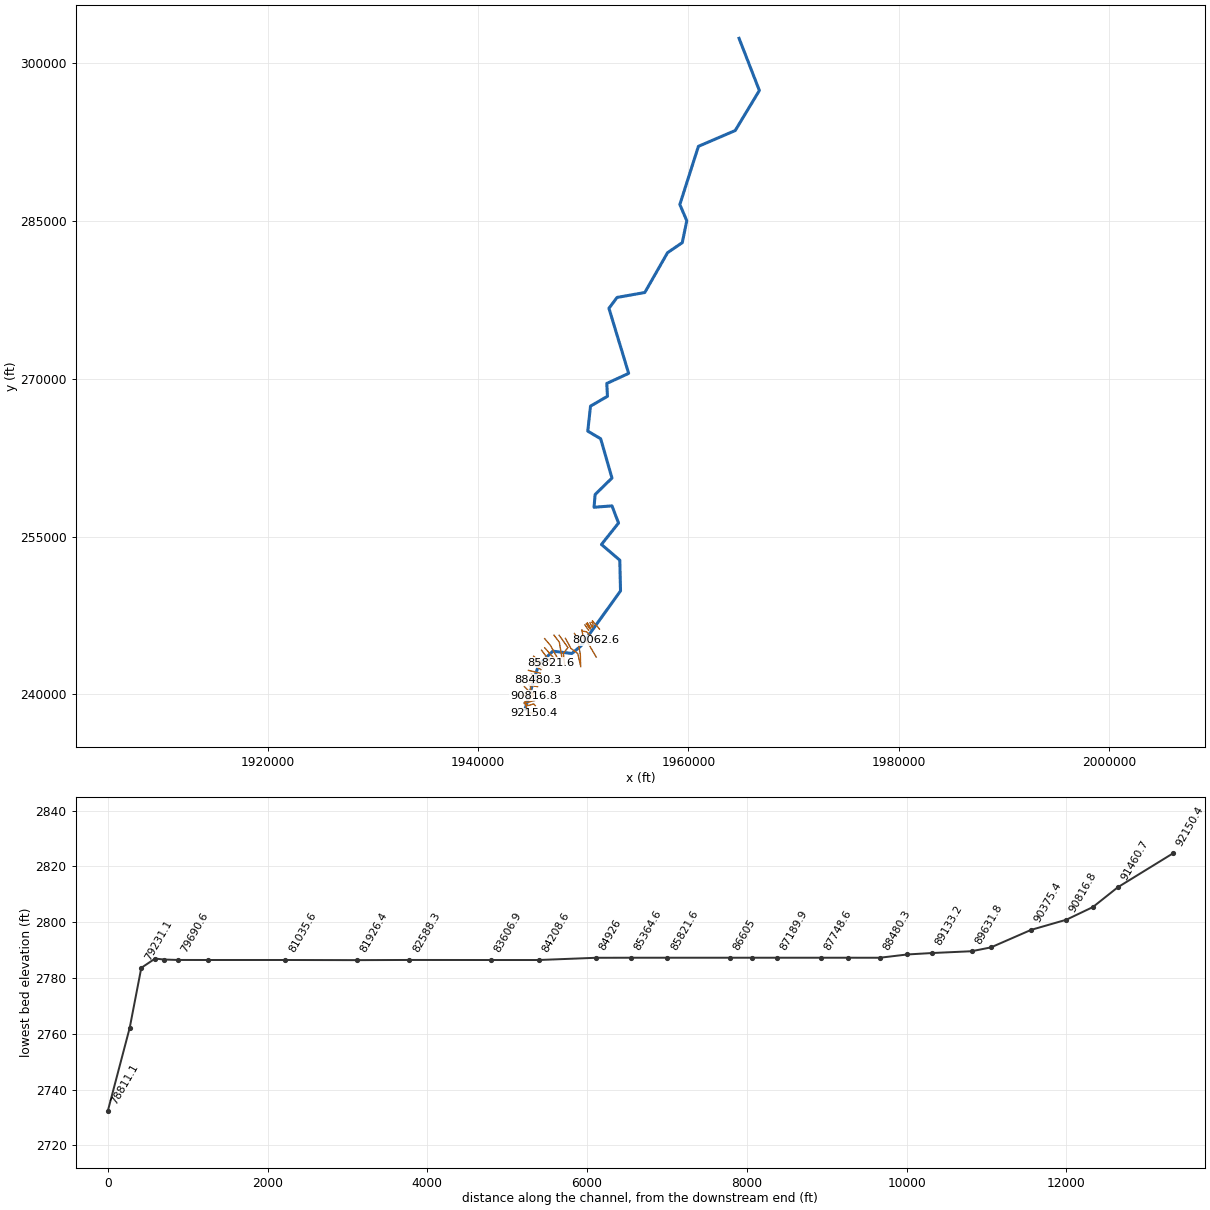
--- GldCrk.prj (project) ---

Proj Title=GldCrk
Current Plan=p02
Default Exp/Contr=0,0
English Units
Geom File=g01
Geom File=c:\temp\GldCrk.g02
Flow File=f01
Plan File=p01
Plan File=p02
BEGIN DESCRIPTION:
END DESCRIPTION:
DSS Export Rating Curves= 0
DSS Export Rating Curve Sorted= 0
DSS Export Volume Flow Curves= 0
DXF OffsetX= 0
DXF OffsetY= 0
DXF ScaleX= 0
DXF ScaleY= 0

--- GldCrk.p01 (plan) ---

Plan Title=Floodplain
Program Version=4.00
Geom File=g01
Flow File=f01
K Sum by GR=0
Std Step Tol=0.01
Critical Tol=0.01
Num of Std Step Trials=20
Max Error Tol=0.3
Flow Tol Ratio=0.001
Split Flow NTrial=30
Split Flow Tol=0.02
Split Flow Ratio=0.02
Log Output Level=0
Friction Slope Method=1
Unsteady Friction Slope Method=2
Unsteady Bridges Friction Slope Method=1
Global Log Level=0
CheckData=False
Run HTab=0
Run UNet=0
Run PostProcess=0
UNET Theta=0
UNET Theta Warmup=0
UNET ZTol=0
UNET ZSATol=0
UNET MxIter=0
UNET MaxInSteps=0
UNET DtIC=0
UNET DtMin=0
UNET MaxCRTS=0
UNET WFStab=0
UNET SFStab=0
UNET WFX=0
UNET SFX=0
UNET DSS MLevel=0
UNET DZMax Abort=0
UNET Convert EG Bridges=0
UNET Use Existing IB Tables=0
UNET Froude Limit=0
UNET Froude Power=0
Write IC File=0
Echo Input=False
Echo Output=False
Write Detailed=0

--- GldCrk.f01 (steady flow) ---

Flow Title=NFF Regression Equation
Program Version=4.00
Number of Profiles=1
Profile Names=P100yr
River Rch & RM=GldCrk,Main      ,92150.4
2469.586
River Rch & RM=GldCrk,Main      ,91148.9
2633.356
River Rch & RM=GldCrk,Main      ,83606.9
2806.819
River Rch & RM=GldCrk,Main      ,73696.5
3101.186
River Rch & RM=GldCrk,Main      ,73179.3
3849.136
River Rch & RM=GldCrk,Main      ,66812.1
3960.190
River Rch & RM=GldCrk,Main      ,56488
4377.581
River Rch & RM=GldCrk,Main      ,43716.9
4837.345
River Rch & RM=GldCrk,Main      ,31729.8
5141.320
River Rch & RM=GldCrk,Main      ,31393.5
6895.091
River Rch & RM=GldCrk,Main      ,23321.4
7420.569
Boundary for River Rch & Prof#=GldCrk,Main      ,1
Up Type=0
Dn Type=3
Dn Slope=0.023025

--- GldCrk.g01 (geometry) ---

Geom Title=USGS 3m DEM
Program Version=4.10

River Reach=GldCrk          ,Main
Reach XY= 30
     1944469.304      238610.482     1945753.305      242802.974
     1947115.706      244109.514     1948923.731      243892.497
        1949779.      244596.401     1953548.648      249835.659
     1953479.617      252754.671     1951734.891      254248.655
     1953360.076      256283.443     1952736.215      257912.999
     1951031.951      257784.745     1951134.815      258995.683
     1952736.378      260560.787     1951661.278      264290.175
     1950435.054      265016.461     1950694.724      267389.386
     1952305.891      268324.782     1952244.191      269546.464
     1954321.819      270503.033     1952447.448      276682.473
     1953216.847      277715.735      1955856.17      278184.485
     1958020.232      281968.339     1959419.972      282921.464
     1959847.055      285000.891     1959186.899      286542.558
     1960952.591      292068.579     1964452.524      293573.808
     1966748.097      297377.193     1964816.226      302331.281

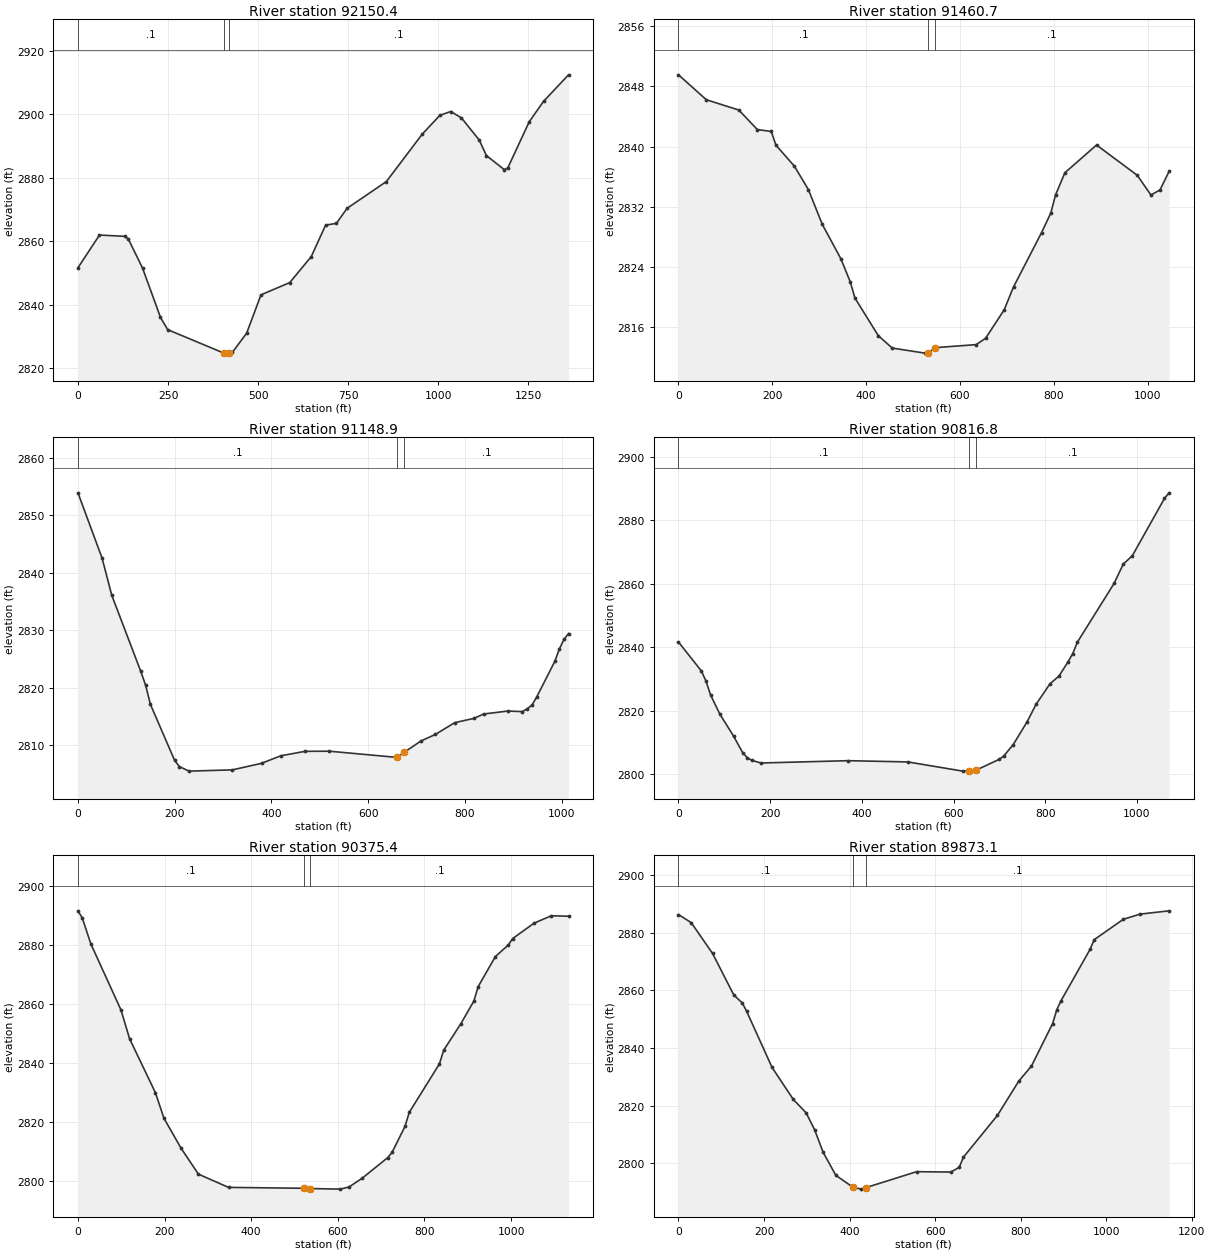
Type RM Length L Ch R = 1 ,92150.4 ,652.6,689.8,727
XS GIS Cut Line= 3
     1944533.978      239021.103     1944704.634      238324.388
     1945337.157      238202.268
#Sta/Elev= 30
       0 2851.59    59.8  2861.9   129.5  2861.5   139.5 2860.72   179.3 2851.49
   229.1 2835.95   249.1 2832.09   404.2 2824.73   418.4 2824.69   419.2 2824.71
   428.4  2824.9   468.2 2830.98   508.1 2843.07   587.8 2846.91   647.6 2855.12
   687.4 2865.03   717.3 2865.58     747 2870.32   856.1 2878.77   955.2 2893.65
  1004.7 2899.64  1034.5 2900.83  1064.2 2898.84  1113.7 2891.84  1133.6 2886.95
  1183.1 2882.52    1193 2883.06  1252.5  2897.6  1292.1 2904.01  1361.5 2912.39
#Mann= 3 , 0 , 0
       0      .1       0   404.2    .045       0   419.2      .1       0
Bank Sta=404.2,419.2
XS Rating Curve= 0 ,0
Exp/Cntr=0.3,0.1

Type RM Length L Ch R = 1 ,91460.7 ,312.2,311.7,311.2
XS GIS Cut Line= 4
     1944510.257       239044.87     1944791.021      238949.523
     1945294.511      239104.672     1945441.005      238937.727
#Sta/Elev= 30
       0 2849.54    59.3 2846.23   128.5 2844.86     168 2842.27   197.7 2842.01
   207.6  2840.2   247.1 2837.39   276.8 2834.29   306.4 2829.67   346.2 2825.08
   366.1 2822.01     376 2819.88   425.7 2814.88   455.6 2813.22   525.2 2812.55
   532.4 2812.56   547.4 2813.28   634.5 2813.68   654.4 2814.52   694.1  2818.3
     714 2821.35   773.7 2828.56   793.5 2831.17   803.5 2833.56   823.4 2836.52
     891 2840.21   977.9 2836.18  1006.8 2833.57  1026.2 2834.24  1045.5  2836.7
#Mann= 3 , 0 , 0
       0      .1       0   532.4    .045       0   547.4      .1       0
Bank Sta=532.4,547.4
XS Rating Curve= 0 ,0
Exp/Cntr=0.3,0.1

Type RM Length L Ch R = 1 ,91148.9 ,326.4,332.3,338.1
XS GIS Cut Line= 3
     1944394.071      239149.096     1945296.573       239407.09
     1945371.977      239412.231
#Sta/Elev= 30
       0 2853.88    49.9 2842.52    69.9 2836.06   129.8 2822.84   139.8 2820.43
   149.8 2817.08   199.7 2807.36   209.7 2806.25   229.7 2805.46   319.5 2805.68
   379.5 2806.82   419.4 2808.13   469.3  2808.9   519.3 2808.93   659.5 2807.85
   674.5 2808.73     709  2810.7   738.9 2811.84   778.9 2813.89   818.8 2814.64
   838.8  2815.4   888.7 2815.91   918.7 2815.82   928.7 2816.28   938.6 2816.94
   948.1  2818.3   985.9 2824.56   995.3  2826.7  1004.8 2828.38  1014.2  2829.4
#Mann= 3 , 0 , 0
       0      .1       0   659.5    .045       0   674.5      .1       0
Bank Sta=659.5,674.5
XS Rating Curve= 0 ,0
Exp/Cntr=0.3,0.1

Type RM Length L Ch R = 1 ,90816.8 ,452.8,441.4,430
XS GIS Cut Line= 2
     1944400.906      239251.613     1945281.171      239860.137
#Sta/Elev= 30
       0 2841.58      50 2832.45      60 2829.25      70  2824.9      90 2818.93
     120 2811.99     140 2806.75     150 2805.16     160  2804.3     180 2803.48
     370 2804.21   500.1 2803.82   620.1 2800.92   633.4    2801   648.4 2801.17
   700.1 2804.67   710.1 2805.77   730.1 2809.27   760.1 2816.37   780.1 2821.98
   810.1 2828.38   830.1 2830.88   850.1 2835.42   860.1 2837.96   870.1 2841.53
   950.1 2860.02   970.1  2866.1   990.1 2868.79  1060.1 2886.81  1070.1 2888.57
#Mann= 3 , 0 , 0
       0      .1       0   633.4    .045       0   648.4      .1       0
Bank Sta=633.4,648.4
XS Rating Curve= 0 ,0
Exp/Cntr=0.3,0.1

Type RM Length L Ch R = 1 ,90375.4 ,520.6,502.1,483.6
XS GIS Cut Line= 2
     1944112.719      239909.144     1945244.481      239950.274
#Sta/Elev= 30
       0 2891.68     9.9 2889.31    29.8 2880.46    99.3 2858.07   119.2  2848.3
   178.8    2830   198.7 2821.27   238.4 2811.08   278.2 2802.35   347.7 2797.87
   521.6 2797.57   536.6 2797.47     606 2797.28   625.9 2798.02   655.7 2800.93
   715.3 2807.98   725.2 2809.76     755 2818.56   764.9 2823.33   834.5 2839.77
   844.4 2844.41   884.2 2853.44     914 2861.07   923.9 2865.95   963.6 2876.15
   993.4 2880.07  1003.4 2882.25    1053  2887.5  1092.8    2890  1132.5 2889.86
#Mann= 3 , 0 , 0
       0      .1       0   521.6    .045       0   536.6      .1       0
Bank Sta=521.6,536.6
XS Rating Curve= 0 ,0
Exp/Cntr=0.3,0.1

Type RM Length L Ch R = 1 ,89873.1 ,258.2,241.1,224.1
XS GIS Cut Line= 3
     1944402.045      240749.783     1945017.146      240141.516
     1945279.635      240038.632
#Sta/Elev= 30
       0 2886.35    29.8 2883.53    79.6 2872.86   129.3 2858.42   149.2 2855.64
   159.1 2852.83   218.8 2833.26   268.5 2822.14   298.3 2817.52   318.2 2811.65
   338.1 2803.83   367.9  2795.8   407.7 2791.69   427.6 2791.01   437.5  2791.5
   556.8 2797.07   636.4 2796.94   656.3 2798.55   666.2  2802.1   745.8 2816.64
   795.5 2828.49   825.3 2833.75   874.8 2848.51   884.5 2853.31   894.2 2856.37
   962.3 2874.27     972 2877.63  1040.1  2884.7    1079 2886.49    1147 2887.64
#Mann= 3 , 0 , 0
       0      .1       0   407.7    .045       0   437.5      .1       0
Bank Sta=407.7,437.5
XS Rating Curve= 0 ,0
Exp/Cntr=0.3,0.1

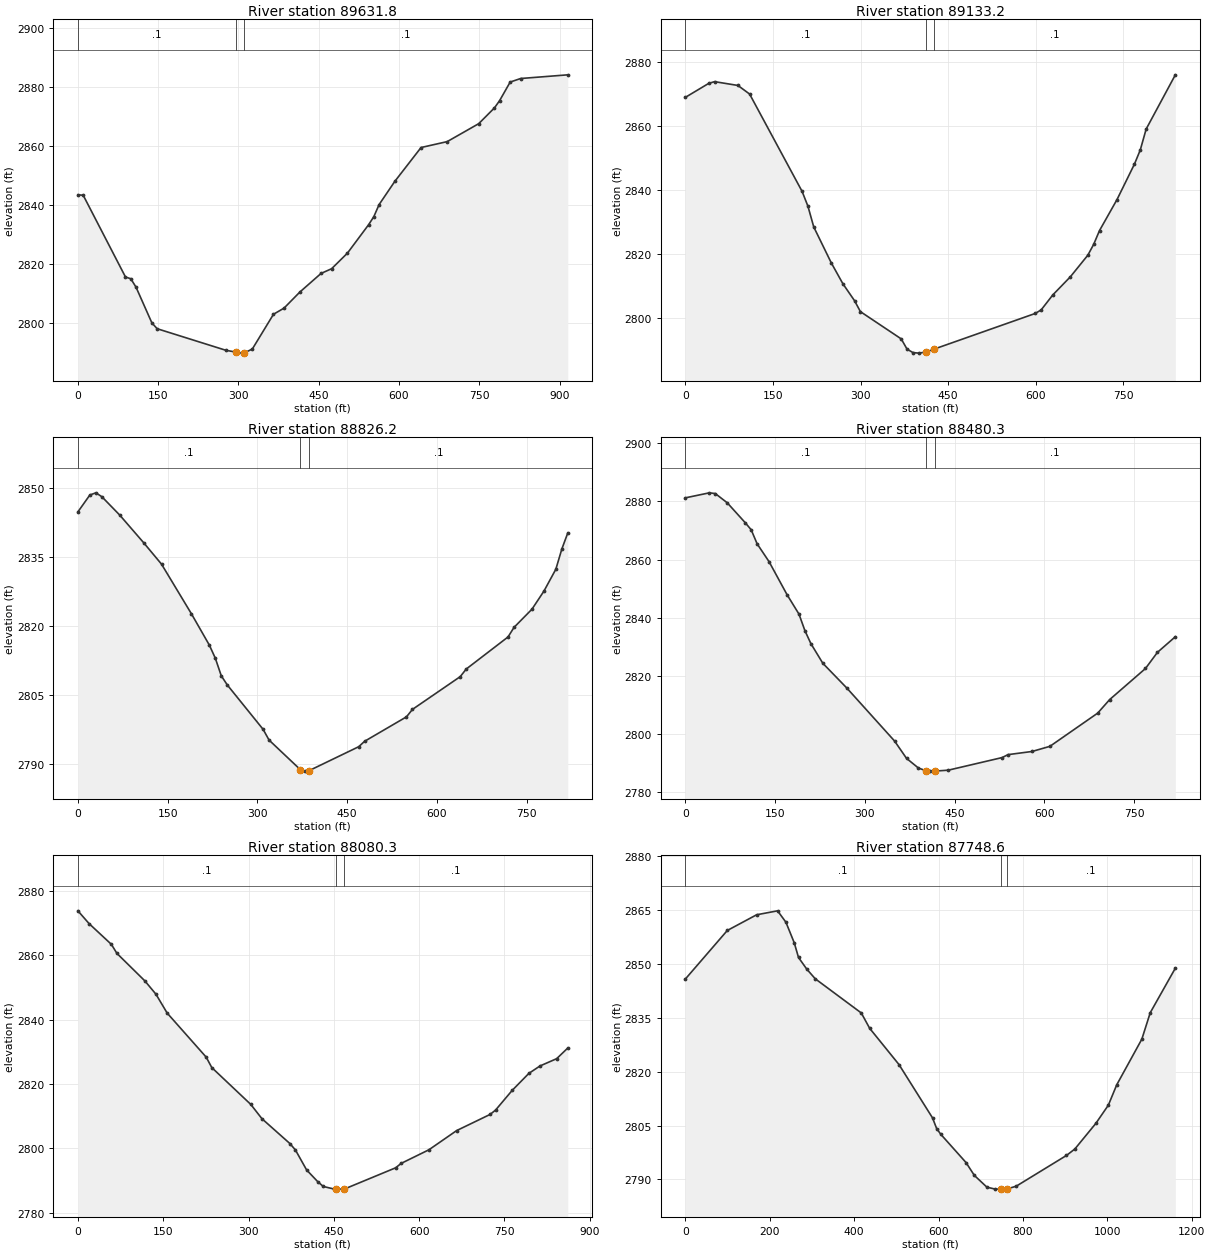
Type RM Length L Ch R = 1 ,89631.8 ,468.2,498.6,528.9
XS GIS Cut Line= 3
      1944987.53      240745.227     1945019.424      240203.026
     1945383.929      240127.847
#Sta/Elev= 30
       0 2843.36     9.9  2843.2    88.9 2815.46    98.8 2814.87   108.6 2812.01
   138.2 2799.89   148.1 2797.91   276.5 2790.59   295.9 2789.96   306.1 2789.63
   310.9 2789.71   325.9 2791.03   365.4 2802.82   385.1  2804.9   414.8 2810.38
   454.3 2816.68     474 2818.27   503.6 2823.57   543.1  2833.2   552.9 2835.95
   562.7 2840.03   592.1 2847.92   641.1  2859.4     690 2861.41   748.8 2867.49
   778.2 2872.84     788 2875.35   807.6 2881.61   827.2 2882.82   915.3 2884.07
#Mann= 3 , 0 , 0
       0      .1       0   295.9    .045       0   310.9      .1       0
Bank Sta=295.9,310.9
XS Rating Curve= 0 ,0
Exp/Cntr=0.3,0.1

Type RM Length L Ch R = 1 ,89133.2 ,305.6,307,308.4
XS GIS Cut Line= 2
     1944833.041      240893.205     1945658.444      240741.734
#Sta/Elev= 30
       0 2868.86      40 2873.22      50 2873.75    89.9 2872.56   109.9 2869.88
   199.8 2839.49   209.8 2834.87   219.8 2828.37   249.8 2817.17   269.7 2810.64
   289.7 2805.34   299.7 2801.94   369.6 2793.43   379.6 2790.23   389.6 2789.16
   399.6 2788.98   411.5 2789.29   426.5 2790.27   599.4 2801.38   609.4 2802.49
   629.4 2807.18   659.4 2812.82   689.3 2819.56   699.3 2822.94   709.3 2827.25
   739.3 2836.94   769.2 2848.02   779.2 2852.45   789.2 2858.94   839.2 2875.88
#Mann= 3 , 0 , 0
       0      .1       0   411.5    .045       0   426.5      .1       0
Bank Sta=411.5,426.5
XS Rating Curve= 0 ,0
Exp/Cntr=0.3,0.1

Type RM Length L Ch R = 1 ,88826.2 ,347.5,345.8,344
XS GIS Cut Line= 2
      1944891.43      241168.132     1945704.439      241069.252
#Sta/Elev= 30
       0 2844.87      20 2848.54      30 2849.01      40 2848.17    69.9 2844.17
   109.9 2838.16   139.8 2833.49   189.8 2822.69   219.7 2815.89   229.7 2813.04
   239.7  2809.2   249.7 2807.22   309.6 2797.56   319.6 2795.22   371.9 2788.79
   379.5 2788.47   386.9  2788.6   469.4 2793.78   479.4 2794.97   549.3 2800.28
   559.3  2801.9   639.2 2809.03   649.2 2810.68   719.1 2817.66   729.1 2819.74
   759.1  2823.7     779 2827.61     799 2832.39     809 2836.78     819  2840.3
#Mann= 3 , 0 , 0
       0      .1       0   371.9    .045       0   386.9      .1       0
Bank Sta=371.9,386.9
XS Rating Curve= 0 ,0
Exp/Cntr=0.3,0.1

Type RM Length L Ch R = 1 ,88480.3 ,401,400,395.9
XS GIS Cut Line= 3
     1944928.159      241541.757     1945329.919      241462.537
     1945730.984      241379.751
#Sta/Elev= 30
       0 2881.22      40 2882.94    49.9 2882.69    69.9 2879.51    99.9 2872.68
   109.9 2870.25   119.8 2865.43   139.8 2859.28   169.8 2847.95   189.8 2841.26
   199.8 2835.53   209.7 2831.12   229.7 2824.35   269.7 2815.87   349.6 2797.64
   369.6 2791.68   389.5 2788.35     402 2787.44   409.5 2787.29     417  2787.3
   439.5 2787.62   529.4 2791.95   539.3 2792.96   579.3 2794.04   609.3 2795.81
   689.2 2807.23   709.2 2811.88   769.1 2822.57     789  2828.1     819 2833.48
#Mann= 3 , 0 , 0
       0      .1       0     402    .045       0     417      .1       0
Bank Sta=402,417
XS Rating Curve= 0 ,0
Exp/Cntr=0.3,0.1

Type RM Length L Ch R = 1 ,88080.3 ,331,331.7,335.7
XS GIS Cut Line= 3
     1945069.141      241913.396      1945517.17      241805.085
     1945888.954      241656.372
#Sta/Elev= 30
       0 2873.79    19.6 2869.82    58.8 2863.38    68.6 2860.56   117.7 2852.02
   137.3 2847.86   156.9 2842.02   225.6 2828.31   235.4 2825.08     304 2813.62
   323.6 2809.18   372.7 2801.47   382.5 2799.46   402.1 2793.27   421.7 2789.62
   431.5 2788.12   451.1  2787.3   453.4  2787.3   468.4 2787.32   558.6 2793.92
   568.4  2795.3   617.2 2799.53     666  2805.5   724.6  2810.5   734.4 2811.87
   763.7 2818.01     793 2823.28   812.5 2825.58   841.8 2827.84   861.4 2831.16
#Mann= 3 , 0 , 0
       0      .1       0   453.4    .045       0   468.4      .1       0
Bank Sta=453.4,468.4
XS Rating Curve= 0 ,0
Exp/Cntr=0.3,0.1

Type RM Length L Ch R = 1 ,87748.6 ,566.8,558.3,549.8
XS GIS Cut Line= 2
     1944797.876      242286.162      1945928.89      242022.964
#Sta/Elev= 30
       0 2845.81    99.2  2859.3   168.7 2863.67   218.4 2864.77   238.2 2861.59
     258 2855.84     268 2851.78   287.8 2848.51   307.7 2845.85   416.8 2836.34
   436.7 2832.06   506.2 2821.97   585.6 2807.14   595.5 2804.14   605.4 2802.54
     665 2794.71   684.8 2791.12   714.6 2787.84   734.5  2787.3   746.8  2787.3
   761.8 2787.33   784.1 2788.12   903.2 2796.68     923 2798.47   972.7 2805.59
  1002.4 2810.67  1022.3 2816.34  1081.8 2829.05  1101.7 2836.41  1161.2 2848.81
#Mann= 3 , 0 , 0
       0      .1       0   746.8    .045       0   761.8      .1       0
Bank Sta=746.8,761.8
XS Rating Curve= 0 ,0
Exp/Cntr=0.3,0.1

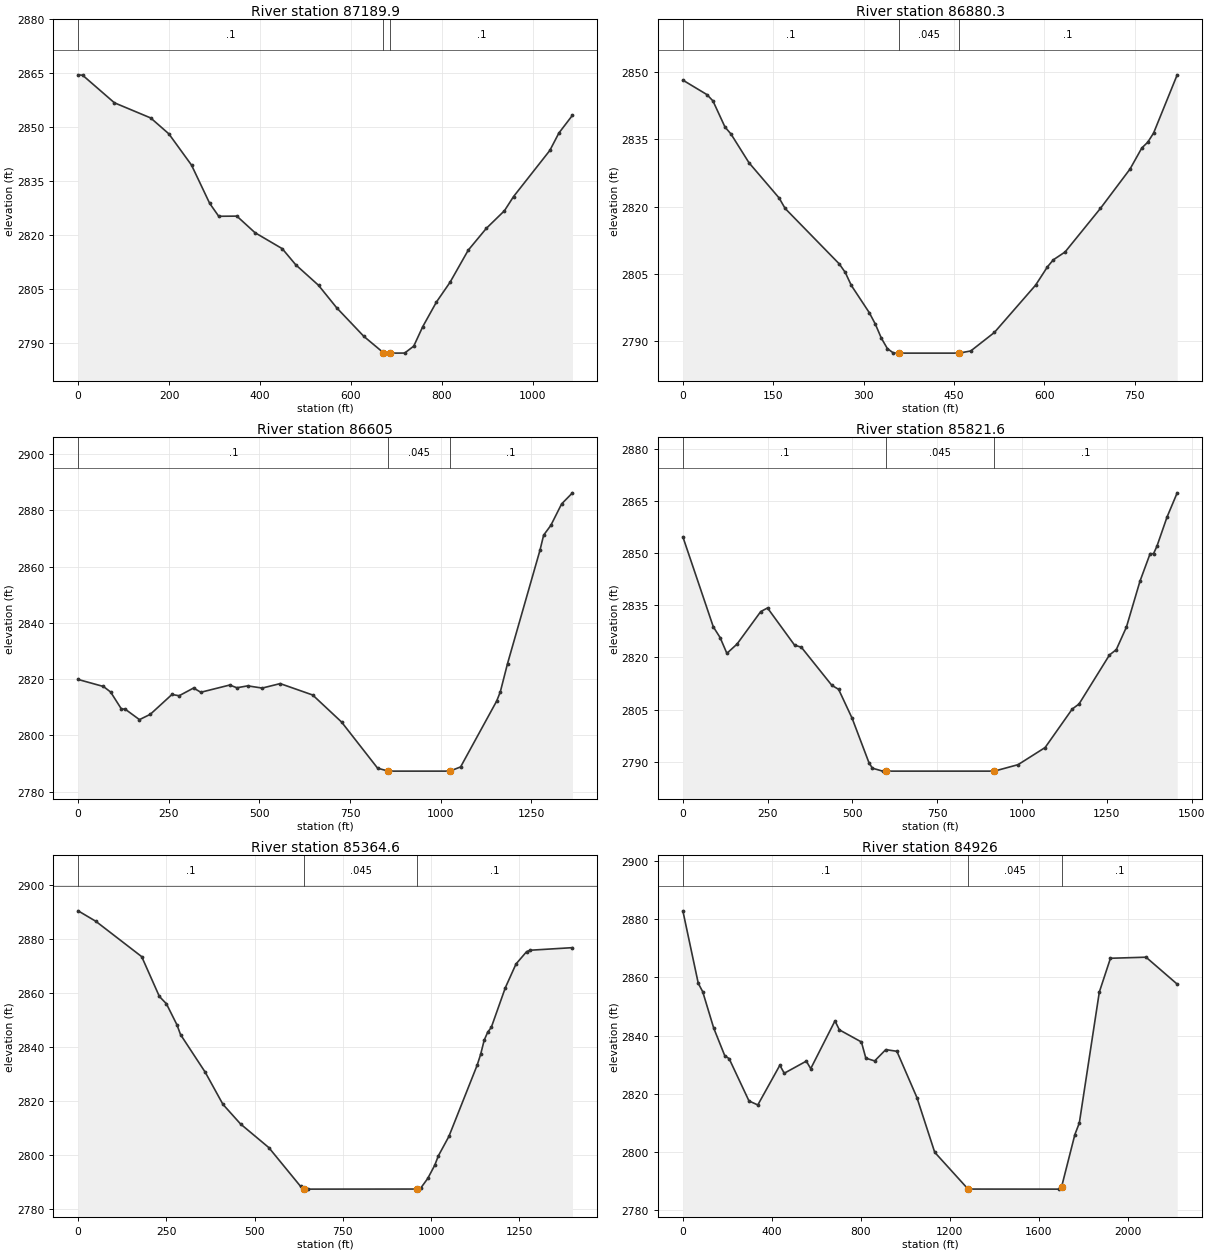
Type RM Length L Ch R = 1 ,87189.9 ,312.8,309.6,306.9
XS GIS Cut Line= 2
     1945085.783      242981.937     1945976.847      242358.818
#Sta/Elev= 30
       0 2864.61      10 2864.49    79.8 2856.84   159.6 2852.63   199.5 2848.22
   249.4 2839.53   289.3 2828.91   309.2 2825.32   349.1 2825.36     389 2820.76
   448.9 2816.32   478.8 2811.82   528.7 2806.15   568.6 2799.91   628.4 2791.96
   671.6  2787.4   678.3  2787.3   686.6  2787.3   718.2 2787.32   738.2 2789.25
   758.1 2794.69   788.1  2801.5     818 2806.98   857.9 2815.88   897.8 2821.96
   937.7 2826.86   957.6 2830.78  1037.4 2843.59  1057.4 2848.44  1087.3 2853.38
#Mann= 3 , 0 , 0
       0      .1       0   671.6    .045       0   686.6      .1       0
Bank Sta=671.6,686.6
XS Rating Curve= 0 ,0
Exp/Cntr=0.3,0.1

Type RM Length L Ch R = 1 ,86880.3 ,273.9,275.3,276.1
XS GIS Cut Line= 3
     1945502.941      243134.325     1945801.684      242854.652
     1946108.825      242581.449
#Sta/Elev= 30
       0 2848.26    39.9 2845.03    49.9 2843.63    69.9 2837.79    79.8 2836.24
   109.8  2829.8   159.7 2821.95   169.7 2819.61   259.5 2807.23   269.5 2805.32
   279.5 2802.43   309.4 2796.33   319.4 2793.78   329.4 2790.64   339.4 2788.31
   349.3 2787.34   359.3  2787.3   458.2  2787.3   477.7 2787.78   516.9 2791.91
   585.4 2802.49     605 2806.57   614.8 2808.14   634.3 2809.89     693 2819.63
     742  2828.4   761.6 2833.11   771.4 2834.39   781.1 2836.43   820.3 2849.44
#Mann= 3 , 0 , 0
       0      .1       0   359.3    .045       0   458.2      .1       0
Bank Sta=359.3,458.2
XS Rating Curve= 0 ,0
Exp/Cntr=0.3,0.1

Type RM Length L Ch R = 1 ,86605   ,788.4,782.2,776
XS GIS Cut Line= 2
     1945292.043      243634.304     1946336.975      242758.061
#Sta/Elev= 30
       0 2819.88    69.7 2817.39    89.6 2815.42   119.4 2809.38   129.4 2809.36
   169.2  2805.6   199.1  2807.5   258.8 2814.54   278.7  2814.1   318.5 2816.84
   338.4 2815.33   418.1  2817.9     438 2816.93   467.8 2817.61   507.7 2816.82
   557.4 2818.41     647 2814.36   726.6 2804.77   826.2 2788.34     856  2787.3
  1025.3  2787.3  1055.1  2788.8  1154.7 2812.24  1164.6 2815.47  1184.5 2825.52
  1274.1 2865.84  1284.1 2871.17    1304 2874.66  1333.8 2882.29  1363.7 2886.22
#Mann= 3 , 0 , 0
       0      .1       0     856    .045       0  1025.3      .1       0
Bank Sta=856,1025.3
XS Rating Curve= 0 ,0
Exp/Cntr=0.3,0.1

Type RM Length L Ch R = 1 ,85821.6 ,453.7,456.6,459.5
XS GIS Cut Line= 2
     1946042.315      244205.361     1946908.013      243032.872
#Sta/Elev= 30
       0 2854.69    89.8 2828.79   109.8 2825.72   129.8 2821.17   159.7 2823.83
   229.6 2833.18   249.6 2834.22   329.4 2823.53   349.4 2822.92   439.2 2811.98
   459.2 2810.82   499.1 2802.49     549 2789.64     559 2788.14     589  2787.3
     599  2787.3   918.4  2787.3   988.3 2789.16  1068.1 2794.09    1148 2805.16
    1168 2806.61  1257.8 2820.71  1277.8 2822.23  1307.7 2828.72  1347.6  2841.9
  1377.6 2849.84  1387.6 2849.83  1397.6 2851.96  1427.5 2860.38  1457.4 2867.33
#Mann= 3 , 0 , 0
       0      .1       0     599    .045       0   918.4      .1       0
Bank Sta=599,918.4
XS Rating Curve= 0 ,0
Exp/Cntr=0.3,0.1

Type RM Length L Ch R = 1 ,85364.6 ,442.5,437.9,434.3
XS GIS Cut Line= 2
     1946343.031      244430.139     1947275.555      243385.226
#Sta/Elev= 30
       0 2890.54      50 2886.67   180.1 2873.54   230.1 2858.79   250.1 2856.06
   280.1 2848.22   290.1 2844.63   360.1 2830.66   410.2 2818.76   460.2 2811.46
   540.2 2802.71   630.2 2788.32   640.2 2787.48   650.2  2787.3   960.4 2787.33
   970.4 2787.65   990.4 2791.25  1010.4 2796.19  1020.4 2799.62  1050.4 2806.86
  1130.4 2833.26  1140.4 2837.34  1150.4 2842.57  1160.4 2845.55  1170.4 2847.27
  1210.4 2862.06  1240.5 2870.82  1270.5 2875.39  1280.5 2875.92  1400.5 2876.88
#Mann= 3 , 0 , 0
       0      .1       0   640.2    .045       0   960.4      .1       0
Bank Sta=640.2,960.4
XS Rating Curve= 0 ,0
Exp/Cntr=0.3,0.1

Type RM Length L Ch R = 1 ,84926   ,728.2,718.3,707.5
XS GIS Cut Line= 3
     1946336.956      245301.912     1946895.863      244645.804
     1947551.971       243455.09
#Sta/Elev= 30
       0 2882.84    69.4 2857.92    89.2 2855.08   138.7 2842.58   188.2 2833.13
     208 2832.08   297.2 2817.56   336.8 2816.18   435.9 2829.82   455.7 2827.07
   554.8 2831.23   574.6 2828.65   683.6 2845.05   703.4 2841.97   802.4 2837.81
   822.3 2832.25   861.9  2831.3   911.9 2835.18   961.8 2834.61  1051.8 2818.73
  1131.8 2799.93  1281.7  2787.3  1691.6 2787.28  1701.6 2787.96  1761.6 2806.02
  1781.6    2810  1871.5 2854.96  1921.5 2866.55  2081.4 2866.92  2221.4 2857.67
#Mann= 3 , 0 , 0
       0      .1       0  1281.7    .045       0  1701.6      .1       0
Bank Sta=1281.7,1701.6
XS Rating Curve= 0 ,0
Exp/Cntr=0.3,0.1

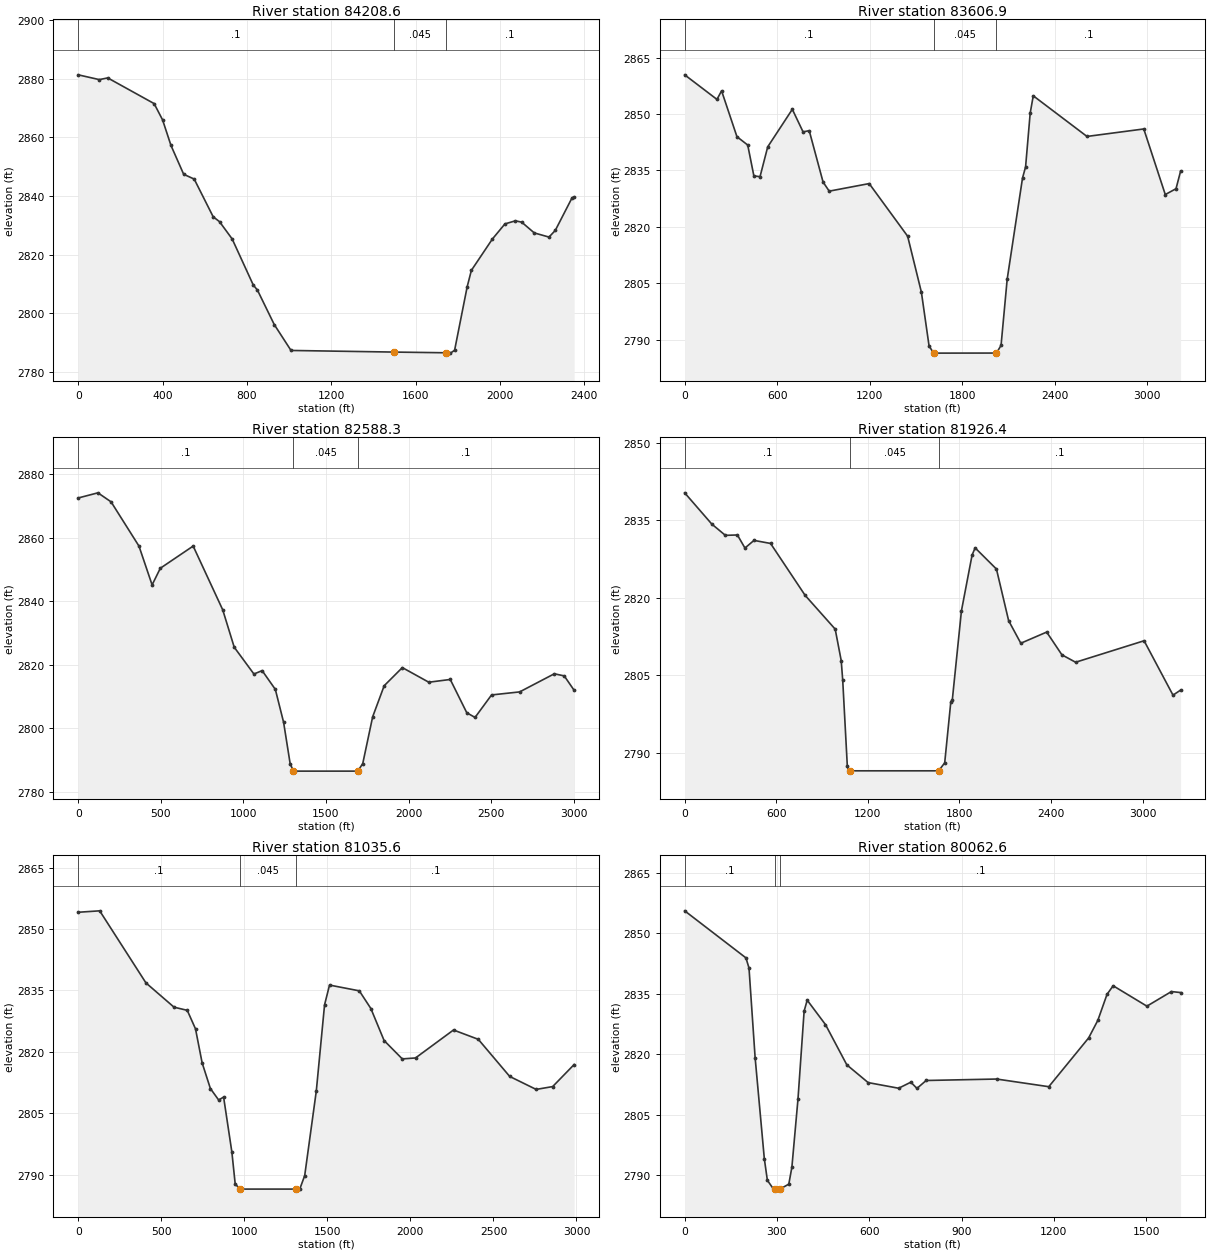
Type RM Length L Ch R = 1 ,84208.6 ,618.1,599.7,581.2
XS GIS Cut Line= 3
     1947217.842      245636.042     1947731.186      244970.821
     1947980.264       243479.39
#Sta/Elev= 30
       0 2881.27     100 2879.64     140 2880.22   360.1 2871.47   400.1 2865.94
   440.1  2857.2   500.2  2847.4   550.2 2845.76   640.2 2832.92   670.2 2831.26
   730.2 2825.37   830.3 2809.69   850.2 2807.94   929.8 2796.22  1009.4 2787.39
  1496.2 2786.84  1745.5  2786.6  1765.4 2786.48  1785.3 2787.44    1845 2809.09
  1864.9 2814.67  1964.4 2825.33  2024.1  2830.5  2073.8 2831.54  2103.6 2831.09
  2163.3 2827.42    2233 2826.01  2262.8 2828.26  2342.4 2839.37  2352.4 2839.67
#Mann= 3 , 0 , 0
       0      .1       0  1496.2    .045       0  1745.5      .1       0
Bank Sta=1496.2,1745.5
XS Rating Curve= 0 ,0
Exp/Cntr=0.3,0.1

Type RM Length L Ch R = 1 ,83606.9 ,980.6,1017.9,1055.3
XS GIS Cut Line= 4
     1947715.998      245623.891     1948553.899       244445.71
     1948114.637      243919.731     1948235.417      242841.507
#Sta/Elev= 30
       0 2860.41   209.4 2853.88   239.3 2856.16     339 2843.97   408.8 2841.76
   448.7 2833.56   488.6 2833.35   538.4 2841.27     698 2851.25   767.7 2845.25
   807.6 2845.58   897.4 2831.93   937.2 2829.51  1196.5 2831.52  1445.8 2817.54
  1535.1 2802.65  1584.8 2788.37  1614.6 2786.48  2021.8  2786.5  2051.6 2788.54
  2091.3  2806.1  2190.8    2833  2210.7 2835.96  2240.5 2850.23  2260.4 2854.84
  2608.8 2844.04  2977.1 2846.03  3116.5 2828.61  3186.1 2830.15    3216 2834.84
#Mann= 3 , 0 , 0
       0      .1       0  1614.6    .045       0  2021.8      .1       0
Bank Sta=1614.6,2021.8
XS Rating Curve= 0 ,0
Exp/Cntr=0.3,0.1

Type RM Length L Ch R = 1 ,82588.3 ,680.4,661.7,642.6
XS GIS Cut Line= 4
     1948311.355      245332.288     1948838.672      244362.752
     1949481.979      243889.099     1949729.885      242817.207
#Sta/Elev= 30
       0 2872.59   119.3 2874.21   198.9 2871.37   367.9 2857.42   447.4 2845.19
   497.1 2850.44     696 2857.43     875 2837.33   944.6 2825.55  1063.9  2817.1
  1113.6 2818.18  1193.5 2812.26  1243.5  2801.9  1283.4 2788.78  1303.4 2786.52
  1313.4  2786.5  1692.8  2786.5  1722.8  2788.9  1782.7 2803.61  1852.6 2813.42
  1962.5 2819.13  2122.6 2814.52  2252.6 2815.39  2352.6  2804.9  2402.6 2803.42
  2502.6 2810.51  2672.7 2811.47  2882.7 2817.18  2942.7 2816.51  3002.7 2811.97
#Mann= 3 , 0 , 0
       0      .1       0  1303.4    .045       0  1692.8      .1       0
Bank Sta=1303.4,1692.8
XS Rating Curve= 0 ,0
Exp/Cntr=0.3,0.1

Type RM Length L Ch R = 1 ,81926.4 ,878.4,890.3,902.2
XS GIS Cut Line= 5
     1949164.903      245797.031     1949445.933      245309.539
     1949535.483      244855.394     1949729.828      243775.761
     1949757.991      242649.187
#Sta/Elev= 30
       0 2840.32   177.7 2834.27   266.5 2832.09   345.5 2832.16   394.9 2829.63
   454.1 2831.11   562.7 2830.52   789.2 2820.47   986.2 2813.93  1025.6 2807.85
  1035.6    2804  1065.5 2787.49  1075.4 2786.44  1085.4  2786.5  1663.8  2786.5
  1703.7 2788.04  1743.6 2799.81  1753.6 2800.23  1813.4 2817.48  1883.2 2828.28
  1903.2 2829.66  2042.8 2825.56  2122.6 2815.57  2202.4  2811.2  2371.9 2813.36
  2471.6 2808.96  2561.4 2807.52  3010.2 2811.68  3199.6 2801.15  3249.5 2802.13
#Mann= 3 , 0 , 0
       0      .1       0  1085.4    .045       0  1663.8      .1       0
Bank Sta=1085.4,1663.8
XS Rating Curve= 0 ,0
Exp/Cntr=0.3,0.1

Type RM Length L Ch R = 1 ,81035.6 ,956.1,972.8,989.5
XS GIS Cut Line= 4
     1949869.612      246140.273     1950018.451      245368.738
     1950551.488      244723.483     1951241.703      243547.945
#Sta/Elev= 30
       0  2854.1   129.3 2854.45   407.8 2836.85   576.9 2830.92   656.5 2830.15
   706.2 2825.62     746 2817.34   795.7 2811.06   845.5 2808.26   875.4 2808.96
   925.2 2795.52   945.2 2787.73   975.1  2786.5  1313.8  2786.5  1333.8 2786.49
  1363.6 2789.79  1433.4 2810.43  1483.2  2831.5  1513.1 2836.32  1692.4 2834.91
    1762 2830.59  1841.6 2822.78  1951.1 2818.29  2030.7 2818.52  2259.5 2825.35
  2408.8 2823.07  2597.8 2814.01    2757 2810.84  2856.5 2811.53  2985.9 2816.92
#Mann= 3 , 0 , 0
       0      .1       0   975.1    .045       0  1313.8      .1       0
Bank Sta=975.1,1313.8
XS Rating Curve= 0 ,0
Exp/Cntr=0.3,0.1

Type RM Length L Ch R = 1 ,80062.6 ,390.4,372,353.6
XS GIS Cut Line= 4
     1949911.672      246017.988     1950305.481       245958.52
      1950562.36      245740.552     1951223.568      245164.375
#Sta/Elev= 30
       0 2855.53   199.1 2843.86   209.1 2841.35     229 2819.12   258.9 2794.04
   268.8 2788.68   288.8 2786.49   294.6  2786.5   309.6  2786.5   338.5 2787.73
   348.5 2791.93   368.4 2808.89   388.3 2830.65   398.3 2833.37   457.7 2827.31
   527.1 2817.32   596.4 2812.92   695.5 2811.52   735.2 2813.02   755.1 2811.48
     785 2813.44  1014.2  2813.8  1183.6  2811.9  1313.2    2824  1343.1 2828.36
    1373 2834.82  1392.9 2836.94  1502.6 2831.88  1582.3  2835.5  1612.2 2835.26
#Mann= 3 , 0 , 0
       0      .1       0   294.6    .045       0   309.6      .1       0
Bank Sta=294.6,309.6
XS Rating Curve= 0 ,0
Exp/Cntr=0.3,0.1

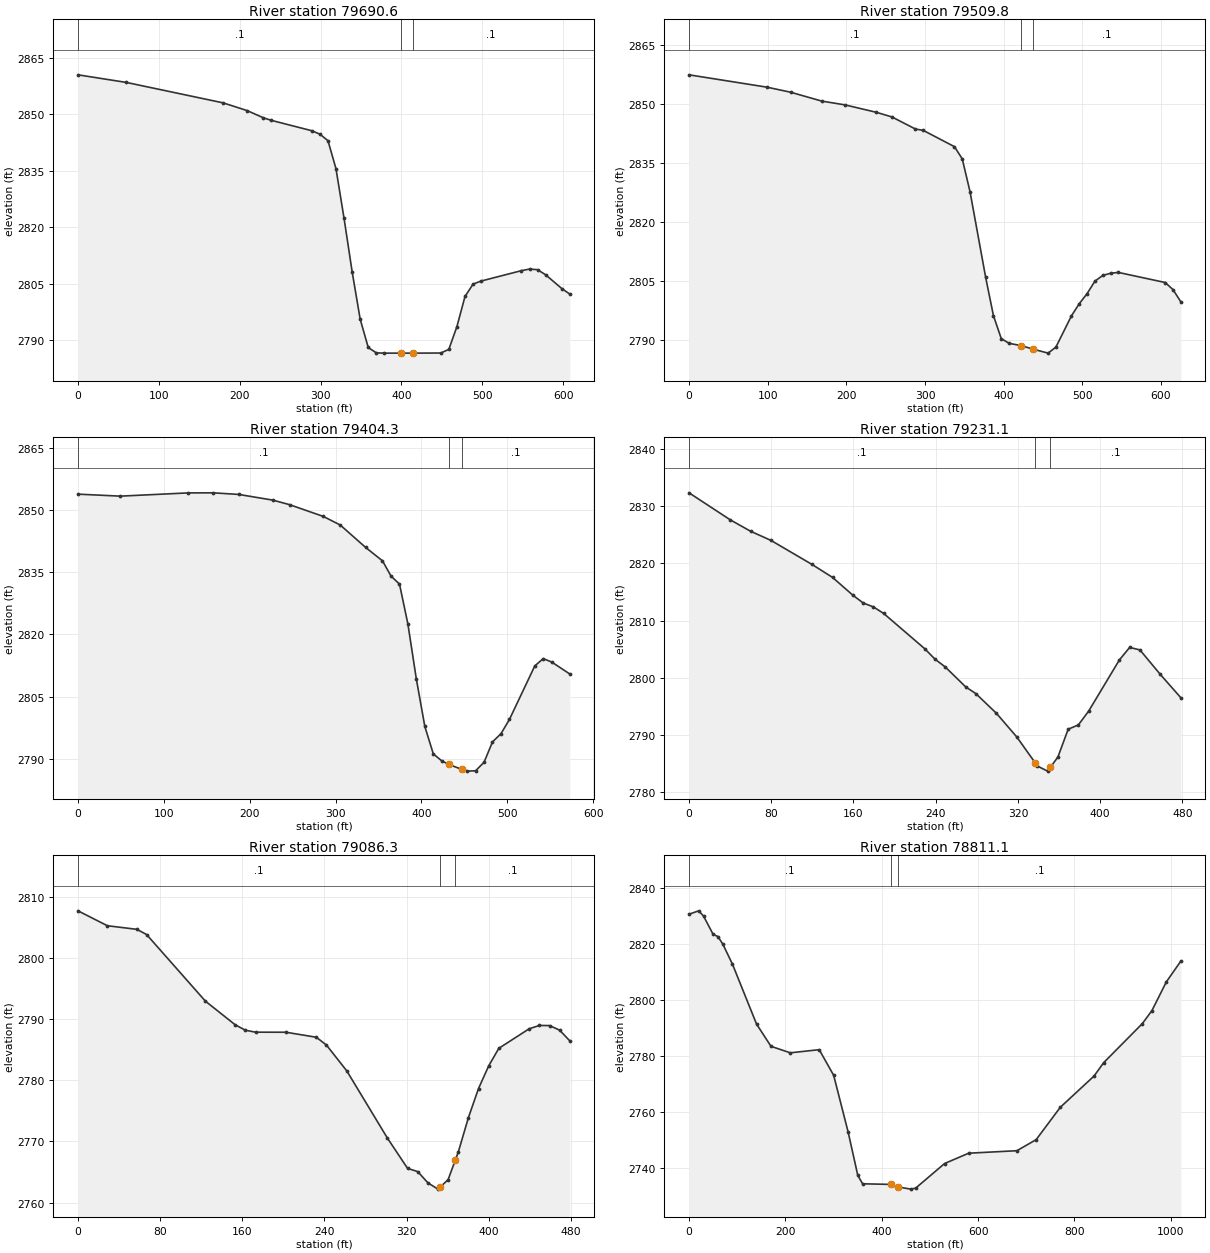
Type RM Length L Ch R = 1 ,79690.6 ,180.3,180.8,181.2
XS GIS Cut Line= 2
     1950162.587      246605.765     1950509.794      246106.249
#Sta/Elev= 30
       0 2860.47    59.8 2858.45   179.5 2853.02   209.4 2850.95   229.4 2849.04
   239.3 2848.36   289.2 2845.61   299.2  2844.7   309.2 2842.96   319.1 2835.53
   329.1 2822.32   339.1 2808.13     349 2795.56     359    2788     369 2786.57
     379  2786.5     399  2786.5     414  2786.5   448.8 2786.53   458.7  2787.5
   468.7 2793.55   478.7 2801.56   488.7 2804.85   498.6 2805.66   548.5 2808.42
   558.5 2808.84   568.4 2808.68   578.4 2807.33   598.4 2803.67   608.3 2802.19
#Mann= 3 , 0 , 0
       0      .1       0     399    .045       0     414      .1       0
Bank Sta=399,414
XS Rating Curve= 0 ,0
Exp/Cntr=0.3,0.1

Type RM Length L Ch R = 1 ,79509.8 ,106.8,105.6,104.3
XS GIS Cut Line= 2
     1950292.606      246719.908     1950659.745      246213.892
#Sta/Elev= 30
       0 2857.32    99.2 2854.18     129 2852.91   168.7 2850.65   198.5 2849.68
   238.2  2847.8     258 2846.62   287.8 2843.56   297.7 2843.22   337.4 2839.08
   347.3 2835.99   357.2 2827.65   377.1 2805.88     387 2796.15   396.9 2790.36
   406.9 2789.14   422.3 2788.57   437.3 2787.67   456.5 2786.66   466.4  2788.2
   486.2 2796.14   496.2 2799.24   506.1 2801.78     516 2804.94   525.9 2806.38
   535.9 2806.94   545.8 2807.15   605.3 2804.59   615.2  2802.8   625.2 2799.69
#Mann= 3 , 0 , 0
       0      .1       0   422.3    .045       0   437.3      .1       0
Bank Sta=422.3,437.3
XS Rating Curve= 0 ,0
Exp/Cntr=0.3,0.1

Type RM Length L Ch R = 1 ,79404.3 ,176.4,173.2,170
XS GIS Cut Line= 3
     1950397.025      246796.956     1950695.606      246333.067
      1950708.42      246316.408
#Sta/Elev= 30
       0 2853.86    49.3 2853.38   128.1 2854.16   157.6 2854.18   187.2 2853.79
   226.6 2852.43   246.3 2851.33   285.7 2848.48   305.4 2846.41   334.9 2841.01
   354.6 2837.76   364.5 2834.09   374.4 2832.15   384.2 2822.49     394 2809.26
   403.9 2797.78   413.8 2791.15   423.6 2789.48   431.9 2788.62   446.9 2787.42
   453.2    2787     463 2787.08   472.9 2789.15   482.7 2794.05   492.6 2796.04
   502.4 2799.47     532 2812.41   541.8 2814.16   551.7 2813.33   572.7 2810.45
#Mann= 3 , 0 , 0
       0      .1       0   431.9    .045       0   446.9      .1       0
Bank Sta=431.9,446.9
XS Rating Curve= 0 ,0
Exp/Cntr=0.3,0.1

Type RM Length L Ch R = 1 ,79231.1 ,155,144.8,134.5
XS GIS Cut Line= 2
     1950642.087      246826.412      1950840.88      246391.123
#Sta/Elev= 30
       0 2832.34    39.9 2827.64    59.8 2825.63    79.8 2824.01   119.6 2819.82
   139.6 2817.55   159.5 2814.42   169.5 2813.07   179.4 2812.39   189.4 2811.24
   229.3 2805.08   239.3 2803.25   249.2  2801.9   269.2  2798.4   279.1 2797.22
   299.1 2793.78     319 2789.62   336.6 2785.17     339 2784.55   348.9 2783.67
   351.6 2784.34   358.9 2786.14   368.9    2791   378.8 2791.75   388.8 2794.16
   418.7 2803.11   428.7  2805.3   438.7 2804.87   458.6 2800.57   478.5 2796.51
#Mann= 3 , 0 , 0
       0      .1       0   336.6    .045       0   351.6      .1       0
Bank Sta=336.6,351.6
XS Rating Curve= 0 ,0
Exp/Cntr=0.3,0.1

Type RM Length L Ch R = 1 ,79086.3 ,258.9,275.1,291.4
XS GIS Cut Line= 3
     1950819.714      246857.962     1950924.205      246759.981
     1950924.653      246424.212
#Sta/Elev= 30
       0 2807.77    28.6 2805.33    57.3 2804.74    66.8 2803.89   124.1 2792.98
   153.1 2789.11     163 2788.22   172.9  2787.9   202.5 2787.89   232.1 2787.07
     242 2785.79   261.8 2781.56   301.2  2770.6     321  2765.6   330.9 2765.07
   340.8 2763.23   350.6  2762.2   352.5  2762.5   360.5 2763.75   367.5 2766.95
   370.4 2768.27   380.3 2773.92   390.1 2778.67     400 2782.37   409.9 2785.26
   439.5 2788.46   449.4    2789   459.3 2788.98   469.1 2788.23     479 2786.48
#Mann= 3 , 0 , 0
       0      .1       0   352.5    .045       0   367.5      .1       0
Bank Sta=352.5,367.5
XS Rating Curve= 0 ,0
Exp/Cntr=0.3,0.1

Type RM Length L Ch R = 1 ,78811.1 ,341,330.9,324.3
XS GIS Cut Line= 2
     1950885.119      246988.421     1951546.938      246211.181
#Sta/Elev= 30
       0 2830.75      20 2831.96      30  2830.1      50 2823.53      60 2822.74
    70.1 2820.04    90.1 2812.85   140.1  2791.4   170.1 2783.43   210.2  2781.1
   270.2 2782.23   300.2 2773.04   330.3 2752.67   350.3 2737.18   360.3 2734.19
   419.3 2733.97   434.3 2733.04   460.4 2732.28   470.4 2732.64   530.4 2741.45
   580.5 2745.15   680.6 2746.04   720.6 2750.02   770.6 2761.59   840.7 2772.79
   860.7 2777.59   940.8 2791.54   960.8 2796.22   990.8 2806.53  1020.8 2813.94
#Mann= 3 , 0 , 0
       0      .1       0   419.3    .045       0   434.3      .1       0
Bank Sta=419.3,434.3
XS Rating Curve= 0 ,0
Exp/Cntr=0.3,0.1