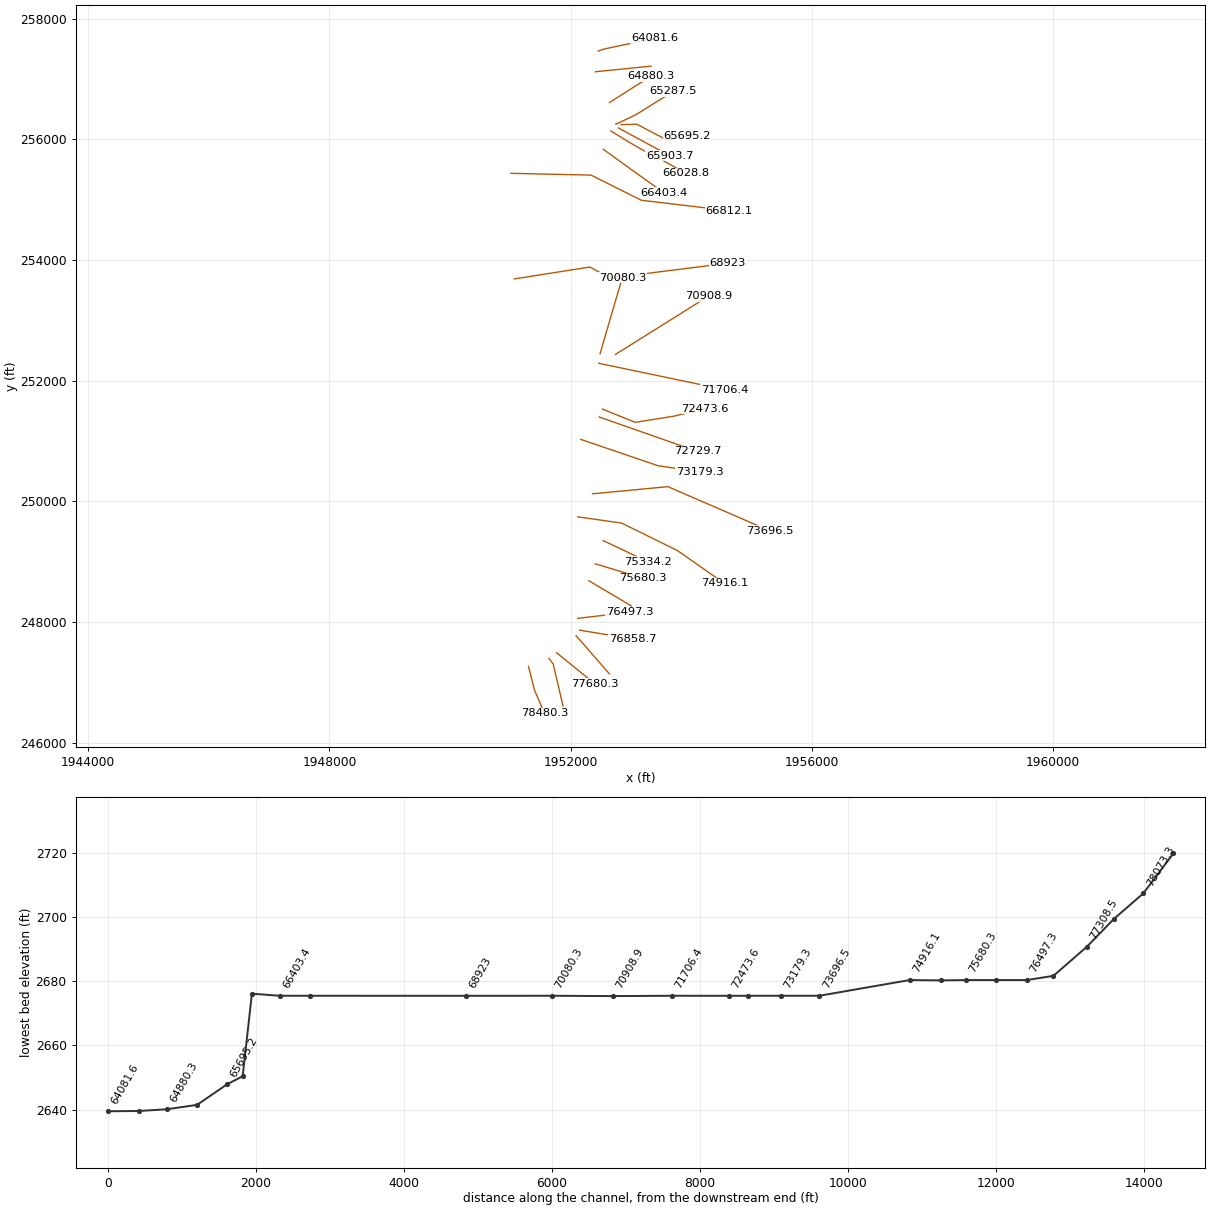
HEC-RAS study GldCrk.prj: GldCrk

--- GldCrk.g01 (geometry) --- (continued)

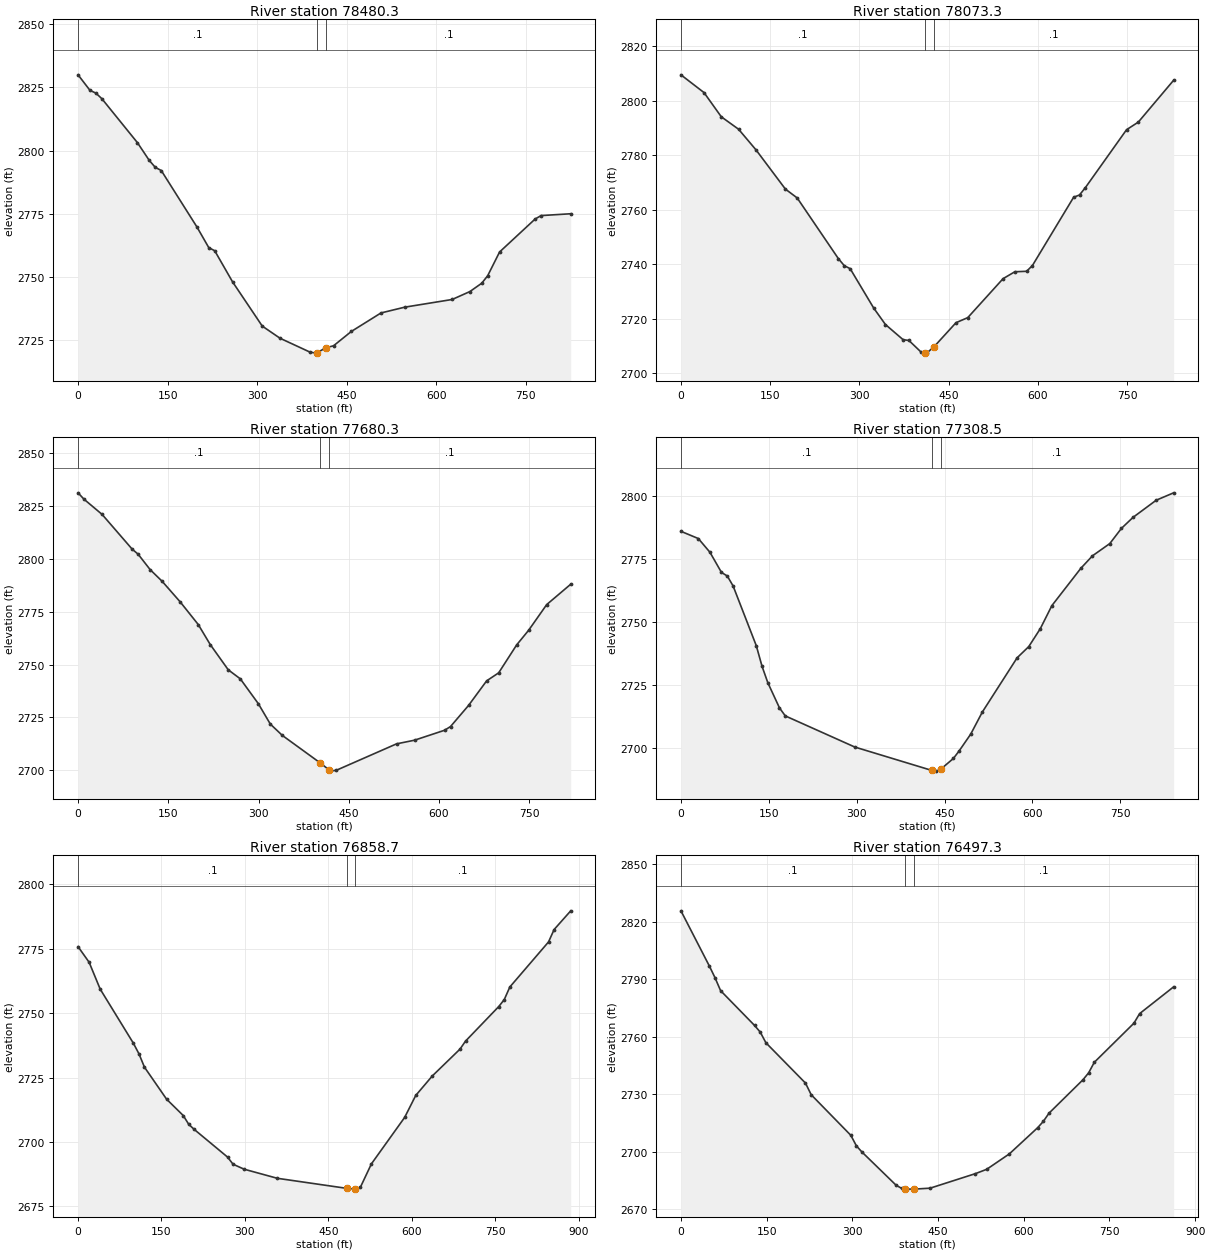
Type RM Length L Ch R = 1 ,78480.3 ,407.5,406.9,402.8
XS GIS Cut Line= 3
     1951300.222      247262.944     1951401.032      246867.463
     1951567.091      246484.645
#Sta/Elev= 30
       0 2829.92    19.9 2823.81    29.9 2822.68    39.8 2820.51    99.5  2803.1
   119.4 2796.06   129.4 2793.35   139.4  2792.1   199.1 2769.81     219 2761.62
     229 2760.38   258.8 2748.11   308.6 2730.61   338.4  2725.8   388.2 2720.36
   398.2 2719.92   400.6 2720.15   415.6 2722.06     428 2722.82   457.8 2728.48
   507.5  2735.8   547.2 2738.08   626.7 2741.12   656.5 2744.26   676.4 2747.57
   686.3 2750.53   706.2  2759.9   765.8 2772.94   775.7 2774.28   825.4 2775.01
#Mann= 3 , 0 , 0
       0      .1       0   400.6    .045       0   415.6      .1       0
Bank Sta=400.6,415.6
XS Rating Curve= 0 ,0
Exp/Cntr=0.3,0.1

Type RM Length L Ch R = 1 ,78073.3 ,378,392.9,407.9
XS GIS Cut Line= 3
     1951640.881      247394.358     1951711.184      247301.692
     1951872.277      246608.377
#Sta/Elev= 30
       0 2809.43    38.8 2802.92    67.8 2794.06    96.9 2789.49   126.2 2781.92
   175.6 2767.55   195.4 2764.31   264.6 2742.08   274.5  2739.5   284.4  2738.4
   323.9 2723.99   343.7 2717.93   373.4 2712.37   383.2 2712.08     403 2707.95
   409.9 2707.59   412.9 2707.44   424.9 2709.66   462.3 2718.59   482.1 2720.45
   541.4 2734.72   561.2 2737.26     581 2737.43   590.8 2739.55     660 2764.55
   669.9  2765.4   679.8  2768.1     749 2789.32   768.8 2792.11   828.1 2807.44
#Mann= 3 , 0 , 0
       0      .1       0   409.9    .045       0   424.9      .1       0
Bank Sta=409.9,424.9
XS Rating Curve= 0 ,0
Exp/Cntr=0.3,0.1

Type RM Length L Ch R = 1 ,77680.3 ,375.7,371.8,367.9
XS GIS Cut Line= 3
     1951766.301      247489.711     1952084.234      247231.624
     1952402.167      246973.537
#Sta/Elev= 30
       0 2831.25      10  2828.2      40 2821.03    89.9 2804.62    99.9  2802.2
   119.8 2794.93   139.8 2789.39   169.8 2779.65   199.8 2768.94   219.7 2759.49
   249.7 2747.51   269.7 2743.25   299.6 2731.53   319.6 2721.85   339.6 2716.47
     402 2703.58     417 2700.23   419.5 2699.58   429.5    2700   529.4 2712.48
   559.3 2714.21   609.3 2718.92   619.2 2720.68   649.2 2730.68   679.2 2742.29
   699.2 2746.08   729.1 2759.29   749.1 2766.25     779 2778.36     819 2788.01
#Mann= 3 , 0 , 0
       0      .1       0     402    .045       0     417      .1       0
Bank Sta=402,417
XS Rating Curve= 0 ,0
Exp/Cntr=0.3,0.1

Type RM Length L Ch R = 1 ,77308.5 ,433.9,449.6,465.3
XS GIS Cut Line= 2
     1952089.146      247773.588     1952641.226      247139.335
#Sta/Elev= 30
       0 2785.89    29.7 2783.02    49.5 2777.58    69.2 2769.58    79.1 2768.16
      89 2764.23   128.6 2740.52   138.5 2732.28   148.4 2725.77   168.2 2715.83
   178.1 2712.66   296.8  2700.3   428.5 2691.01   435.3 2690.75   443.5 2691.52
     465 2695.78   474.8 2698.76   494.6 2705.43   514.4 2714.19   573.8 2735.72
   593.6 2740.14   613.3 2747.24   633.1 2756.41   682.6 2771.23   702.4 2776.17
     732 2781.03   751.8 2787.05   771.6 2791.42   811.2 2798.23   840.9 2801.16
#Mann= 3 , 0 , 0
       0      .1       0   428.5    .045       0   443.5      .1       0
Bank Sta=428.5,443.5
XS Rating Curve= 0 ,0
Exp/Cntr=0.3,0.1

Type RM Length L Ch R = 1 ,76858.7 ,354.4,361.4,368.5
XS GIS Cut Line= 2
     1952148.144      247863.365     1953022.561      247722.148
#Sta/Elev= 30
       0 2775.77    19.9 2769.72    39.8  2759.3    99.5  2738.3   109.5  2734.2
   119.4 2729.02   159.2  2716.6   189.1 2710.27     199 2706.85     209 2704.85
   268.7 2694.16   278.7 2691.37   298.6 2689.44   358.3 2685.91   483.1 2682.01
   497.6 2681.71   498.1 2681.75   507.6 2682.43   527.5 2691.53   587.2 2709.53
   607.1 2718.04   636.9 2725.61   686.7 2736.02   696.6 2739.12   756.4 2752.54
   766.3 2755.24   776.3 2760.12   845.9 2777.61   855.9 2782.41   885.8 2789.67
#Mann= 3 , 0 , 0
       0      .1       0   483.1    .045       0   498.1      .1       0
Bank Sta=483.1,498.1
XS Rating Curve= 0 ,0
Exp/Cntr=0.3,0.1

Type RM Length L Ch R = 1 ,76497.3 ,431.7,416.9,402
XS GIS Cut Line= 2
     1952116.982      248059.831     1952973.314      248160.953
#Sta/Elev= 30
       0 2825.76    49.6 2797.01    59.5 2790.91    69.4 2784.07   128.8 2765.91
   138.8 2762.42   148.7 2756.85     218 2735.78     228  2729.7   297.3 2708.52
   307.2 2702.95   317.2 2699.67   376.6 2682.44   386.5 2680.76   392.9 2680.53
   396.4  2680.4   407.9  2680.4   436.1  2680.9   515.4 2688.49   535.2 2690.76
   574.8 2698.81   624.4  2712.5   634.3  2715.8   644.2 2720.07   703.7 2737.54
   713.6 2741.16   723.5 2746.65   792.9 2767.09   802.8 2772.07   862.3 2786.05
#Mann= 3 , 0 , 0
       0      .1       0   392.9    .045       0   407.9      .1       0
Bank Sta=392.9,407.9
XS Rating Curve= 0 ,0
Exp/Cntr=0.3,0.1

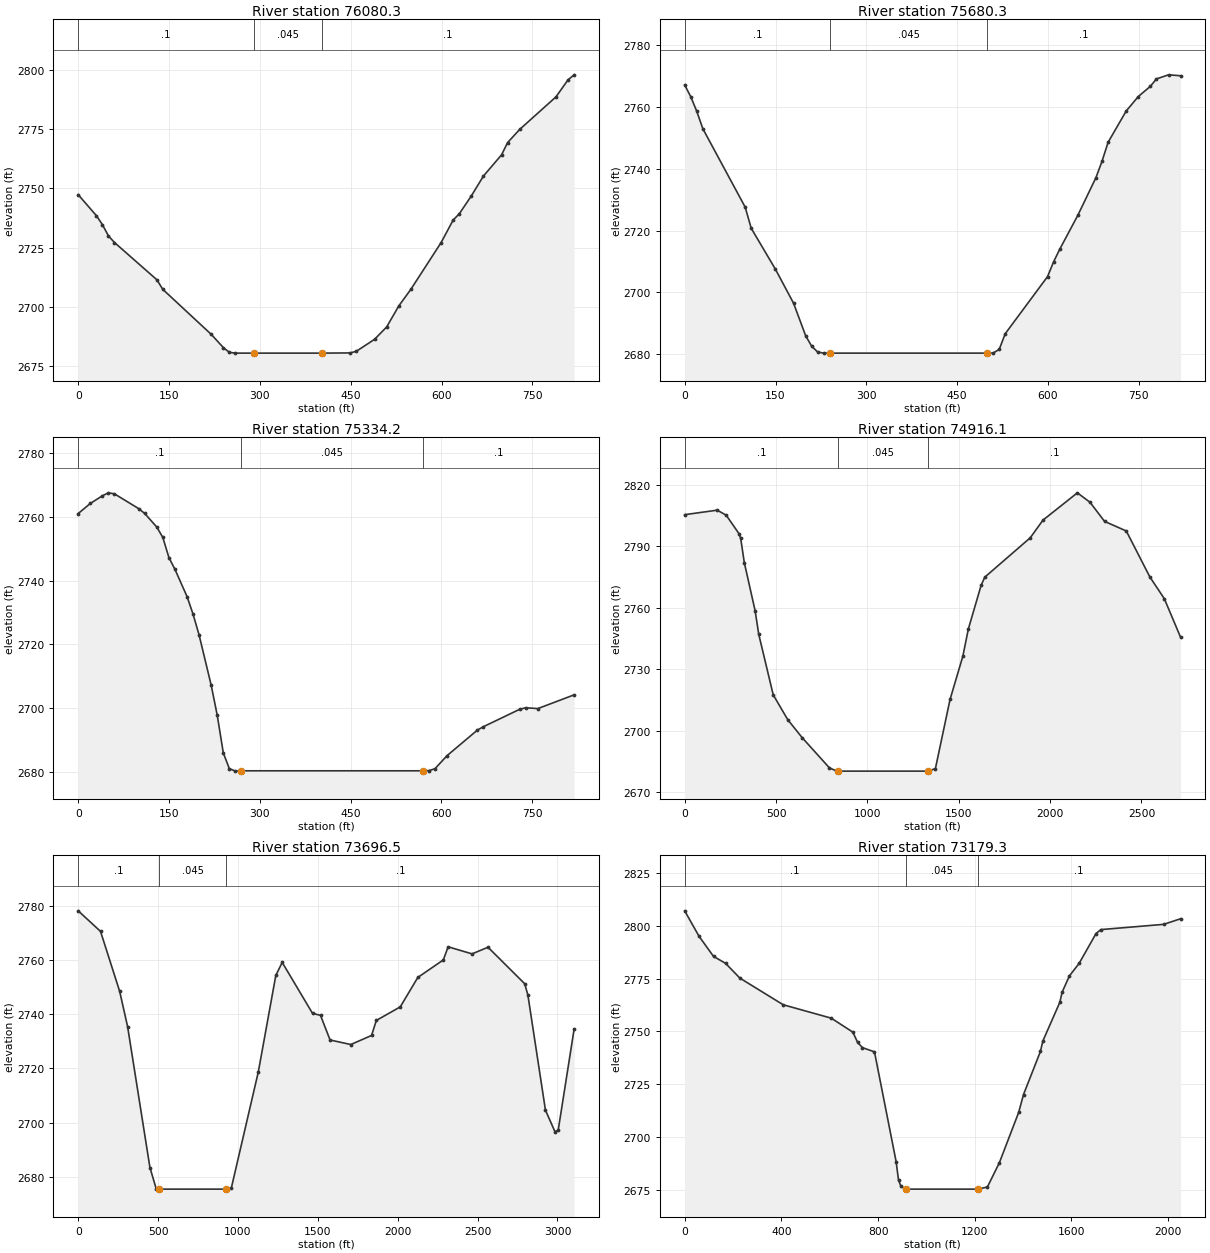
Type RM Length L Ch R = 1 ,76080.3 ,394.6,400,405.4
XS GIS Cut Line= 3
     1952302.085      248682.929     1952654.375      248474.165
     1953006.664      248265.401
#Sta/Elev= 30
       0  2747.3      30 2738.46      40 2734.65    49.9 2729.91    59.9 2727.11
   129.8  2711.4   139.8  2707.3   219.7 2688.32   239.7 2682.73   249.7 2680.71
   259.7  2680.4   289.6  2680.4     402  2680.4   449.4 2680.49   459.4  2681.2
   489.4 2686.23   509.4 2691.46   529.4 2700.33   549.3 2707.33   599.3 2727.09
   619.2 2736.61   629.2  2739.2   649.2 2746.79   669.2 2755.18   699.2 2764.16
   709.1  2769.3   729.1 2774.88     789 2788.62     809 2795.84     819 2797.92
#Mann= 3 , 0 , 0
       0      .1       0   289.6    .045       0     402      .1       0
Bank Sta=289.6,402
XS Rating Curve= 0 ,0
Exp/Cntr=0.3,0.1

Type RM Length L Ch R = 1 ,75680.3 ,349.5,346.1,342.6
XS GIS Cut Line= 3
     1952407.699      248963.952     1952799.704      248845.534
     1953191.708      248727.116
#Sta/Elev= 30
       0 2767.08      10 2763.29      20 2758.54      30 2752.93    99.9 2727.59
   109.9 2720.75   149.8 2707.54   179.8 2696.54   199.8 2686.01   209.7 2682.63
   219.7 2680.75   229.7  2680.4   239.7  2680.4   499.4  2680.4   509.4 2680.43
   519.4  2681.6   529.4 2686.69   599.3 2705.15   609.3 2709.93   619.2 2713.92
   649.2 2724.93   679.2 2737.13   689.2  2742.4   699.2 2748.53   729.1 2758.65
   749.1 2763.33   769.1 2766.65     779 2769.02     799 2770.35     819 2770.05
#Mann= 3 , 0 , 0
       0      .1       0   239.7    .045       0   499.4      .1       0
Bank Sta=239.7,499.4
XS Rating Curve= 0 ,0
Exp/Cntr=0.3,0.1

Type RM Length L Ch R = 1 ,75334.2 ,417.5,417.8,417.9
XS GIS Cut Line= 3
     1952538.417      249348.709     1952908.931      249174.479
     1953278.042      248996.285
#Sta/Elev= 30
       0 2760.99      20 2764.15    39.9 2766.55    49.9 2767.48    59.9 2767.16
    99.9 2762.53   109.8 2761.03   129.8 2756.75   139.8  2753.5   149.8 2747.22
   159.8 2743.51   179.8 2734.98   189.7 2729.49   199.7 2722.94   219.7  2707.2
   229.7 2697.77   239.7    2686   249.6  2681.1   259.6  2680.3   269.6  2680.4
   569.4  2680.4   579.4 2680.45   589.4 2681.06   609.4 2685.16   659.4 2693.15
   669.4 2694.22   729.3 2699.67   739.3 2700.15   759.3 2699.89   819.3  2704.2
#Mann= 3 , 0 , 0
       0      .1       0   269.6    .045       0   569.4      .1       0
Bank Sta=269.6,569.4
XS Rating Curve= 0 ,0
Exp/Cntr=0.3,0.1

Type RM Length L Ch R = 1 ,74916.1 ,1200.7,1218.8,1231.4
XS GIS Cut Line= 4
     1952118.403      249742.377     1952842.856       249639.86
     1953768.045      249185.161     1954547.674      248639.371
#Sta/Elev= 30
       0 2805.51     178 2807.71   227.4 2805.24   296.6 2796.32   306.5 2793.93
   326.3 2782.15   385.6 2758.59   405.4 2747.12   484.5 2717.63   563.6 2705.57
   642.7 2696.76   791.7 2682.03   831.8  2680.4   841.8  2680.4  1332.2  2680.4
  1372.2 2681.64  1452.3 2715.36  1522.4 2736.46  1552.4  2749.7  1622.4 2771.05
  1642.4 2775.02  1891.4 2794.25  1960.8 2802.84  2149.2 2816.17  2218.6 2811.54
  2297.9 2802.24  2416.8 2797.56  2545.7 2775.16    2625 2764.52  2714.2 2745.66
#Mann= 3 , 0 , 0
       0      .1       0   841.8    .045       0  1332.2      .1       0
Bank Sta=841.8,1332.2
XS Rating Curve= 0 ,0
Exp/Cntr=0.3,0.1

Type RM Length L Ch R = 1 ,73696.5 ,526.5,517,507.4
XS GIS Cut Line= 3
     1952360.647      250124.727     1953612.112      250243.191
     1955307.058      249508.107
#Sta/Elev= 30
       0 2778.08   139.7  2770.5   259.4 2748.42   309.3 2735.36     449 2683.45
   488.9  2675.5   508.8  2675.5   927.8  2675.5   957.8 2675.74  1127.4 2718.71
  1237.1  2754.3    1277 2759.06  1466.8 2740.28  1516.7 2739.56  1576.6 2730.47
  1706.4  2728.8  1836.3 2732.14  1866.2 2737.68    2016 2742.68  2125.9 2753.53
  2285.7 2759.99  2315.6 2764.82  2465.4 2762.21  2565.3 2764.66    2795  2751.2
  2814.9 2747.03  2924.8 2704.62  2984.7 2696.62  3004.7 2697.22  3104.5 2734.56
#Mann= 3 , 0 , 0
       0      .1       0   508.8    .045       0   927.8      .1       0
Bank Sta=508.8,927.8
XS Rating Curve= 0 ,0
Exp/Cntr=0.3,0.1

Type RM Length L Ch R = 1 ,73179.3 ,449.5,449.2,449
XS GIS Cut Line= 3
     1952167.069      251026.593      1953446.48       250590.75
     1954138.908      250488.819
#Sta/Elev= 30
       0 2806.99    59.6 2794.93   119.3 2785.46     169  2782.2   228.6 2775.18
   407.5 2762.61   606.2 2756.28   695.7 2749.67   715.6 2744.78   735.4 2742.35
   785.1 2740.36   874.6 2688.54   884.5 2679.81   894.4 2676.89   914.3  2675.5
  1212.5  2675.5  1252.2 2676.49  1301.9 2688.02  1381.6 2711.76  1401.6 2720.19
  1471.6 2740.56  1481.6 2745.47  1551.6  2763.7  1561.6 2768.62  1591.6 2776.27
  1631.6 2782.15  1701.6 2796.26  1721.6 2798.12  1981.5  2800.6  2051.5 2803.26
#Mann= 3 , 0 , 0
       0      .1       0   914.3    .045       0  1212.5      .1       0
Bank Sta=914.3,1212.5
XS Rating Curve= 0 ,0
Exp/Cntr=0.3,0.1

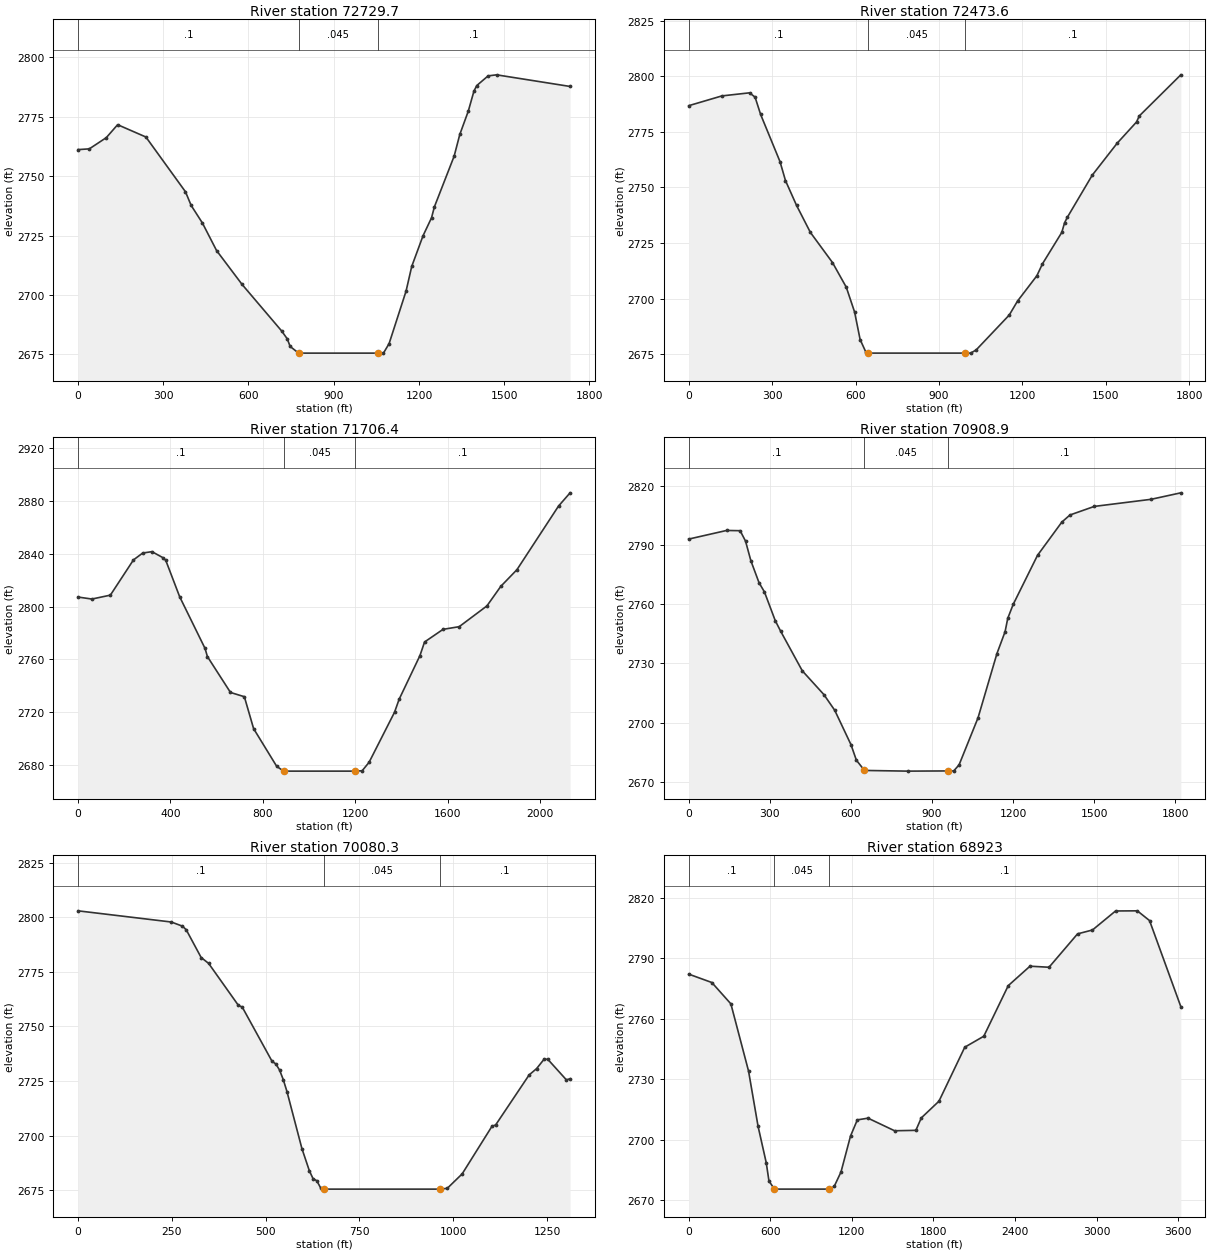
Type RM Length L Ch R = 1 ,72729.7 ,244.3,255.5,266.7
XS GIS Cut Line= 2
     1952469.347      251399.169      1954103.76      250826.246
#Sta/Elev= 30
       0 2761.19    39.8 2761.51    99.5 2766.23   139.4 2771.68   238.9  2766.5
   378.2 2743.44   398.1 2737.71     438 2730.25   487.7 2718.68   577.3 2704.44
   716.7 2684.83   736.6 2681.48   746.5 2678.33   776.4  2675.5  1055.1  2675.5
    1075  2675.5  1094.9 2679.52  1154.6 2701.62  1174.5    2712  1214.3 2724.91
  1244.2 2732.48  1254.2 2737.06  1323.8 2758.43  1343.7 2767.57  1373.6 2777.39
  1393.5 2785.82  1403.4 2788.16  1443.3 2792.23  1473.1 2792.68  1731.9 2787.78
#Mann= 3 , 0 , 0
       0      .1       0   776.4    .045       0  1055.1      .1       0
Bank Sta=776.4,1055.1
XS Rating Curve= 0 ,0
Exp/Cntr=0.3,0.1

Type RM Length L Ch R = 1 ,72473.6 ,775.9,767.2,758.6
XS GIS Cut Line= 4
     1952525.585      251529.219     1953069.573      251309.358
     1953717.124      251413.229     1954230.295      251536.249
#Sta/Elev= 30
       0 2786.74   119.3 2791.13   218.8 2792.52   238.7 2790.57   258.6  2782.8
   328.2 2761.63   348.1 2753.05   387.8 2741.93   437.6 2729.77   517.1 2716.23
   566.8 2705.12   596.7 2693.96   616.6 2681.59   636.4 2676.17   646.4  2675.5
   994.2  2675.5    1014 2675.49  1033.9 2676.91  1153.1 2692.62    1183 2698.92
  1252.5 2710.28  1272.4  2715.6  1342.1 2729.76  1352.1 2734.08    1362 2736.54
  1451.7  2755.5  1541.3 2769.86    1611 2779.41  1620.9 2782.12  1770.3 2800.61
#Mann= 3 , 0 , 0
       0      .1       0   646.4    .045       0   994.2      .1       0
Bank Sta=646.4,994.2
XS Rating Curve= 0 ,0
Exp/Cntr=0.3,0.1

Type RM Length L Ch R = 1 ,71706.4 ,779.6,796.9,814.2
XS GIS Cut Line= 2
     1952465.833       252288.43     1954550.147      251852.587
#Sta/Elev= 30
       0 2807.21      60  2805.7     140 2808.65   239.9  2835.3   279.9 2840.51
   319.9 2841.55   369.9 2836.76   379.9 2834.89   439.9 2807.42   549.8 2768.28
   559.8  2762.2   659.8 2735.02   719.8  2731.8   759.8 2707.66   859.8 2679.12
   889.8  2675.5  1199.7  2675.5  1229.6 2675.78  1259.6  2682.2  1369.6 2720.02
  1389.6 2729.88  1479.6 2762.89  1499.6  2773.2  1579.6 2782.77  1649.5 2784.79
  1769.5  2800.5  1829.5 2815.29  1899.5 2827.93  2079.4 2876.05  2129.4 2886.06
#Mann= 3 , 0 , 0
       0      .1       0   889.8    .045       0  1199.7      .1       0
Bank Sta=889.8,1199.7
XS Rating Curve= 0 ,0
Exp/Cntr=0.3,0.1

Type RM Length L Ch R = 1 ,70908.9 ,811.8,828.3,844.7
XS GIS Cut Line= 2
     1952743.507      252436.054     1954286.532      253402.642
#Sta/Elev= 30
       0 2793.06   140.1 2797.43   190.1 2797.31   210.1 2792.05   230.1 2781.99
   260.1 2770.94   280.1 2766.27   320.1 2751.71   340.1 2746.35   420.2 2726.26
   500.2  2714.2   540.2 2706.25   600.3 2688.84   620.3 2680.95   650.3 2675.75
   809.7  2675.4   960.4  2675.5   980.4 2675.49  1000.4  2678.6  1070.5 2702.45
  1140.5 2735.04  1170.5 2746.08  1180.5  2752.9  1200.5 2759.92  1290.6 2784.83
  1380.6 2801.68  1410.6 2805.27  1500.6 2809.62  1710.7 2813.22  1820.8 2816.51
#Mann= 3 , 0 , 0
       0      .1       0   650.3    .045       0   960.4      .1       0
Bank Sta=650.3,960.4
XS Rating Curve= 0 ,0
Exp/Cntr=0.3,0.1

Type RM Length L Ch R = 1 ,70080.3 ,1181.9,1156.2,1130.7
XS GIS Cut Line= 3
     1952486.922      252446.599     1952720.167      253248.632
     1952855.983       253704.92
#Sta/Elev= 30
       0 2802.92   248.6  2797.8   278.4 2795.89   288.4 2794.24   328.1 2781.55
     348 2778.86   427.6 2759.58   437.5 2758.89   517.1 2734.02     527 2732.84
     537 2730.06   546.9 2725.67   556.8 2720.18   596.6  2694.1   616.5 2683.89
   626.4 2680.27   636.4 2679.33   646.3 2676.12   656.3  2675.5   964.2  2675.5
     984 2675.86  1023.7 2682.48    1103 2704.24    1113 2704.91  1202.2  2727.8
  1222.1 2730.68  1241.9 2734.97  1251.8 2734.96  1301.4 2725.53  1311.3 2726.04
#Mann= 3 , 0 , 0
       0      .1       0   656.3    .045       0   964.2      .1       0
Bank Sta=656.3,964.2
XS Rating Curve= 0 ,0
Exp/Cntr=0.3,0.1

Type RM Length L Ch R = 1 ,68923   ,2120.5,2109.6,2097.6
XS GIS Cut Line= 4
     1951063.402      253687.346     1952318.208      253884.178
      1952652.12      253701.405     1954605.691      253947.077
#Sta/Elev= 30
       0 2782.13     170 2777.97     310 2767.38     440 2734.04   510.1 2706.61
   570.1  2688.6   590.1 2679.55   630.1  2675.5  1030.1  2675.5  1040.1 2675.49
  1070.1 2676.84  1120.1 2684.01  1190.1 2701.82  1240.2 2709.84    1319 2710.69
  1514.2 2704.44  1670.8 2704.65  1710.8 2710.82  1840.7  2719.1  2030.6 2745.89
  2170.5 2751.33  2350.4 2776.42  2510.4 2786.07  2650.3 2785.54  2860.2  2802.1
  2970.1 2804.03    3140 2813.46  3299.9 2813.53  3389.9 2808.68  3619.8 2766.03
#Mann= 3 , 0 , 0
       0      .1       0   630.1    .045       0  1030.1      .1       0
Bank Sta=630.1,1030.1
XS Rating Curve= 0 ,0
Exp/Cntr=0.3,0.1

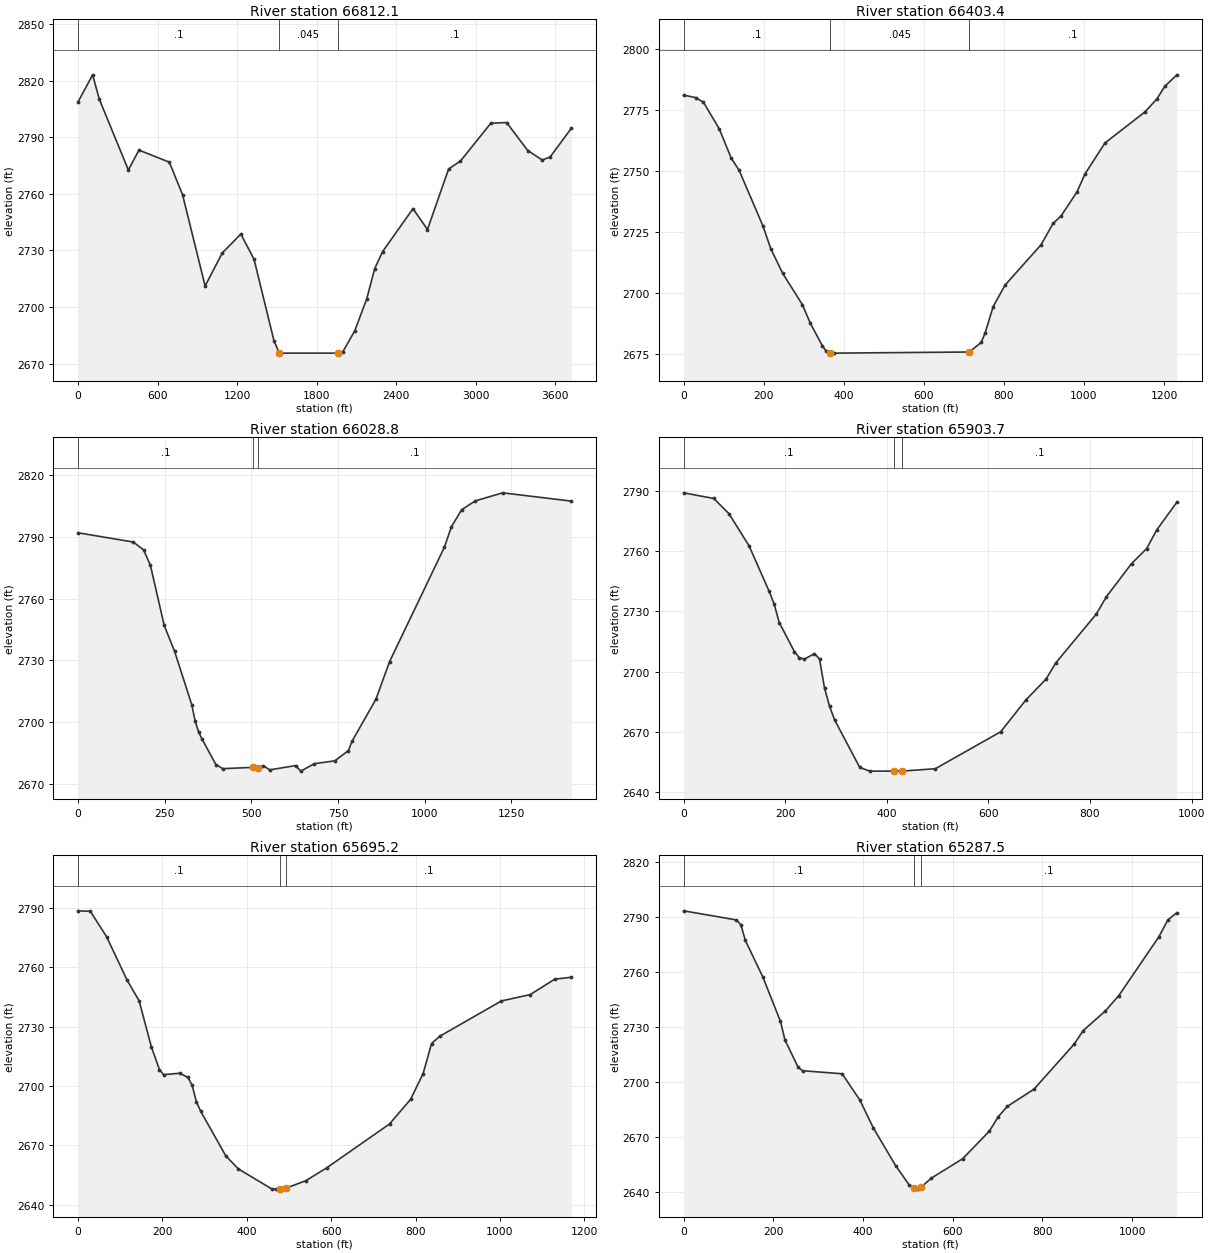
Type RM Length L Ch R = 1 ,66812.1 ,412.3,408.5,404.7
XS GIS Cut Line= 4
     1951010.679      255437.749     1952338.492      255408.007
     1953170.489      254991.111     1954623.959      254819.132
#Sta/Elev= 30
       0 2808.71   109.8 2823.04   159.8  2810.2   379.5 2772.56   459.4 2783.13
     689 2776.72   788.9  2759.4   958.7 2711.09  1088.5 2728.61  1228.3 2738.65
  1328.2 2725.22  1478.2 2682.12  1518.3 2675.54  1528.3  2675.5  1958.6  2675.5
  1998.6 2676.29  2088.6 2687.39  2178.7 2704.27  2238.7 2720.32  2298.6 2729.35
  2527.6 2752.08  2637.1 2741.04  2796.4 2773.13    2886 2777.34    3115 2797.39
  3234.5 2797.74  3393.8  2782.9  3503.3 2777.88    3563  2779.5  3722.4  2794.7
#Mann= 3 , 0 , 0
       0      .1       0  1518.3    .045       0  1958.6      .1       0
Bank Sta=1518.3,1958.6
XS Rating Curve= 0 ,0
Exp/Cntr=0.3,0.1

Type RM Length L Ch R = 1 ,66403.4 ,371.6,374,374.8
XS GIS Cut Line= 3
     1952539.845       255836.76     1953012.982      255494.589
     1953541.034      255118.428
#Sta/Elev= 30
       0 2781.06    29.7 2780.08    49.5 2778.17    89.1 2767.26   118.8 2755.34
   138.6 2750.34   197.9 2727.64   217.7 2718.26   247.4 2708.18   296.9 2695.29
   316.7 2687.67   346.4 2678.57   356.3  2676.3   366.2 2675.57   376.1  2675.5
   713.6 2675.96   743.5 2679.87   753.5 2683.88   773.4 2694.58   803.3 2703.38
   893.1 2719.87     923 2728.57     943 2731.64   982.9 2741.52  1002.8 2748.85
  1052.7  2761.5  1152.4 2774.18  1182.4 2779.52  1202.3 2784.72  1232.2 2789.38
#Mann= 3 , 0 , 0
       0      .1       0   366.2    .045       0   713.6      .1       0
Bank Sta=366.2,713.6
XS Rating Curve= 0 ,0
Exp/Cntr=0.3,0.1

Type RM Length L Ch R = 1 ,66028.8 ,124.6,125,126.9
XS GIS Cut Line= 6
     1952666.544      256140.421     1952987.908      255941.858
     1953147.559      255850.325     1953218.361      255811.432
     1953292.055      255785.067     1953903.366      255439.316
#Sta/Elev= 30
       0 2792.08   159.1 2787.61   188.9 2783.82   208.8 2776.23   248.5 2747.05
   278.4 2734.48     328 2708.49     338 2700.45   347.9 2695.12   357.9 2691.71
   397.6 2679.34   417.5 2677.35   504.2 2677.97   519.2 2677.71   534.5 2678.84
   552.8 2676.76   627.5 2678.84   642.7 2676.15   681.8 2679.77   740.8 2681.15
   780.3 2686.16   790.2 2690.57   859.5 2711.12     899 2729.45  1057.3 2785.16
  1077.1 2794.94  1106.8 2803.29  1146.3 2807.61  1225.5 2811.53  1423.3  2807.5
#Mann= 3 , 0 , 0
       0      .1       0   504.2    .045       0   519.2      .1       0
Bank Sta=504.2,519.2
XS Rating Curve= 0 ,0
Exp/Cntr=0.3,0.1

Type RM Length L Ch R = 1 ,65903.7 ,208.1,208.5,208.8
XS GIS Cut Line= 2
      1952788.71      256190.825     1953643.017      255729.499
#Sta/Elev= 30
       0 2789.14    59.4 2786.33    89.2 2778.75   128.8 2762.73   168.4 2740.03
   178.3 2733.58   188.2 2724.49     218 2710.01   227.9 2706.87   237.8 2706.24
   257.6 2708.96   267.5 2706.28   277.4 2691.76   287.3 2682.72   297.2 2675.93
   346.8  2652.2   366.6 2650.39   414.6  2650.4   429.6  2650.4   495.4 2651.58
   624.2 2670.02   673.7 2685.87   713.3 2696.24   733.1 2704.51   812.4 2728.72
   832.2 2737.32   881.7 2753.86   911.5 2761.34   931.3 2770.63   970.9 2784.45
#Mann= 3 , 0 , 0
       0      .1       0   414.6    .045       0   429.6      .1       0
Bank Sta=414.6,429.6
XS Rating Curve= 0 ,0
Exp/Cntr=0.3,0.1

Type RM Length L Ch R = 1 ,65695.2 ,383.3,407.7,432.1
XS GIS Cut Line= 4
     1952834.953      256244.982     1953095.406       256251.48
     1953607.066      255983.948     1953930.064      256057.553
#Sta/Elev= 30
       0 2788.61      29 2788.38    67.6 2775.51   115.8 2753.75   144.7 2743.09
   173.7 2719.86     193  2708.3   202.6 2705.78   241.2  2706.5   260.5 2704.35
   270.5 2700.37   280.4 2692.06   290.4 2687.39   350.1 2664.74     380 2658.13
   459.6 2647.95   469.6  2647.9   478.6  2648.1   493.6 2648.47   539.3  2652.1
     589 2658.61   738.4 2680.86   788.1 2693.25     818 2706.34   837.9 2721.51
   857.4  2725.2  1003.6 2743.05  1071.8 2746.26  1130.2 2754.08  1169.2 2755.02
#Mann= 3 , 0 , 0
       0      .1       0   478.6    .045       0   493.6      .1       0
Bank Sta=478.6,493.6
XS Rating Curve= 0 ,0
Exp/Cntr=0.3,0.1

Type RM Length L Ch R = 1 ,65287.5 ,407,407.2,407.3
XS GIS Cut Line= 3
     1952748.557      256251.267     1953085.581       256411.45
      1953701.11      256797.383
#Sta/Elev= 30
       0 2793.24   117.8 2788.26   127.7 2785.59   137.5  2777.2   176.8 2757.05
     216 2732.88   225.9 2722.88   255.3 2707.89   265.1 2706.04   353.5 2704.36
   393.1 2689.97   422.9 2674.86   472.7 2654.28   502.5 2643.88   513.8 2641.83
   522.4 2641.45   528.8 2642.38   552.3 2647.45     622 2657.99   681.7 2673.08
   701.6 2680.96   721.5 2686.53   781.2 2695.97   870.8 2720.54   890.7 2727.87
   940.4 2738.65   970.3    2747  1059.9 2779.18  1079.8 2788.33  1099.7 2792.17
#Mann= 3 , 0 , 0
       0      .1       0   513.8    .045       0   528.8      .1       0
Bank Sta=513.8,528.8
XS Rating Curve= 0 ,0
Exp/Cntr=0.3,0.1

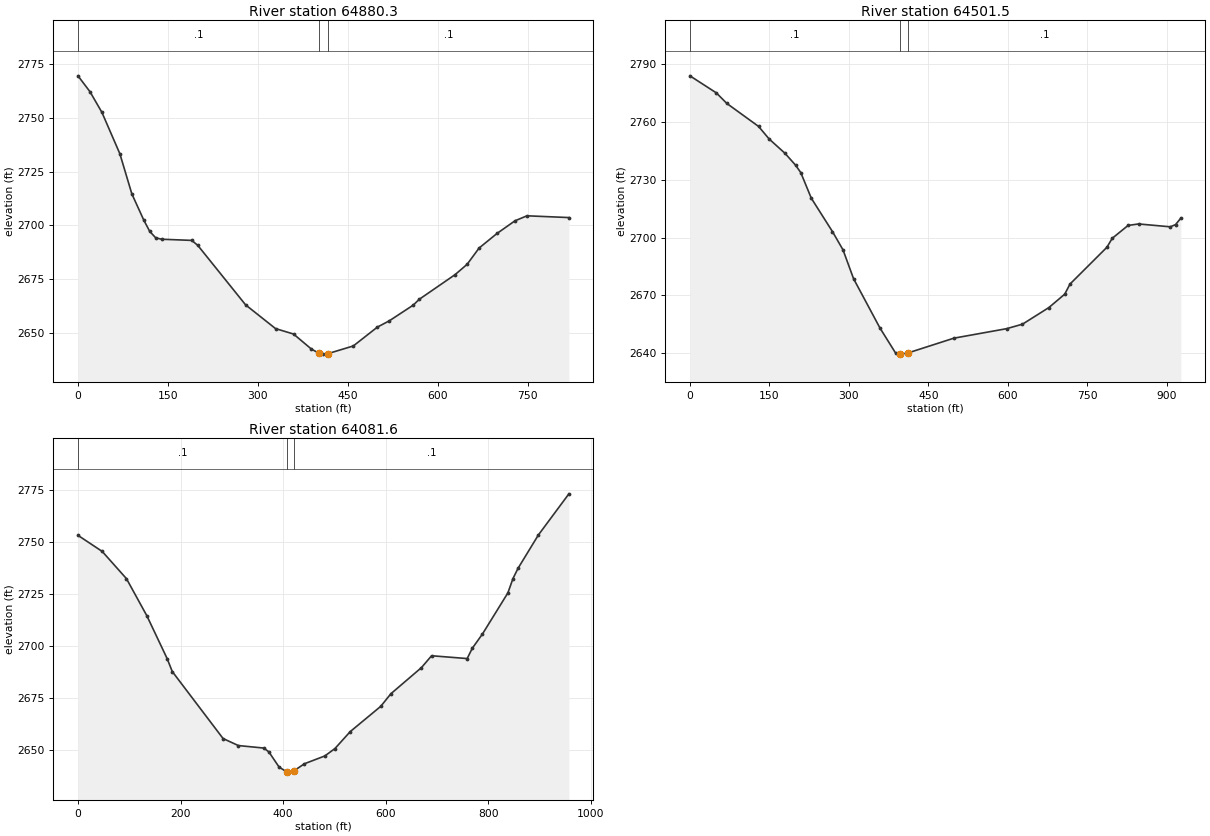
Type RM Length L Ch R = 1 ,64880.3 ,389.2,378.6,368.1
XS GIS Cut Line= 3
     1952641.764      256610.119     1952987.159      256830.102
     1953332.553      257050.086
#Sta/Elev= 30
       0 2769.68      20 2762.31      40 2752.64    69.9 2733.39    89.9  2714.7
   109.9 2702.44   119.8 2697.21   129.8 2694.22   139.8 2693.59   189.8 2693.05
   199.8 2690.76   279.7 2663.02   329.6 2651.98   359.6 2649.45   389.5 2642.43
     402 2640.53   409.5 2640.09     417 2640.32   459.4  2643.9   499.4 2652.66
   519.4  2655.6   559.3 2662.91   569.3 2665.61   629.2 2677.12   649.2 2681.91
   669.2  2689.5   699.2 2696.31   729.1 2702.18   749.1  2704.5     819 2703.68
#Mann= 3 , 0 , 0
       0      .1       0     402    .045       0     417      .1       0
Bank Sta=402,417
XS Rating Curve= 0 ,0
Exp/Cntr=0.3,0.1

Type RM Length L Ch R = 1 ,64501.5 ,417.3,419.8,422.3
XS GIS Cut Line= 2
     1952410.522      257121.842     1953332.049      257214.285
#Sta/Elev= 30
       0 2783.85    49.8 2775.01    69.7 2769.52   129.5 2757.62   149.4 2751.11
   179.3 2743.69   199.2 2737.56   209.1 2733.69     229 2720.38   268.9 2703.08
   288.8 2693.61   308.7 2678.66   358.5 2653.09   388.4 2639.93   396.1 2639.63
   398.3 2639.54   411.1 2640.13   497.9 2647.81   597.5 2652.74   627.4 2655.07
   677.2 2663.69   707.1 2670.63     717 2675.86   786.7 2694.96   796.7 2699.59
   826.6 2706.27   846.5 2707.04   906.2 2705.56   916.2  2706.7   926.2  2710.1
#Mann= 3 , 0 , 0
       0      .1       0   396.1    .045       0   411.1      .1       0
Bank Sta=396.1,411.1
XS Rating Curve= 0 ,0
Exp/Cntr=0.3,0.1

Type RM Length L Ch R = 1 ,64081.6 ,381.4,400.9,421.2
XS GIS Cut Line= 3
      1952455.53      257463.743     1952544.378      257496.206
     1953388.433      257675.611
#Sta/Elev= 30
       0 2753.08    47.3 2745.36    94.6 2732.29   134.3 2714.52   173.9 2693.96
   183.9 2687.75     283 2655.59   312.8 2652.22   362.4 2651.02   372.3 2649.19
   392.2 2641.92   406.9 2639.61     412 2639.47   421.9 2640.21   441.7 2643.49
   481.4 2647.22   501.2 2650.78     531 2658.91   590.5 2671.03   610.4  2677.1
   669.9 2689.62   689.7 2695.31   759.1 2693.96     769 2698.87   788.9 2705.74
   838.5 2725.47   848.4 2732.33   858.3 2737.27     898 2753.27   957.5    2773
#Mann= 3 , 0 , 0
       0      .1       0   406.9    .045       0   421.9      .1       0
Bank Sta=406.9,421.9
XS Rating Curve= 0 ,0
Exp/Cntr=0.3,0.1