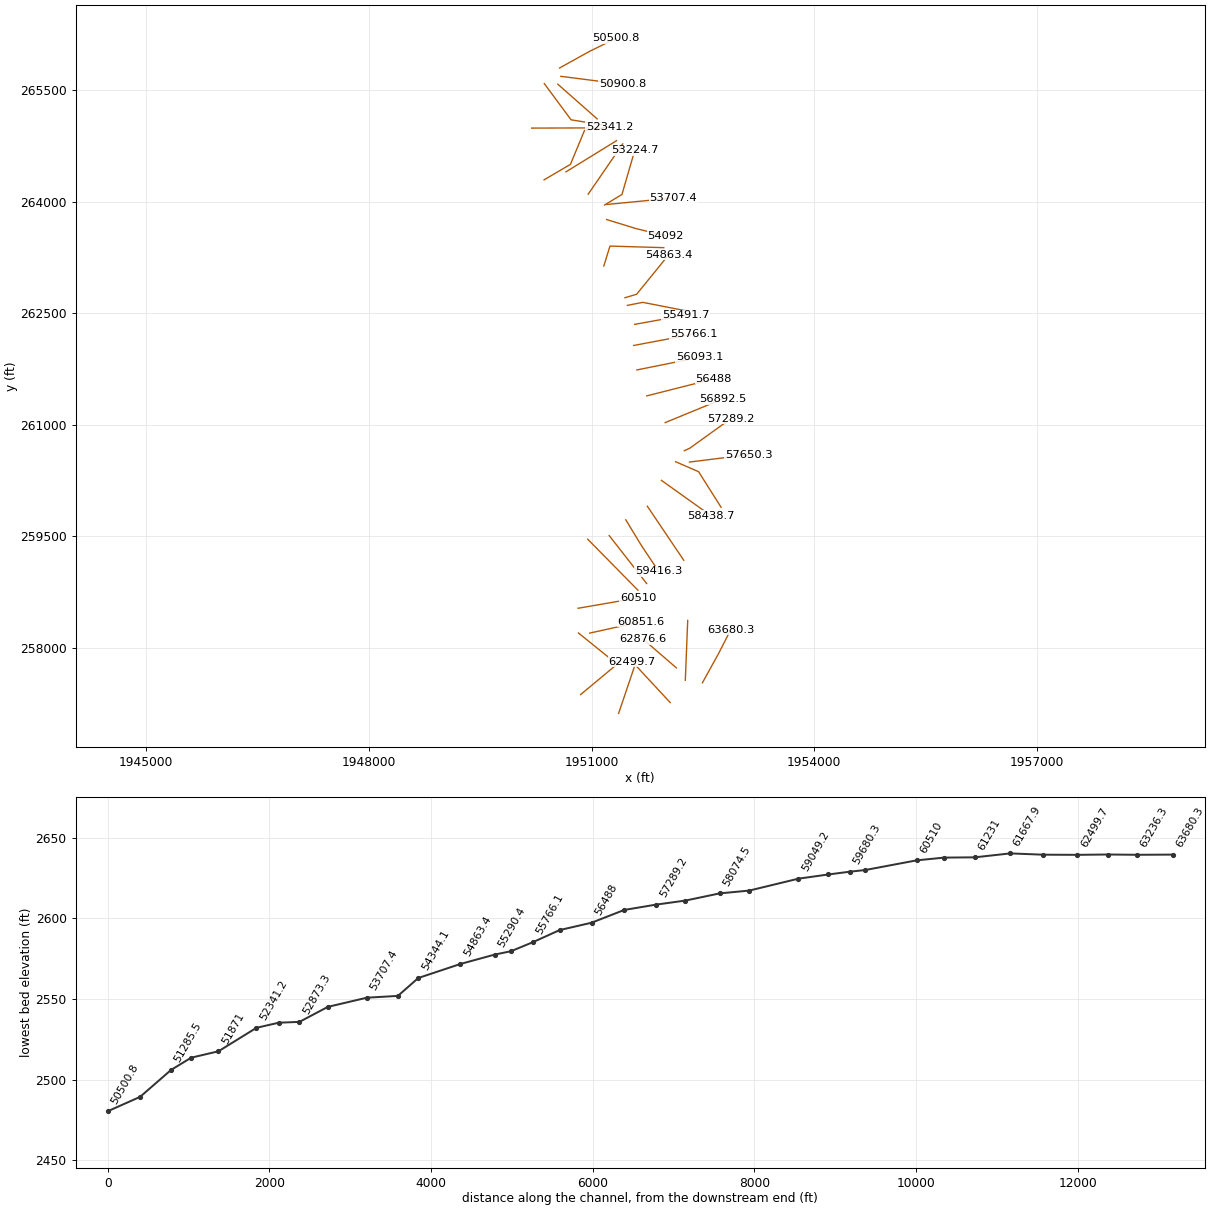
HEC-RAS study GldCrk.prj: GldCrk

--- GldCrk.g01 (geometry) --- (continued)

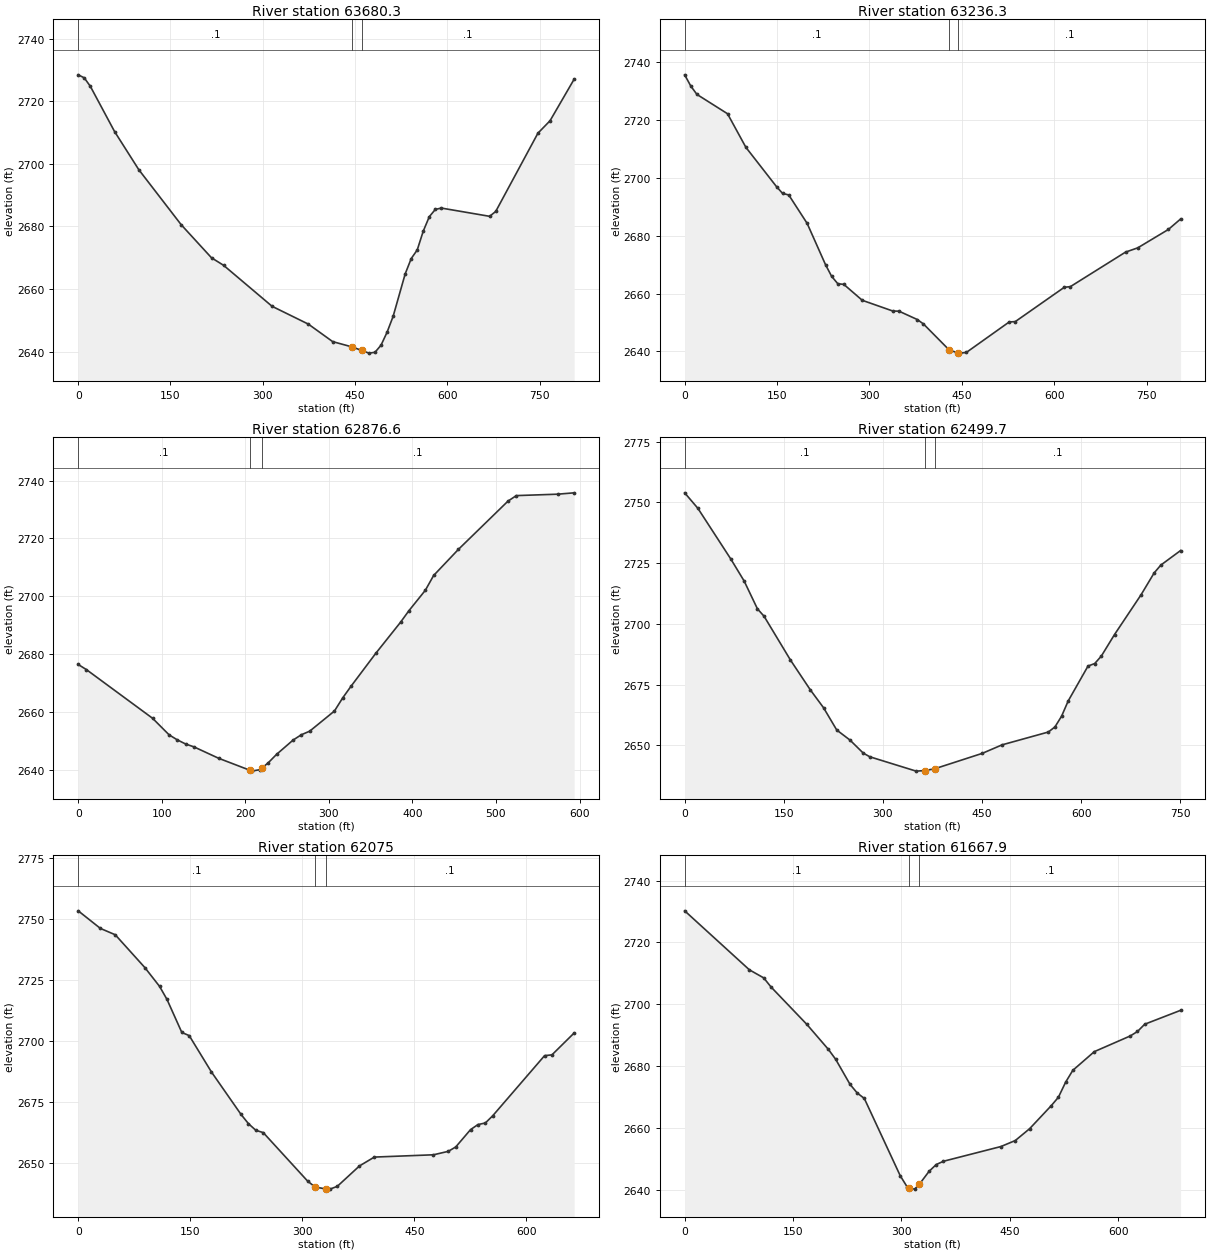
Type RM Length L Ch R = 1 ,63680.3 ,433.4,444,453.8
XS GIS Cut Line= 3
     1952493.119       257528.67     1952712.118        257925.3
     1952872.718      258239.919
#Sta/Elev= 30
       0 2728.47     9.8 2727.51    19.7  2724.8    59.1 2710.34    98.5 2698.14
   167.4 2680.55   216.7 2669.97   236.4 2667.56   315.2 2654.46   374.3 2648.75
   413.7 2643.17   445.6 2641.45   460.6 2640.37   472.7 2639.49   482.5 2639.76
   492.3 2642.02   502.1 2646.15     512 2651.25   531.6 2664.83   541.4 2669.72
   551.2 2672.49     561 2678.51   570.8 2683.11   580.6 2685.44   590.4 2685.87
   668.9 2683.23   678.8 2684.79   747.4 2709.81   767.1 2713.79   806.3 2727.08
#Mann= 3 , 0 , 0
       0      .1       0   445.6    .045       0   460.6      .1       0
Bank Sta=445.6,460.6
XS Rating Curve= 0 ,0
Exp/Cntr=0.3,0.1

Type RM Length L Ch R = 1 ,63236.3 ,339.2,359.7,380.2
XS GIS Cut Line= 2
     1952262.456      257562.842      1952294.92        258367.6
#Sta/Elev= 30
       0 2735.67     9.9 2731.79    19.9 2728.89    69.6  2722.2    99.4 2710.58
   149.2 2696.96   159.1 2694.62     169 2694.11   198.9 2684.26   228.7 2669.99
   238.6 2665.96   248.6  2663.4   258.5 2663.15   288.4 2657.65   338.1 2653.93
     348 2653.89   377.8 2650.99   387.8 2649.46   429.4  2640.5   444.4 2639.38
   447.4 2639.37   457.4  2639.6     527 2650.15   536.9 2650.28   616.5 2662.15
   626.4 2662.38   715.9 2674.32   735.8  2675.8   785.5 2682.16   805.4 2685.79
#Mann= 3 , 0 , 0
       0      .1       0   429.4    .045       0   444.4      .1       0
Bank Sta=429.4,444.4
XS Rating Curve= 0 ,0
Exp/Cntr=0.3,0.1

Type RM Length L Ch R = 1 ,62876.6 ,380.2,377.3,374.4
XS GIS Cut Line= 2
     1952142.853      257728.578     1951693.488      258116.434
#Sta/Elev= 30
       0 2676.42     9.9 2674.63      89 2657.82   108.8 2652.09   118.7 2650.34
   128.6 2648.93   138.5 2647.94   168.2 2643.98   205.2 2639.88   207.8 2639.55
   217.6 2640.07   220.2 2640.69   227.6 2642.47   237.4 2645.34   257.2 2650.29
   267.1 2652.13     277 2653.35   306.7 2660.33   316.6 2664.88   326.5 2668.88
   356.2 2680.29   385.8 2691.02   395.7 2694.96   415.5 2702.08   425.4 2707.18
   455.1 2716.22   514.4 2732.89   524.4  2734.8   573.8 2735.29   593.6 2735.76
#Mann= 3 , 0 , 0
       0      .1       0   205.2    .045       0   220.2      .1       0
Bank Sta=205.2,220.2
XS Rating Curve= 0 ,0
Exp/Cntr=0.3,0.1

Type RM Length L Ch R = 1 ,62499.7 ,448.5,424.2,399.9
XS GIS Cut Line= 2
     1952058.955      257262.465     1951548.255        257812.3
#Sta/Elev= 30
       0 2753.98      20 2747.59      70 2726.63      90 2717.64   110.1 2706.18
   120.1 2703.15   160.1 2685.08   190.1 2672.82   210.1 2665.46   230.1 2656.27
   250.1 2652.14   270.2 2646.76   280.2 2645.24   350.2 2639.34   363.9 2639.58
   378.9 2640.36   450.2 2646.65   480.3 2650.17   550.3 2655.45   560.3 2657.57
   570.3 2661.97   580.3 2668.25   610.3 2682.63   620.4 2683.65   630.4 2686.72
   650.4 2695.61   690.4 2711.92   710.4    2721   720.4  2724.2   750.4 2730.22
#Mann= 3 , 0 , 0
       0      .1       0   363.9    .045       0   378.9      .1       0
Bank Sta=363.9,378.9
XS Rating Curve= 0 ,0
Exp/Cntr=0.3,0.1

Type RM Length L Ch R = 1 ,62075   ,419.7,407.1,394.5
XS GIS Cut Line= 2
     1951364.331      257116.845     1951577.302      257745.664
#Sta/Elev= 30
       0 2753.47    29.7 2746.26    49.6 2743.66    89.2 2730.22     109 2722.47
   118.9 2717.14   138.7 2703.63   148.6 2702.34   178.4 2687.42     218 2670.03
   227.9 2666.26   237.8 2663.54   247.7  2662.6   307.2  2642.7     317 2640.34
     332 2639.46   336.9 2639.44   346.8 2640.57   376.5 2648.94   396.4 2652.57
   475.6 2653.51   495.4 2654.92   505.4 2656.72   525.2 2663.82   535.1 2665.89
     545 2666.54   554.9  2669.5   624.3 2694.13   634.2 2694.46   663.9 2703.42
#Mann= 3 , 0 , 0
       0      .1       0     317    .045       0     332      .1       0
Bank Sta=317,332
XS Rating Curve= 0 ,0
Exp/Cntr=0.3,0.1

Type RM Length L Ch R = 1 ,61667.9 ,468.1,437,405.9
XS GIS Cut Line= 2
      1950852.96       257370.29     1951380.811      257808.883
#Sta/Elev= 30
       0 2730.22    89.5 2711.15   109.4 2708.53   119.4 2705.62   169.1 2693.49
   198.9 2685.41   208.9 2682.23   228.8 2674.12   238.7 2671.33   248.6 2669.55
   298.4 2644.51   308.3 2640.79   309.9  2640.7   318.3 2640.23   324.9 2641.86
   338.2 2645.98   348.1 2648.18   358.1 2649.24   437.6    2654   457.5 2655.94
   477.4 2659.78   507.3 2667.22   517.2 2669.95   527.2 2674.82   537.1 2678.64
   566.9 2684.69   616.7 2689.77   626.6  2691.2   636.6 2693.55   686.3 2698.05
#Mann= 3 , 0 , 0
       0      .1       0   309.9    .045       0   324.9      .1       0
Bank Sta=309.9,324.9
XS Rating Curve= 0 ,0
Exp/Cntr=0.3,0.1

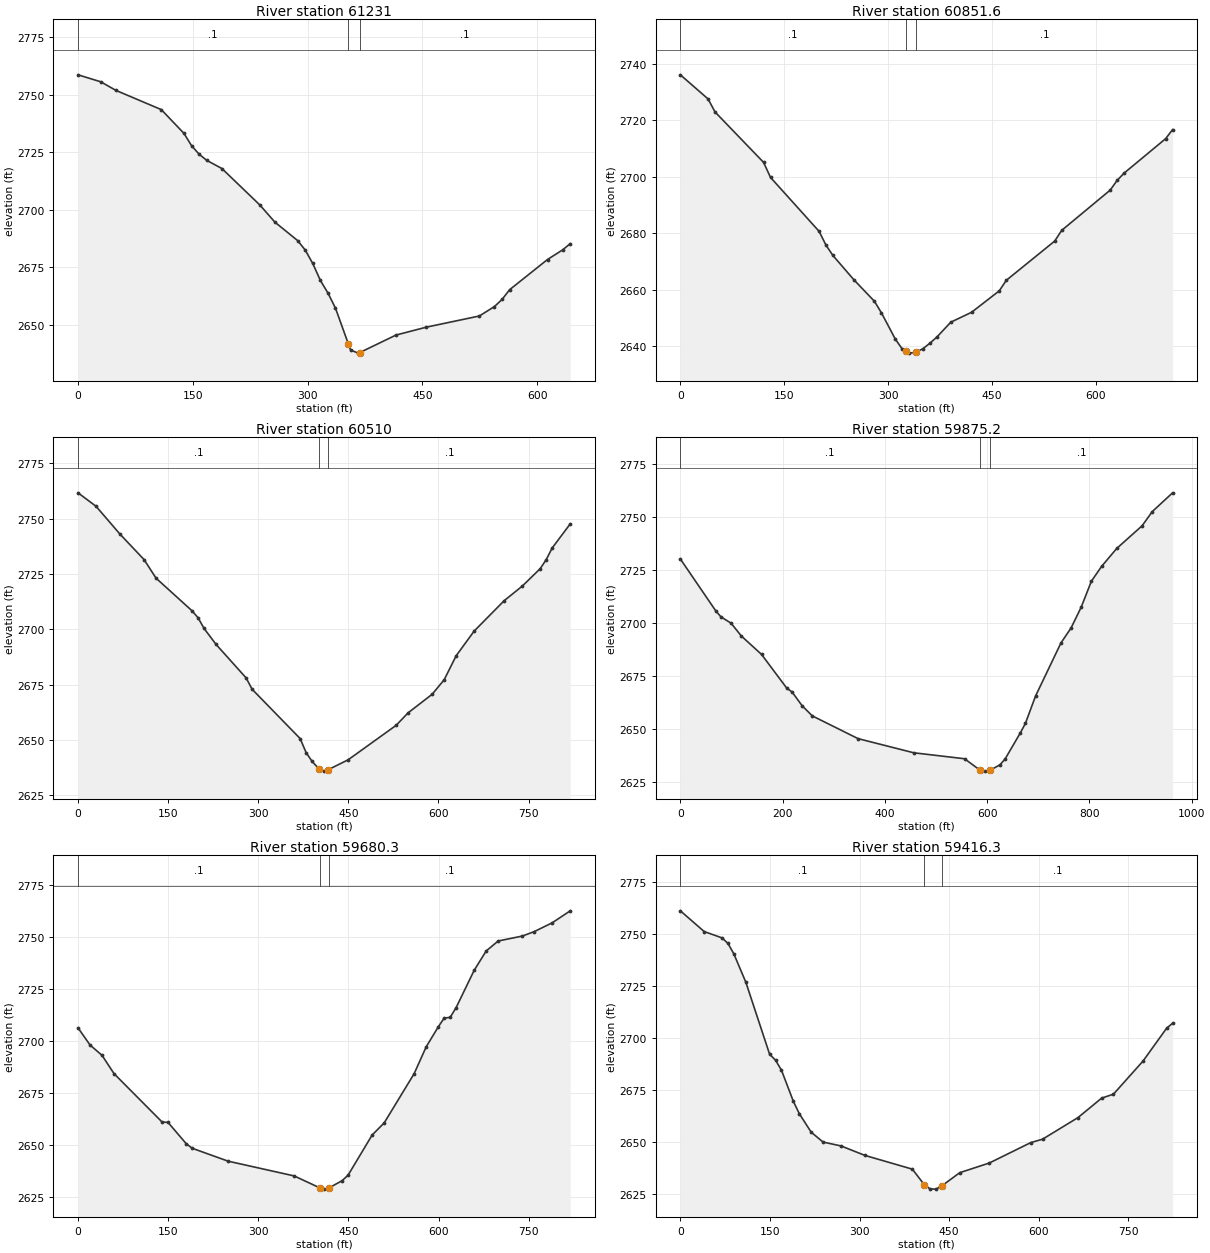
Type RM Length L Ch R = 1 ,61231   ,359,379.3,399.6
XS GIS Cut Line= 2
     1950823.362      258198.429     1951324.427      257795.214
#Sta/Elev= 30
       0 2758.57    29.7 2755.55    49.5 2751.82   108.8 2743.48   138.5 2733.14
   148.4 2727.79   158.3  2724.1   168.2 2721.46     188 2717.91   237.5 2702.12
   257.3 2694.63     287 2686.64   296.8 2682.57   306.7 2676.73   316.6 2669.42
   326.5 2663.92   336.4 2657.35   353.3 2641.76   356.2 2639.15   366.1  2637.8
   368.3 2638.07   415.6 2645.65   455.2 2649.07   524.4 2653.91   544.2 2658.01
   554.1  2661.1     564 2665.32   613.5 2678.43   633.3 2682.61   643.2 2685.31
#Mann= 3 , 0 , 0
       0      .1       0   353.3    .045       0   368.3      .1       0
Bank Sta=353.3,368.3
XS Rating Curve= 0 ,0
Exp/Cntr=0.3,0.1

Type RM Length L Ch R = 1 ,60851.6 ,342.6,341.5,340.5
XS GIS Cut Line= 2
     1950974.161      258196.738     1951667.858      258350.514
#Sta/Elev= 30
       0 2736.06      40 2727.52      50 2722.93   120.1 2705.09   130.1 2699.78
   200.2 2680.71   210.2 2675.82   220.2 2672.16   250.2 2663.64   280.2 2655.94
   290.2 2651.89   310.2 2642.61   320.2 2639.11   325.1 2638.38   330.2 2637.63
   340.1 2637.92   350.3 2639.23   360.3 2641.16   370.3 2643.33   390.3 2648.57
   420.3 2652.07   460.4 2659.68   470.4 2663.37   540.4 2677.28   550.4 2681.04
   620.5  2695.3   630.5 2698.74   640.5 2701.29   700.5 2713.49   710.5 2716.69
#Mann= 3 , 0 , 0
       0      .1       0   325.1    .045       0   340.1      .1       0
Bank Sta=325.1,340.1
XS Rating Curve= 0 ,0
Exp/Cntr=0.3,0.1

Type RM Length L Ch R = 1 ,60510   ,657.1,634.8,612.5
XS GIS Cut Line= 2
     1950817.956      258531.421     1951625.362      258670.484
#Sta/Elev= 30
       0 2761.67      30 2755.59    69.9 2742.98   109.9 2731.51   129.9  2723.1
   189.8 2708.36   199.8 2705.22   209.8 2700.39   229.8 2693.17   279.8 2678.04
   289.8 2672.91   369.7 2650.64   379.7 2644.28   389.7 2640.29   401.8  2636.7
   409.6 2635.92   416.8 2636.62   449.6 2641.03   529.5 2656.61   549.5 2662.28
   589.5 2670.65   609.5 2677.22   629.5 2688.08   659.4 2699.21   709.4 2712.95
   739.4 2719.51   769.3 2727.39   779.3 2731.48   789.3 2736.76   819.3 2747.64
#Mann= 3 , 0 , 0
       0      .1       0   401.8    .045       0   416.8      .1       0
Bank Sta=401.8,416.8
XS Rating Curve= 0 ,0
Exp/Cntr=0.3,0.1

Type RM Length L Ch R = 1 ,59875.2 ,197.5,194.9,192.3
XS GIS Cut Line= 2
     1950948.531      259460.259      1951624.24      258774.603
#Sta/Elev= 30
       0 2729.98    69.5 2705.42    79.4 2702.69    99.2 2699.71   119.1 2693.69
   158.8 2684.97   208.4 2668.96   218.3 2667.31   238.2 2660.75     258 2655.99
   347.4 2645.27   456.5 2638.58   555.8 2635.77   585.5 2630.49   595.5 2629.93
   605.4 2630.28   625.2 2632.94   635.2  2635.7   664.9 2647.96   674.8 2652.43
   694.7 2665.37   744.3 2690.37   764.2 2697.48     784  2707.3   803.9 2719.52
   823.7 2726.45   853.5 2734.98   903.1 2745.66     923 2752.36   962.7  2761.2
#Mann= 3 , 0 , 0
       0      .1       0   585.5    .045       0   605.4      .1       0
Bank Sta=585.5,605.4
XS Rating Curve= 0 ,0
Exp/Cntr=0.3,0.1

Type RM Length L Ch R = 1 ,59680.3 ,267.1,264.1,262.1
XS GIS Cut Line= 3
     1951237.395       259509.49     1951489.661      259186.919
     1951741.928      258864.348
#Sta/Elev= 30
       0 2706.39      20 2698.14      40 2693.15    59.9 2684.37   139.8 2661.15
   149.8 2660.93   179.8 2650.78   189.8 2648.53   249.7 2642.31   359.6 2635.22
     402 2629.52   409.5 2628.87     417 2629.36   439.5 2632.95   449.4  2635.6
   489.4 2654.88   509.4 2660.69   559.3 2684.37   579.3 2697.25   599.3 2706.81
   609.3  2711.1   619.2  2711.4   629.2 2716.16   659.2 2734.05   679.2 2743.36
   699.2 2748.14   739.1 2750.49   759.1 2752.64     789 2756.87     819 2762.63
#Mann= 3 , 0 , 0
       0      .1       0     402    .045       0     417      .1       0
Bank Sta=402,417
XS Rating Curve= 0 ,0
Exp/Cntr=0.3,0.1

Type RM Length L Ch R = 1 ,59416.3 ,366.1,367.2,367.3
XS GIS Cut Line= 3
     1951461.045      259721.699     1951672.987      259372.619
     1951904.356      259027.093
#Sta/Elev= 30
       0 2761.05    39.8 2751.09    69.7 2748.04    79.7 2745.36    89.6  2740.3
   109.6  2726.7   149.4 2692.07   159.4 2689.16   169.3 2684.35   189.2 2669.39
   199.2 2663.41   219.1 2654.53     239  2649.8   268.9 2647.95   308.8  2643.4
   388.5 2636.76   408.4 2629.28   418.3 2627.23   428.2 2627.16   438.1 2628.79
   467.8 2635.07   517.3 2639.72   586.6 2649.53   606.4 2651.17   665.8 2661.58
   705.4 2670.94   725.2 2672.84   774.7 2688.78   814.3  2704.6   824.2 2706.97
#Mann= 3 , 0 , 0
       0      .1       0   408.4    .045       0   438.1      .1       0
Bank Sta=408.4,438.1
XS Rating Curve= 0 ,0
Exp/Cntr=0.3,0.1

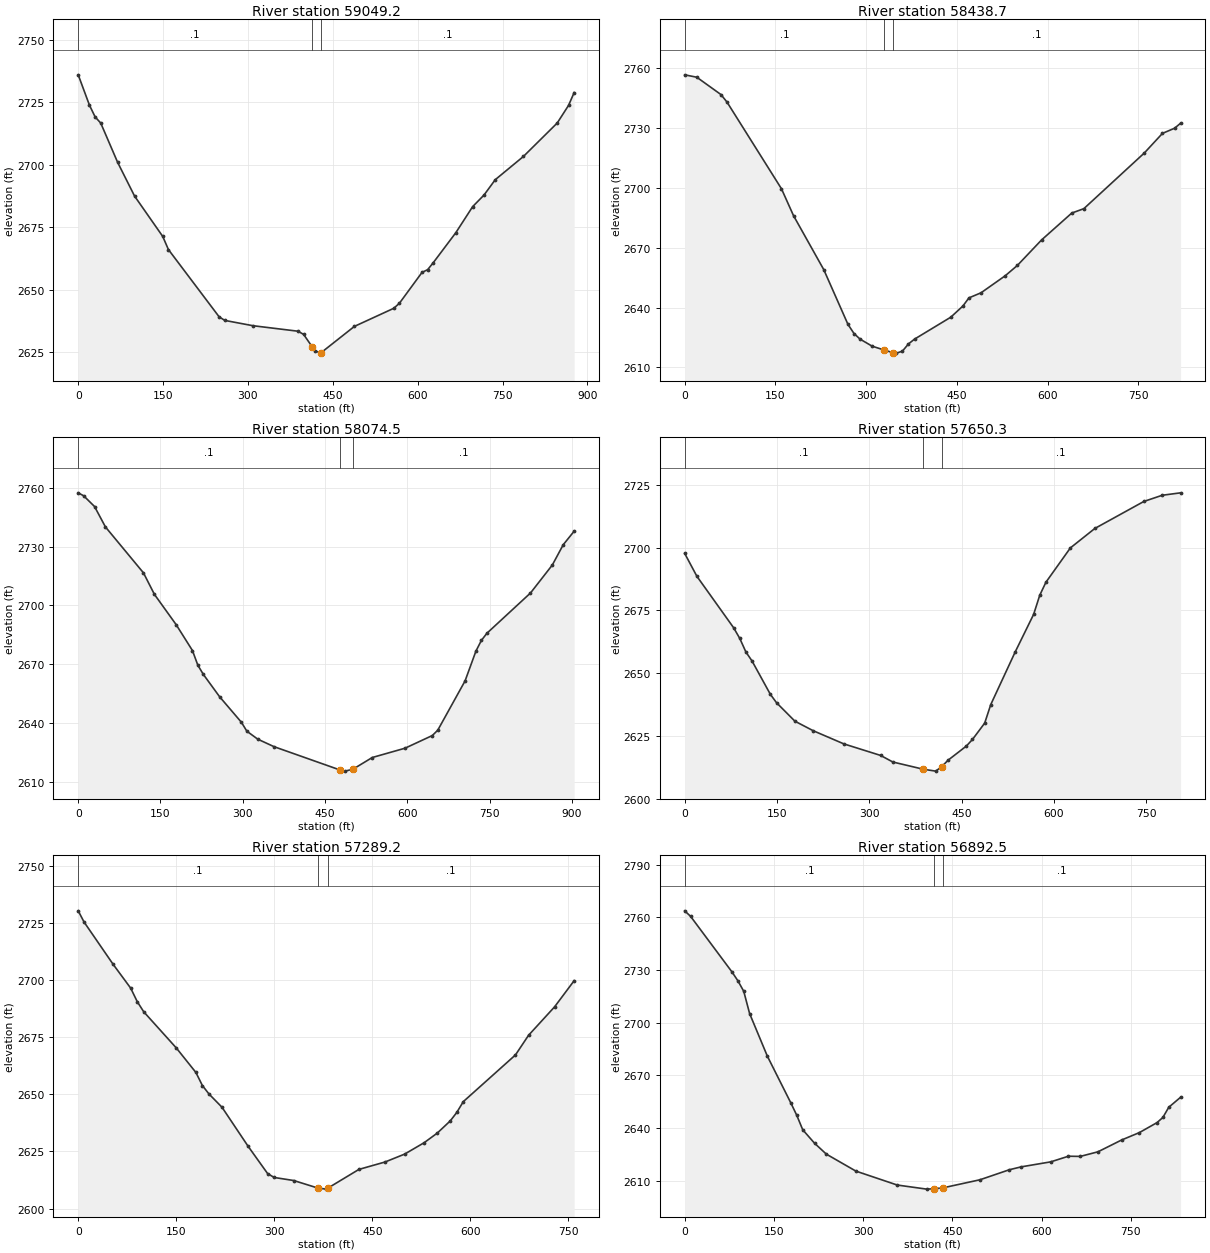
Type RM Length L Ch R = 1 ,59049.2 ,602.1,610.2,618.4
XS GIS Cut Line= 2
     1951750.905      259904.475     1952241.099      259177.839
#Sta/Elev= 30
       0 2736.01    19.9 2723.83    29.9 2719.16    39.8  2716.7    69.7 2700.95
    99.6 2687.46   149.4  2671.3   159.4 2666.06     249 2639.13     259 2637.68
   308.8 2635.56   388.5 2633.35   398.4 2632.07   413.3 2627.17   418.3 2625.59
   428.3 2624.58   488.1 2635.28   557.8 2642.54   567.8 2644.59   607.6 2656.89
   617.6    2658   627.5 2660.79   667.4 2672.81   697.2 2683.26   717.2 2687.88
   737.1 2694.03   786.9 2703.34   846.6 2716.72   866.6 2723.77   876.5 2728.92
#Mann= 3 , 0 , 0
       0      .1       0   413.3    .045       0   428.3      .1       0
Bank Sta=413.3,428.3
XS Rating Curve= 0 ,0
Exp/Cntr=0.3,0.1

Type RM Length L Ch R = 1 ,58438.7 ,373,364.2,355.4
XS GIS Cut Line= 2
     1951939.955      260252.985     1952607.981      259777.364
#Sta/Elev= 30
       0 2756.71      20 2755.51      60 2746.81      70 2743.03     160  2699.6
     180 2686.08     230 2659.02     270 2631.58     280    2627     290  2624.2
     310 2620.66   329.8 2618.74   344.8 2617.35     350 2617.18     360 2618.16
     370  2621.8     380 2624.19     440  2635.2     460 2640.79     470 2644.88
     490 2647.43     530 2655.97     550 2661.12     590  2673.9     640  2687.4
     660 2689.61     760 2717.53     790 2727.36     810 2729.93     820 2732.46
#Mann= 3 , 0 , 0
       0      .1       0   329.8    .045       0   344.8      .1       0
Bank Sta=329.8,344.8
XS Rating Curve= 0 ,0
Exp/Cntr=0.3,0.1

Type RM Length L Ch R = 1 ,58074.5 ,398.7,424.2,449.8
XS GIS Cut Line= 3
      1952131.47      260503.589     1952441.006      260369.598
       1952744.3      259890.516
#Sta/Elev= 30
       0 2757.41     9.9  2755.9    29.8 2750.42    49.6 2740.03     119 2716.58
   138.9 2705.64   178.6 2690.17   208.3 2676.97   218.2 2669.44   228.2 2664.78
   257.9 2653.37   297.6 2640.37   307.5 2635.83   327.4 2631.76   357.2 2627.92
   476.6 2616.12   486.5 2615.46   500.8 2616.41   536.2 2622.41   595.9 2627.15
   645.7 2633.62   655.6 2636.34   705.4 2661.48   725.2 2676.68   735.2 2682.15
   745.2 2685.78   824.7 2706.32   864.5 2720.59   884.4 2730.94   904.3 2737.85
#Mann= 3 , 0 , 0
       0      .1       0   476.6    .045       0   500.8      .1       0
Bank Sta=476.6,500.8
XS Rating Curve= 0 ,0
Exp/Cntr=0.3,0.1

Type RM Length L Ch R = 1 ,57650.3 ,349.9,361.1,372.4
XS GIS Cut Line= 2
     1952317.986      260499.026      1953118.04      260598.071
#Sta/Elev= 30
       0 2697.69    19.9 2688.55    79.6 2668.07    89.6 2663.82    99.5 2658.44
   109.5 2654.85   139.3 2641.57   149.3 2638.24   179.2 2630.88     209 2627.08
   258.8 2621.84   318.5 2617.25   338.4 2614.63   388.2 2611.74   408.1    2611
     418  2612.8     428 2615.32   457.8 2620.96   467.8  2623.6   487.7 2630.12
   497.6 2637.51   537.4 2658.51   567.3 2673.43   577.2 2681.02   587.2 2686.19
     627 2699.87   666.8 2707.62   746.4 2718.36   776.3 2720.83   806.2  2721.8
#Mann= 3 , 0 , 0
       0      .1       0   388.2    .045       0     418      .1       0
Bank Sta=388.2,418
XS Rating Curve= 0 ,0
Exp/Cntr=0.3,0.1

Type RM Length L Ch R = 1 ,57289.2 ,401.8,396.6,391.4
XS GIS Cut Line= 3
     1952248.787       260651.52     1952321.831      260684.838
     1952872.859      261080.809
#Sta/Elev= 30
       0 2730.23     8.9 2725.35    53.5  2706.8    80.3 2696.41    90.3 2690.52
   100.2 2686.09   150.1 2670.25   180.1 2659.52     190 2653.81     200 2650.15
     220 2644.32   259.9 2627.27   289.8 2615.31   299.8 2613.61   329.8 2612.27
   366.7 2608.98   379.6 2608.51   381.7  2608.9   429.5 2617.14   469.4 2620.37
   499.4 2623.82   529.3 2628.82   549.3    2633   569.2 2638.34   579.2 2642.04
   589.2 2646.78     669  2667.2     689 2675.78   728.9 2688.25   758.8 2699.69
#Mann= 3 , 0 , 0
       0      .1       0   366.7    .045       0   381.7      .1       0
Bank Sta=366.7,381.7
XS Rating Curve= 0 ,0
Exp/Cntr=0.3,0.1

Type RM Length L Ch R = 1 ,56892.5 ,399.8,404.6,402.3
XS GIS Cut Line= 2
     1951991.158      261029.574     1952762.445      261346.571
#Sta/Elev= 30
       0 2763.67     9.9 2760.54    79.4 2728.93    89.4 2723.87    99.3 2717.86
   109.2 2705.16     139 2680.92   178.7 2654.15   188.6 2647.13   198.5 2638.99
   218.4 2631.32   238.2 2625.12   287.9 2615.45   357.4 2607.52     407 2605.19
   419.2 2605.41   434.2 2605.91   496.4 2610.51     546 2616.24   565.8 2617.87
   615.5 2620.72   645.3 2623.93   665.1 2623.82   694.9 2626.44   734.6 2633.16
   764.4 2637.36   794.2 2643.06   804.1 2646.02     814 2651.82   833.9 2657.52
#Mann= 3 , 0 , 0
       0      .1       0   419.2    .045       0   434.2      .1       0
Bank Sta=419.2,434.2
XS Rating Curve= 0 ,0
Exp/Cntr=0.3,0.1

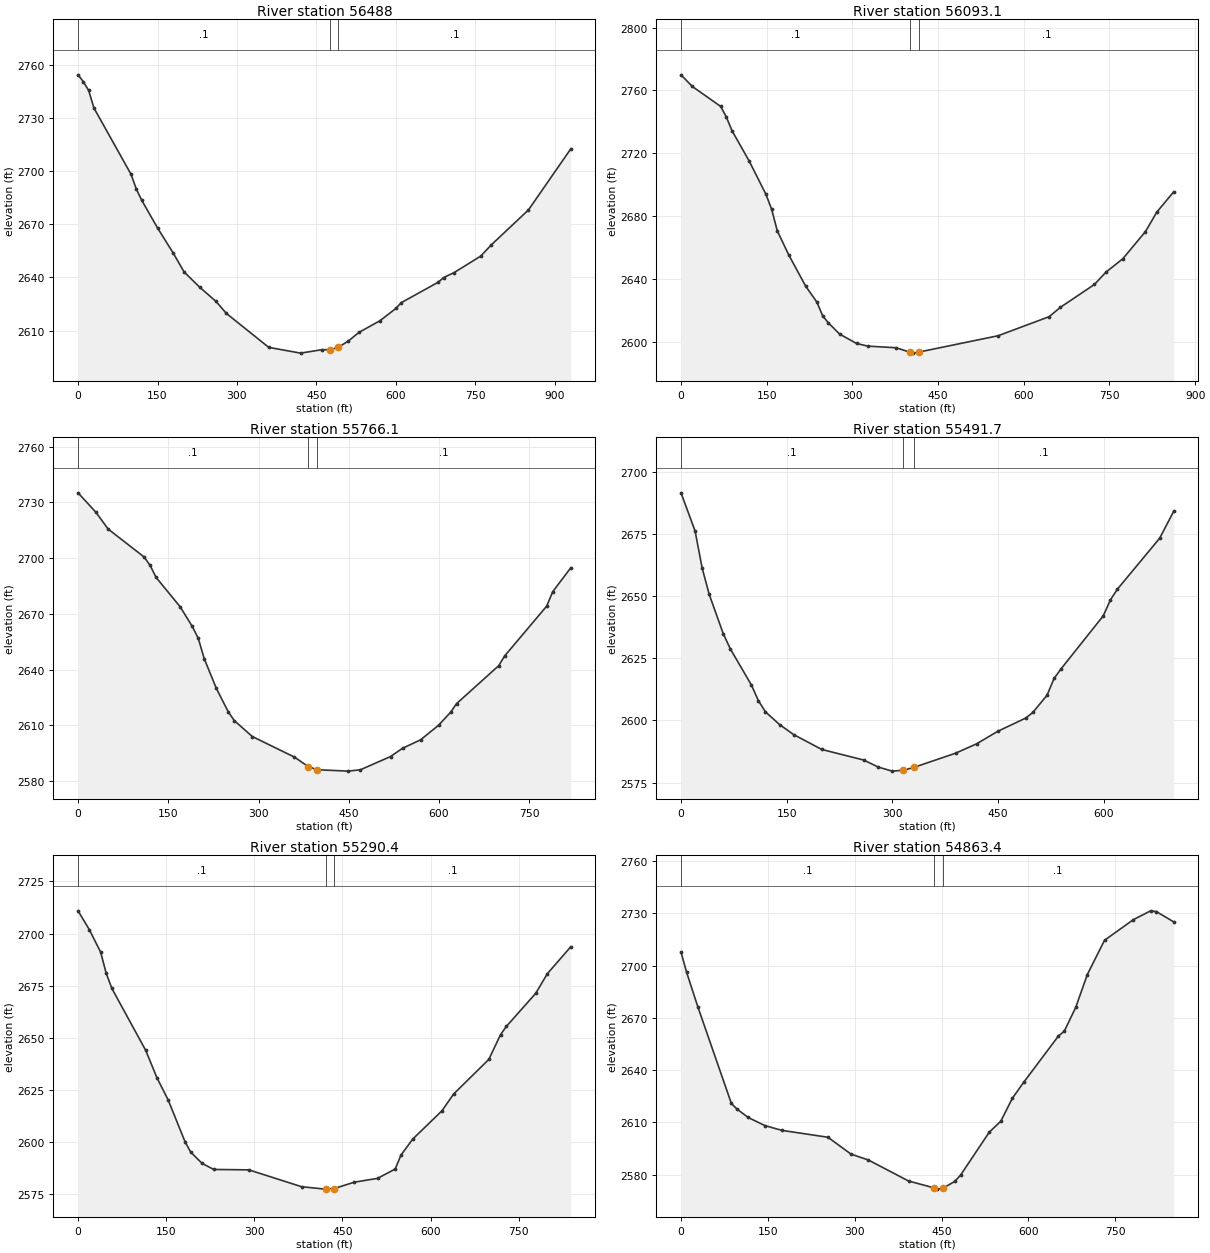
Type RM Length L Ch R = 1 ,56488   ,404.5,394.7,392.1
XS GIS Cut Line= 2
     1951743.892      261389.641       1952645.8      261617.715
#Sta/Elev= 30
       0 2754.34      10 2750.46      20 2745.53      30  2735.6     100 2698.21
     110 2689.89     120 2683.66     150 2667.94   180.1 2653.54   200.1 2643.13
   230.1 2634.34   260.1 2626.55   280.1 2619.66   360.1  2600.5   420.1 2597.26
   460.2 2599.18   476.2 2599.18   491.2 2600.52   510.2 2604.05   530.2 2608.94
   570.2 2615.58   600.2 2622.52   610.2 2625.74   680.2 2637.31   690.2  2639.9
   710.2 2642.75   760.2 2652.01   780.2 2658.35   850.3 2678.06   930.3 2712.57
#Mann= 3 , 0 , 0
       0      .1       0   476.2    .045       0   491.2      .1       0
Bank Sta=476.2,491.2
XS Rating Curve= 0 ,0
Exp/Cntr=0.3,0.1

Type RM Length L Ch R = 1 ,56093.1 ,327.2,327.1,326.9
XS GIS Cut Line= 2
     1951609.534      261738.378     1952455.103      261908.633
#Sta/Elev= 30
       0 2769.89    19.8 2762.47    69.4  2749.8    79.3 2743.08    89.2 2734.38
     119 2715.25   148.7  2693.8   158.6 2684.36   168.5 2670.61   188.4 2655.37
   218.1 2635.42   237.9 2625.17   247.9  2616.5   257.8 2612.04   277.6 2604.85
   307.3 2598.85   327.2 2597.17   376.7 2596.13   401.4 2593.21   406.5 2592.71
   416.4 2593.39   555.2 2603.79   644.4 2615.91   664.2 2621.89   723.7 2636.43
   743.6 2644.19   773.3 2652.78     813 2670.09   832.8 2682.45   862.5 2695.46
#Mann= 3 , 0 , 0
       0      .1       0   401.4    .045       0   416.4      .1       0
Bank Sta=401.4,416.4
XS Rating Curve= 0 ,0
Exp/Cntr=0.3,0.1

Type RM Length L Ch R = 1 ,55766.1 ,274.5,274.3,274.2
XS GIS Cut Line= 3
     1951567.405      262067.901      1951969.84      262143.636
     1952372.276      262219.371
#Sta/Elev= 30
       0 2735.17      30 2724.58    49.9 2715.69   109.9 2700.59   119.8 2696.05
   129.8 2689.58   169.8 2673.76   189.8 2663.23   199.8 2656.82   209.7 2645.86
   229.7 2629.97   249.7 2617.21   259.7  2612.5   289.6 2603.93   359.6 2592.86
   382.9 2587.67   397.9 2586.03   449.4 2585.29   469.4 2586.03   519.4 2593.16
   539.3 2597.59   569.3 2602.14   599.3 2610.01   619.2    2617   629.2 2621.66
   699.2 2642.08   709.1 2647.33     779 2674.18     789 2681.95     819 2694.81
#Mann= 3 , 0 , 0
       0      .1       0   382.9    .045       0   397.9      .1       0
Bank Sta=382.9,397.9
XS Rating Curve= 0 ,0
Exp/Cntr=0.3,0.1

Type RM Length L Ch R = 1 ,55491.7 ,209.7,201.3,192.9
XS GIS Cut Line= 2
     1951581.146      262352.018     1952269.291       262476.32
#Sta/Elev= 30
       0 2691.54      20 2676.18      30  2661.3      40 2650.73    59.9 2634.93
    69.9 2628.83    99.9 2614.26   109.9 2607.92   119.9 2603.44   139.9 2598.34
   159.8 2594.32   199.8 2588.32   259.7 2584.04   279.7 2581.26   299.7 2579.61
   315.4 2579.96   330.4  2581.1   389.6 2586.81   419.6  2590.6   449.5 2595.62
   489.5 2600.99   499.5 2603.27   519.5 2610.14   529.5  2616.9   539.4 2620.76
   599.4 2642.12   609.4 2648.48   619.4 2652.81   679.3 2673.27   699.3 2684.14
#Mann= 3 , 0 , 0
       0      .1       0   315.4    .045       0   330.4      .1       0
Bank Sta=315.4,330.4
XS Rating Curve= 0 ,0
Exp/Cntr=0.3,0.1

Type RM Length L Ch R = 1 ,55290.4 ,402.6,426.9,451.3
XS GIS Cut Line= 3
     1951482.946      262607.762      1951690.07      262648.036
     1952305.981      262527.638
#Sta/Elev= 30
       0 2710.93    19.2 2701.91    38.4 2691.15      48  2680.9    57.6  2673.7
   115.1 2644.07   134.3 2630.88   153.5  2620.2   182.2 2600.16   191.8 2595.25
     211 2589.89   230.9 2586.96   290.7 2586.76   380.4 2578.69   420.2 2577.53
   421.2 2577.53   436.2 2577.82     470 2580.85   509.8 2582.69   539.7 2587.16
   549.7 2593.89   569.6 2601.52   619.4  2615.1   639.3 2623.16   699.1 2639.72
     719 2651.56     729 2655.54   778.8 2671.35   798.7 2680.78   838.6 2693.73
#Mann= 3 , 0 , 0
       0      .1       0   421.2    .045       0   436.2      .1       0
Bank Sta=421.2,436.2
XS Rating Curve= 0 ,0
Exp/Cntr=0.3,0.1

Type RM Length L Ch R = 1 ,54863.4 ,540.1,519.3,498.6
XS GIS Cut Line= 3
     1951449.328      262710.244     1951606.775       262756.96
     1952040.066      263289.607
#Sta/Elev= 30
       0 2707.77     9.7 2696.15      29 2676.43      87 2620.84    96.6 2617.68
   115.9 2612.82   144.9 2608.16   174.2 2605.41   253.8 2601.45   293.6 2591.77
   323.4 2588.42   393.1 2576.31   436.9  2572.4   442.9 2571.67   451.9 2572.08
   472.7  2576.1   482.7 2579.69   532.4  2604.4   552.3 2610.68   572.2 2623.84
   592.1 2633.15   651.8  2659.6   661.8 2662.31   681.7 2676.06   701.6 2694.85
   731.4 2714.57   781.2  2726.4     811 2731.47     821    2731   850.9 2725.12
#Mann= 3 , 0 , 0
       0      .1       0   436.9    .045       0   451.9      .1       0
Bank Sta=436.9,451.9
XS Rating Curve= 0 ,0
Exp/Cntr=0.3,0.1

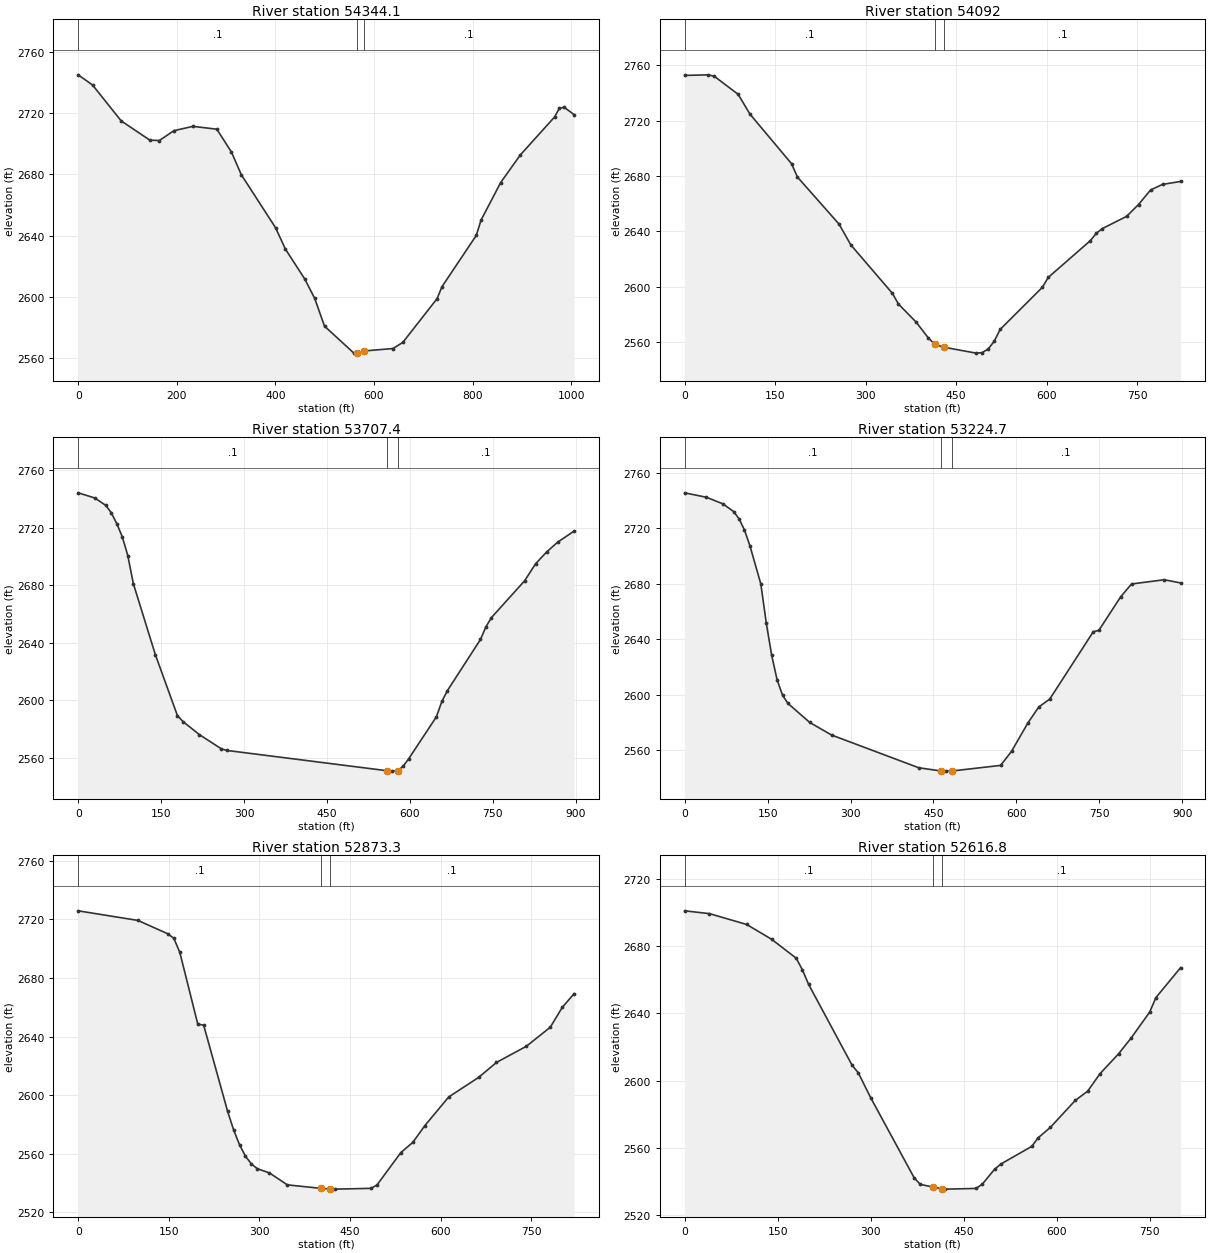
Type RM Length L Ch R = 1 ,54344.1 ,257.7,252.2,247.4
XS GIS Cut Line= 3
     1951164.931      263136.774     1951247.966      263405.379
     1951972.483      263384.086
#Sta/Elev= 30
       0 2745.27    29.1  2738.6    87.2 2715.09   145.4 2702.48   164.8 2702.26
   193.9 2708.68   232.7 2711.52   281.2 2709.66   310.9 2694.67   330.8 2679.86
   400.3 2645.15   420.2  2631.2   459.9 2611.36   479.7 2598.83   499.6  2580.7
   559.2 2563.01   565.2 2563.17   580.2 2564.43   638.6 2566.03   658.5 2570.05
     728 2598.72   737.9 2606.52   807.4 2640.07   817.3 2650.25     857 2674.74
   896.8 2692.79   966.3 2717.68   976.2 2723.48   986.1 2723.94    1006 2719.18
#Mann= 3 , 0 , 0
       0      .1       0   565.2    .045       0   580.2      .1       0
Bank Sta=565.2,580.2
XS Rating Curve= 0 ,0
Exp/Cntr=0.3,0.1

Type RM Length L Ch R = 1 ,54092   ,375.7,384.4,392.3
XS GIS Cut Line= 3
     1951203.443      263762.747      1951598.35       263640.81
     1951995.542      263543.963
#Sta/Elev= 30
       0 2752.61    39.4 2753.04    49.2 2751.94    88.6 2738.98   108.2 2724.67
   177.1 2688.83     187 2679.13   255.8  2645.2   275.5 2630.09   344.4 2595.09
   354.3 2587.41   383.8 2574.28   403.5  2563.1   414.9 2558.16   429.9 2556.17
   483.1 2551.91   493.1 2552.27     503 2554.87     513 2560.44     523 2569.07
   592.8 2599.42   602.8 2606.66   672.6 2633.26   682.5  2638.6   692.5 2641.96
   732.4 2650.73   752.3 2659.29   772.3 2669.83   792.2 2673.87   822.1 2675.97
#Mann= 3 , 0 , 0
       0      .1       0   414.9    .045       0   429.9      .1       0
Bank Sta=414.9,429.9
XS Rating Curve= 0 ,0
Exp/Cntr=0.3,0.1

Type RM Length L Ch R = 1 ,53707.4 ,456.2,482.6,509.1
XS GIS Cut Line= 2
     1951205.678      263965.378     1952098.856      264052.517
#Sta/Elev= 30
       0 2744.31    29.9 2740.75    49.9 2735.59    59.8 2730.45    69.8 2722.85
    79.8 2713.73    89.7 2700.72    99.7 2681.25   139.6 2631.77   179.5 2589.44
   189.5  2585.3   219.4 2576.16   259.2 2566.25   269.2 2565.18   558.4  2551.1
   568.4  2550.8   578.3 2551.05   588.3 2554.39   598.3 2559.58   648.1 2588.55
   658.1 2599.35   668.1 2606.81   727.9 2642.36   737.9 2651.26   747.8  2657.6
   807.7 2683.12   827.6 2694.97   847.6 2703.18   867.5 2709.98   897.4 2717.73
#Mann= 3 , 0 , 0
       0      .1       0   558.4    .045       0   578.3      .1       0
Bank Sta=558.4,578.3
XS Rating Curve= 0 ,0
Exp/Cntr=0.3,0.1

Type RM Length L Ch R = 1 ,53224.7 ,358.2,351.4,344.4
XS GIS Cut Line= 3
     1951173.567      263957.531      1951409.43      264099.931
     1951582.428      264697.092
#Sta/Elev= 30
       0 2745.62    39.4  2742.4    68.9 2737.72    88.6 2732.12    98.4 2726.87
   108.2  2718.8   118.1 2707.41   137.8 2679.87   147.6 2651.87   157.4 2628.51
   167.3 2610.76   177.1 2599.74     187 2593.85   226.3 2580.16   265.7 2571.13
   423.5 2547.53     463 2545.26   472.9 2545.11   482.8 2545.18   571.6 2549.25
   591.3 2559.38   620.9 2579.81   640.6 2591.33   660.4    2597   739.3  2645.6
   749.2 2646.48   788.7 2670.68   808.4 2679.95   867.6    2683   897.2  2680.7
#Mann= 3 , 0 , 0
       0      .1       0     463    .045       0   482.8      .1       0
Bank Sta=463,482.8
XS Rating Curve= 0 ,0
Exp/Cntr=0.3,0.1

Type RM Length L Ch R = 1 ,52873.3 ,265.9,256.5,247.1
XS GIS Cut Line= 2
     1950954.357      264103.299     1951419.344      264780.229
#Sta/Elev= 30
       0 2725.84      99 2719.28   148.4 2710.14   158.3 2707.07   168.2 2697.54
   197.9 2648.62   207.8 2647.68   247.4 2588.88   257.3 2576.29   267.2 2566.01
     277 2558.24   286.9 2552.95   296.8 2549.72   316.6 2546.87   346.3 2538.73
   402.1 2536.32   417.1 2535.86   425.5 2535.81   484.8 2536.34   494.7 2538.64
   534.3  2560.8   554.1 2567.75   573.9 2579.13   613.5 2598.74   662.9 2612.07
   692.6 2622.33   742.1 2633.36   781.7 2646.37   801.5 2659.91   821.2 2669.33
#Mann= 3 , 0 , 0
       0      .1       0   402.1    .045       0   417.1      .1       0
Bank Sta=402.1,417.1
XS Rating Curve= 0 ,0
Exp/Cntr=0.3,0.1

Type RM Length L Ch R = 1 ,52616.8 ,261.2,275.3,289.6
XS GIS Cut Line= 2
     1950655.424      264404.574     1951336.387      264823.957
#Sta/Elev= 30
       0 2701.09      40 2699.42     100 2692.96     140 2684.19   179.9 2672.87
   189.9 2665.86   199.9 2657.22   269.9 2609.14   279.9 2604.62   299.9 2589.79
   369.9 2542.15   379.9 2538.12   400.7 2536.54   415.7 2535.54   419.9  2535.3
   469.8 2535.71   479.8 2538.22   499.8 2547.17   509.8 2550.26   559.8 2560.79
   569.8 2565.82   589.8 2572.12   629.8 2588.15   649.8 2593.66   669.8 2604.12
   699.8 2615.97   719.8 2625.28   749.8 2640.76   759.8 2649.38   799.7 2667.26
#Mann= 3 , 0 , 0
       0      .1       0   400.7    .045       0   415.7      .1       0
Bank Sta=400.7,415.7
XS Rating Curve= 0 ,0
Exp/Cntr=0.3,0.1

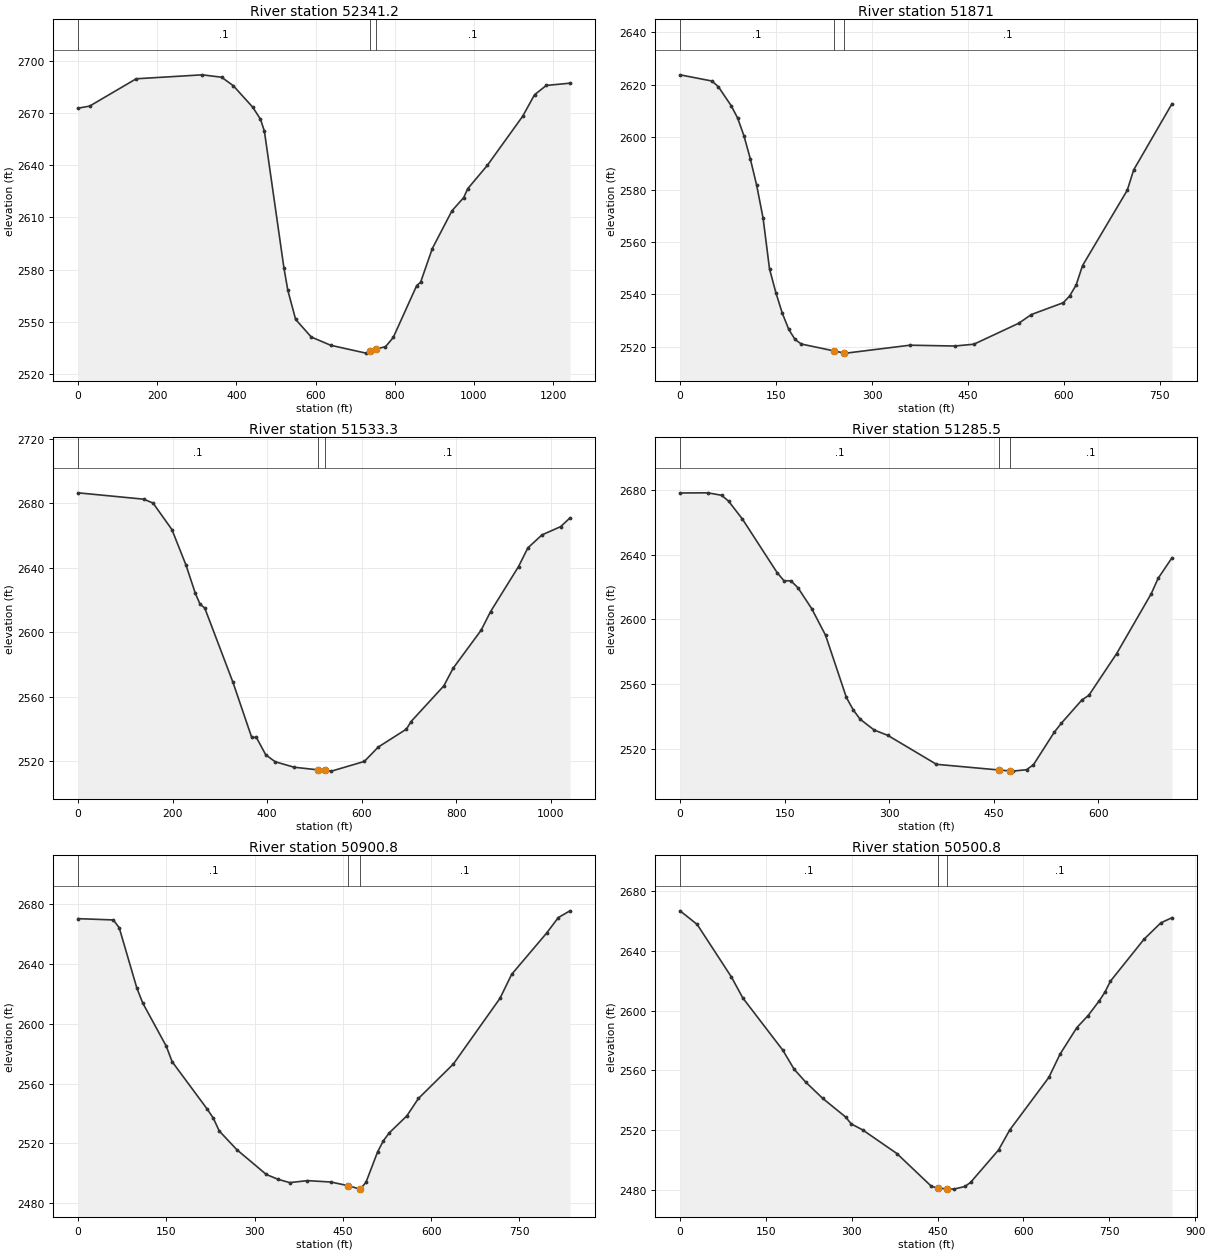
Type RM Length L Ch R = 1 ,52341.2 ,496.8,470.1,443.3
XS GIS Cut Line= 4
     1950360.717      264297.126     1950715.878      264505.358
     1950904.535      264961.073      1951238.99      265008.728
#Sta/Elev= 30
       0 2672.66    29.4 2673.86     147 2689.53   313.7  2691.8   362.7 2690.43
   392.1  2685.6   441.3 2673.27     461 2666.34   470.9 2659.45   520.2 2581.05
   530.1 2568.16   549.8 2551.47   589.3 2541.38   638.6 2536.62   727.4 2532.13
   738.8 2533.45   753.8 2534.65   776.7 2535.76   796.4  2541.1   855.6 2570.86
   865.5  2572.8   895.1 2592.13   944.7 2613.78   974.5  2621.4   984.4 2626.41
  1034.1 2639.86  1123.5 2668.07  1153.3 2680.37  1183.1 2685.71  1242.8 2687.01
#Mann= 3 , 0 , 0
       0      .1       0   738.8    .045       0   753.8      .1       0
Bank Sta=738.8,753.8
XS Rating Curve= 0 ,0
Exp/Cntr=0.3,0.1

Type RM Length L Ch R = 1 ,51871   ,358.7,337.5,316.3
XS GIS Cut Line= 2
     1950193.324       264993.11       1950962.2      264995.673
#Sta/Elev= 30
       0 2623.84    49.9 2621.47    59.9 2619.28    79.9 2612.06    89.9 2607.38
    99.8 2600.61   109.8 2591.78   119.8 2581.61   129.8 2569.09   139.8 2549.78
   149.8 2540.62   159.8 2532.84   169.8 2526.72   179.7  2522.8   189.7 2521.05
   240.9 2518.42   255.9 2517.66   259.6 2517.59   359.5 2520.62   429.4  2520.3
   459.3    2521   529.2 2528.97   549.2 2532.33   599.1 2536.85   609.1 2539.48
   619.1 2543.61   629.1 2551.02     699 2579.78     709 2587.53   768.9  2612.8
#Mann= 3 , 0 , 0
       0      .1       0   240.9    .045       0   255.9      .1       0
Bank Sta=240.9,255.9
XS Rating Curve= 0 ,0
Exp/Cntr=0.3,0.1

Type RM Length L Ch R = 1 ,51533.3 ,242.9,247.8,252.6
XS GIS Cut Line= 3
     1950363.758      265591.552     1950723.849      265104.597
     1951153.138      265035.398
#Sta/Elev= 30
       0 2686.62     139 2682.67   158.8 2680.23   198.6 2663.79   228.4  2641.7
   248.2  2624.1   258.1 2617.42   268.1    2615   327.6 2568.94   367.4 2534.58
   377.3 2534.58   397.1 2523.76     417 2519.46   456.7 2516.07   507.2 2514.41
   522.2 2514.23   536.1 2513.62   605.6 2519.65   635.3 2528.64   694.6 2539.72
   704.5 2544.47   773.6 2566.56   793.4 2577.56   852.7 2601.24   872.5 2612.73
   931.8 2640.81   951.5  2652.4   981.2 2660.44  1020.7 2665.59  1040.5 2670.98
#Mann= 3 , 0 , 0
       0      .1       0   507.2    .045       0   522.2      .1       0
Bank Sta=507.2,522.2
XS Rating Curve= 0 ,0
Exp/Cntr=0.3,0.1

Type RM Length L Ch R = 1 ,51285.5 ,371.3,384.7,398.1
XS GIS Cut Line= 2
     1950545.359      265583.832     1951074.969      265117.411
#Sta/Elev= 30
       0 2678.17    39.8 2678.26    59.6 2676.74    69.6 2673.12    89.5    2662
   139.2 2628.92   149.1 2623.86     159 2623.82     169 2619.59   188.8 2606.65
   208.7 2590.18   238.6 2551.67   248.5 2543.91   258.4 2538.18   278.3 2531.55
   298.2 2528.16   367.8 2510.29   457.8 2506.76   472.8  2506.2   477.1 2506.07
     497 2506.95   506.9 2509.98   536.7 2530.07   546.7 2535.56   576.5 2550.13
   586.4 2552.94   626.2 2578.72   675.9 2615.82   685.8 2625.34   705.7 2638.08
#Mann= 3 , 0 , 0
       0      .1       0   457.8    .045       0   472.8      .1       0
Bank Sta=457.8,472.8
XS Rating Curve= 0 ,0
Exp/Cntr=0.3,0.1

Type RM Length L Ch R = 1 ,50900.8 ,385.7,400,413.2
XS GIS Cut Line= 3
     1950585.754      265690.052     1951012.072      265635.323
     1951414.719      265583.922
#Sta/Elev= 30
       0 2670.51      60 2669.66      70 2664.43     100 2623.97     110 2613.98
   149.9  2585.1   159.9  2574.7   219.9 2542.72   229.9 2536.84   239.9 2528.31
   269.9 2515.72   319.9 2499.15   339.9 2495.89   359.8 2493.69   389.8 2495.03
   429.8 2494.08   459.5 2491.57   479.3 2489.33   489.2 2493.88     509 2514.33
   518.9 2521.82   528.8 2527.04   558.5 2538.35   578.3 2550.06   637.7 2573.16
   716.9 2617.17   736.7 2633.22   796.1 2660.86   815.9 2671.23   835.7 2675.76
#Mann= 3 , 0 , 0
       0      .1       0   459.5    .045       0   479.3      .1       0
Bank Sta=459.5,479.3
XS Rating Curve= 0 ,0
Exp/Cntr=0.3,0.1

Type RM Length L Ch R = 1 ,50500.8 ,414.3,405.8,398.6
XS GIS Cut Line= 3
     1950569.197      265802.173     1950970.326      266024.608
     1951330.197      266201.104
#Sta/Elev= 30
       0 2667.04    29.9 2657.92    89.7 2622.68   109.7  2608.6   179.5 2573.61
   199.4 2560.77   219.4 2552.26   249.3 2541.26   289.2 2528.82   299.1 2524.16
   319.1 2520.13   378.9 2504.28   438.7 2482.47   451.2 2480.93   466.2 2480.73
   478.2 2480.43   497.8  2482.2   507.6 2484.96   556.4 2506.64     576 2520.09
   644.4 2555.38     664 2571.01   693.3 2588.76   712.8 2596.77   732.4 2606.69
   742.2 2612.42     752  2619.9   810.6 2647.98   839.9 2658.94   859.5 2662.46
#Mann= 3 , 0 , 0
       0      .1       0   451.2    .045       0   466.2      .1       0
Bank Sta=451.2,466.2
XS Rating Curve= 0 ,0
Exp/Cntr=0.3,0.1