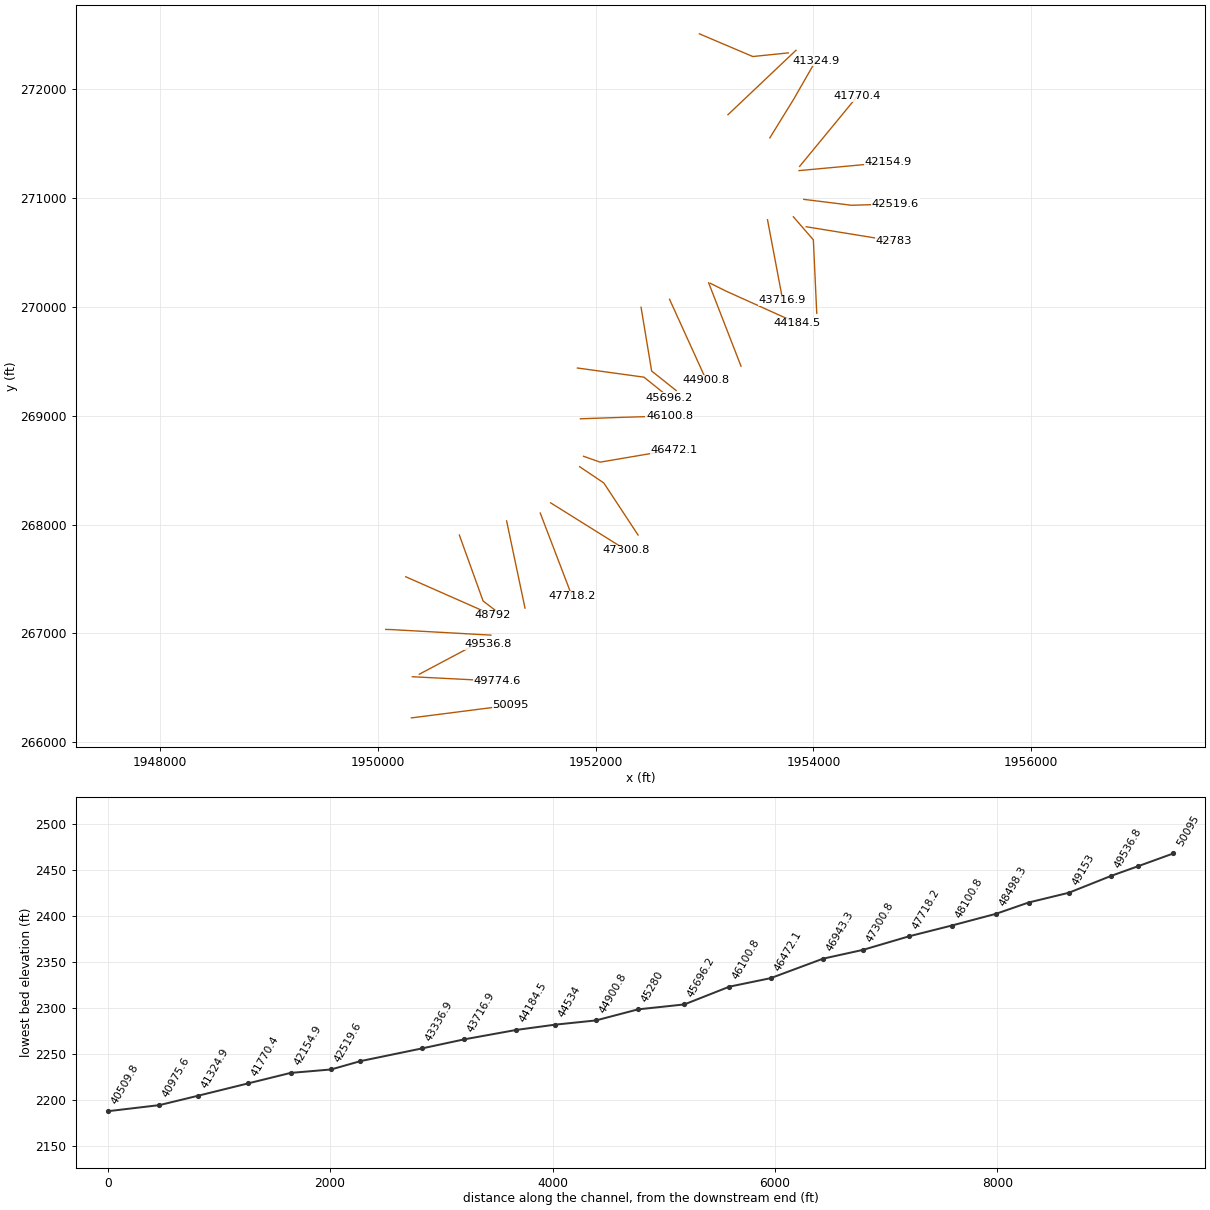
HEC-RAS study GldCrk.prj: GldCrk

--- GldCrk.g01 (geometry) --- (continued)

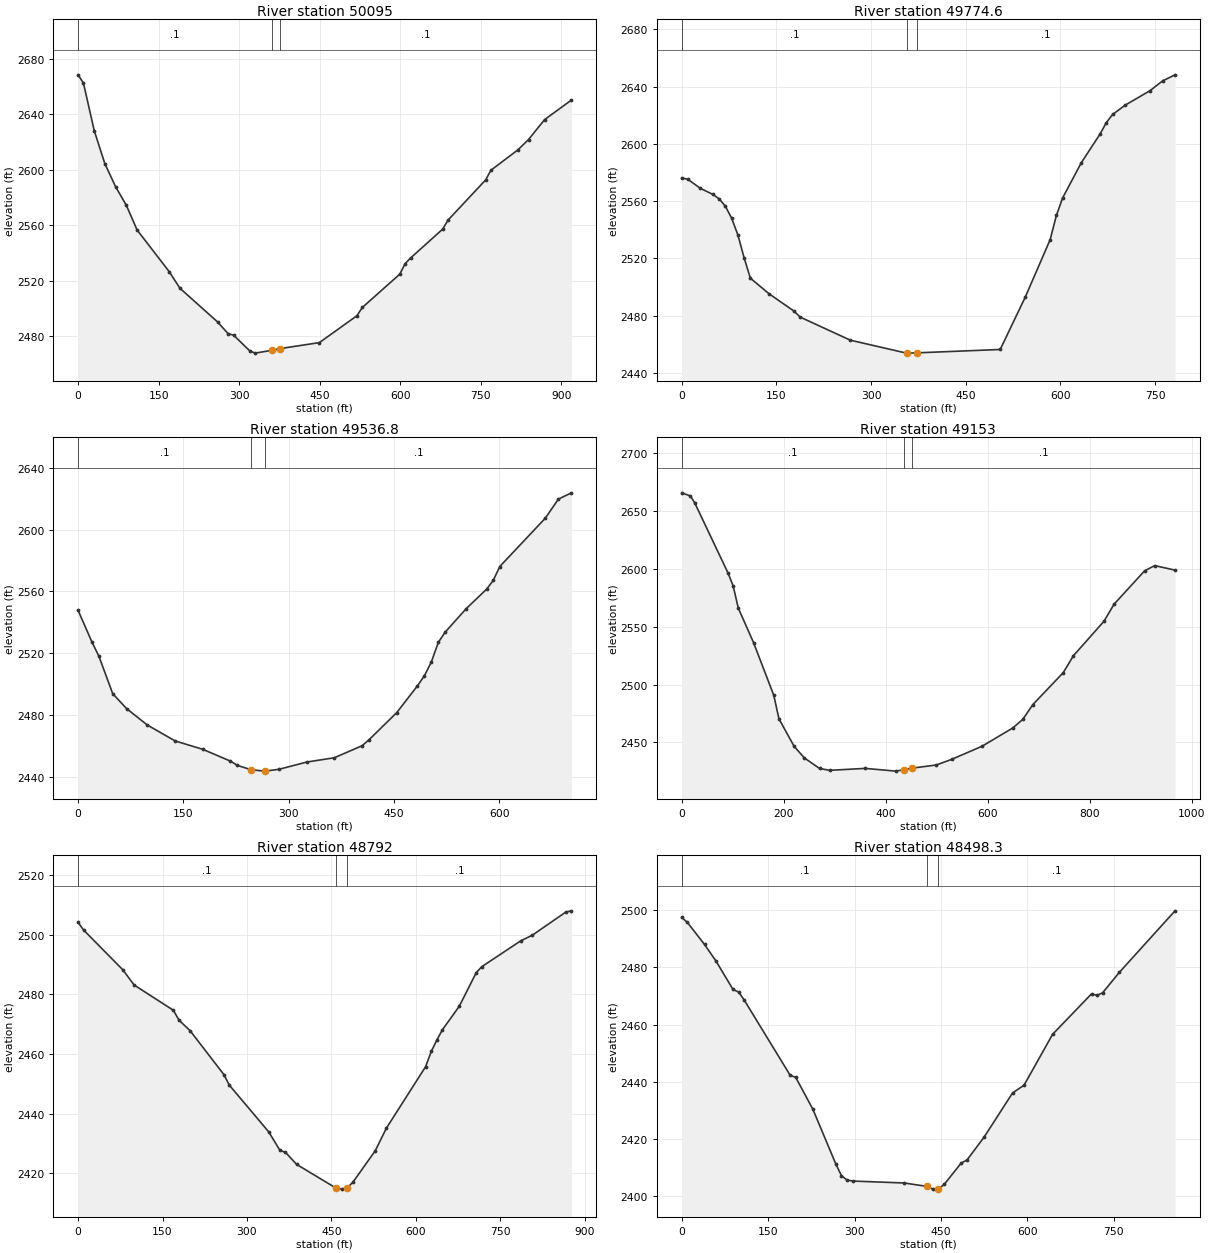
Type RM Length L Ch R = 1 ,50095   ,324,320.2,316.5
XS GIS Cut Line= 2
     1950307.374      266224.594     1951218.493      266341.207
#Sta/Elev= 30
       0 2668.58      10 2662.63      30 2628.44    49.9 2604.45    69.9 2587.89
    89.9  2574.5   109.8 2556.78   169.7 2526.67   189.7  2514.7   259.6 2490.49
   279.6 2481.88   289.5 2480.94   319.5 2469.65   329.5 2467.95   360.3 2469.92
   375.3 2471.17   449.3 2475.53   519.2  2494.9   529.2 2500.85   599.1 2524.91
     609 2532.49     619 2536.48   678.9 2557.36   688.9 2563.87   758.8 2592.78
   768.8 2599.83   818.7  2614.4   838.7 2621.92   868.6 2636.28   918.6 2650.39
#Mann= 3 , 0 , 0
       0      .1       0   360.3    .045       0   375.3      .1       0
Bank Sta=360.3,375.3
XS Rating Curve= 0 ,0
Exp/Cntr=0.3,0.1

Type RM Length L Ch R = 1 ,49774.6 ,231.9,237.6,244.7
XS GIS Cut Line= 2
     1950316.344      266602.625     1951096.754        266562.9
#Sta/Elev= 30
       0 2576.27     9.9  2575.2    29.7 2568.93    49.5 2564.68    59.4 2561.62
    69.2 2556.45    79.1 2548.13      89 2536.46    98.9 2520.43   108.8 2506.25
   138.5 2495.33     178 2483.22   187.9 2479.04   267.1 2462.98   356.1 2453.94
   357.3 2453.94   372.3 2454.13   504.5 2456.49     544 2492.85   583.6 2533.11
   593.5 2550.03   603.4 2562.28     633 2586.86   662.7 2606.85   672.6  2614.8
   682.5 2620.48   702.3 2626.95   741.8 2637.09   761.6 2643.88   781.4 2648.16
#Mann= 3 , 0 , 0
       0      .1       0   357.3    .045       0   372.3      .1       0
Bank Sta=357.3,372.3
XS Rating Curve= 0 ,0
Exp/Cntr=0.3,0.1

Type RM Length L Ch R = 1 ,49536.8 ,388.3,383.5,376.9
XS GIS Cut Line= 3
     1950380.417      266625.691     1950894.283      266898.642
      1951014.74      266902.487
#Sta/Elev= 30
       0 2547.72    19.7 2527.28    29.6 2518.06    49.3 2493.83      69 2484.15
    98.6  2473.5   138.1 2463.22   177.5 2457.77     217 2450.14   226.8 2447.39
   246.6 2444.51   266.3 2443.66     286 2444.84   325.4 2449.52   364.9 2452.32
   404.3  2460.1   414.2 2463.96   453.6 2481.48   483.2 2498.87   493.1  2505.4
     503 2514.31   512.8 2526.92   522.7 2533.64   552.3 2548.69   581.9 2561.57
   591.1 2567.12   600.4 2576.09   665.3 2607.42   683.8 2619.71   702.4 2623.79
#Mann= 3 , 0 , 0
       0      .1       0   246.6    .045       0   266.3      .1       0
Bank Sta=246.6,266.3
XS Rating Curve= 0 ,0
Exp/Cntr=0.3,0.1

Type RM Length L Ch R = 1 ,49153   ,369.6,360.9,352.7
XS GIS Cut Line= 3
     1950071.585       267037.04     1950122.843      267035.759
     1951037.561      266984.752
#Sta/Elev= 30
       0  2665.8    17.1 2663.12    25.6 2657.09    91.1 2596.29   101.1 2585.04
     111 2566.13   140.9 2536.34   180.7 2490.62   190.7 2470.42   220.6 2446.58
   240.5 2436.64   270.4 2427.48   290.3 2425.89     360 2427.57   419.7  2425.2
     436 2426.43     451 2427.71   499.4 2430.52   529.3 2435.34     589 2446.72
   648.8 2462.38   668.7 2469.85   688.6 2482.72   748.3 2510.38   768.2    2525
     828 2554.72   847.9 2569.54   907.7 2598.35   927.6 2602.88   967.4 2598.97
#Mann= 3 , 0 , 0
       0      .1       0     436    .045       0     451      .1       0
Bank Sta=436,451
XS Rating Curve= 0 ,0
Exp/Cntr=0.3,0.1

Type RM Length L Ch R = 1 ,48792   ,311.8,293.5,275.2
XS GIS Cut Line= 2
     1950255.754      267520.794      1951057.65       267166.95
#Sta/Elev= 30
       0 2504.18      10 2501.56    79.7 2488.21    99.6 2483.15   169.3 2474.66
   179.3 2471.36   199.2 2467.77     259 2453.09   268.9 2449.49   338.6 2433.88
   358.6 2427.66   368.5 2426.97   388.4 2422.92   458.2 2414.99   468.1 2414.63
   478.1 2415.11     488 2416.87   527.9 2427.49   547.8  2435.1   617.5 2455.76
   627.5 2460.83   637.4 2464.68   647.4 2468.15   677.3 2476.03   707.2 2487.24
   717.1 2489.28   786.8 2498.02   806.8 2499.84   866.5 2507.63   876.5 2508.05
#Mann= 3 , 0 , 0
       0      .1       0   458.2    .045       0   478.1      .1       0
Bank Sta=458.2,478.1
XS Rating Curve= 0 ,0
Exp/Cntr=0.3,0.1

Type RM Length L Ch R = 1 ,48498.3 ,400.5,397.4,394.3
XS GIS Cut Line= 3
     1950747.946      267903.926     1950966.045      267298.458
     1951134.624      267169.248
#Sta/Elev= 30
       0 2497.57     9.9 2495.78    39.6 2488.08    59.4  2482.3    89.1 2472.29
      99 2471.36   108.9 2468.46   188.1 2442.28     198 2441.46   227.7  2430.3
   267.3 2411.21   277.2 2407.08   287.1  2405.5     297 2405.18   386.1  2404.5
   425.7 2403.31   435.6 2402.35   445.5  2402.4   455.4 2403.99   485.1  2411.5
     495 2412.54   524.7 2420.56   574.2 2436.07     594 2438.75   643.6 2456.59
   711.1 2470.75   720.8 2470.25   730.4 2471.14   759.4  2478.3     856 2499.85
#Mann= 3 , 0 , 0
       0      .1       0   425.7    .045       0   445.5      .1       0
Bank Sta=425.7,445.5
XS Rating Curve= 0 ,0
Exp/Cntr=0.3,0.1

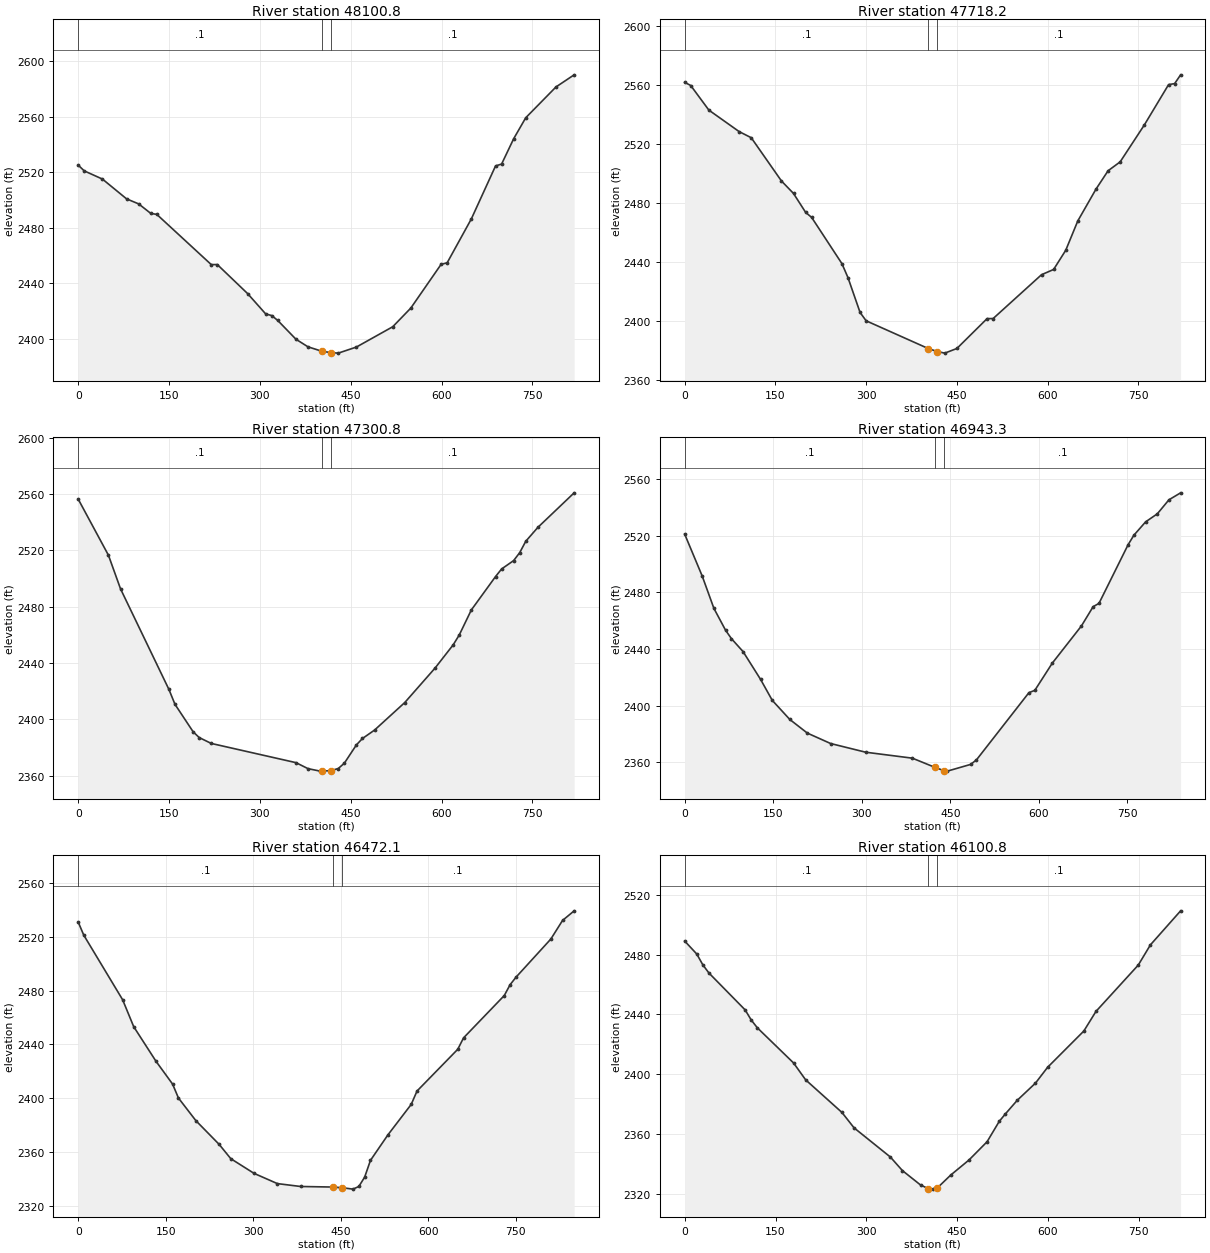
Type RM Length L Ch R = 1 ,48100.8 ,379,382.5,386
XS GIS Cut Line= 3
     1951181.974      268033.952     1951266.526      267633.276
     1951351.001      267232.584
#Sta/Elev= 30
       0 2525.15      10    2521      40  2515.1    79.9 2500.83    99.9  2497.2
   119.8 2490.37   129.8 2489.64   219.7 2453.46   229.7 2453.48   279.7 2432.58
   309.6  2417.9   319.6 2416.72   329.6 2413.16   359.6 2399.65   379.5 2394.17
     402 2391.06     417 2390.02   429.5 2389.64   459.4 2394.02   519.4 2408.65
   549.3 2422.14   599.3 2453.65   609.3 2454.76   649.2 2486.39   689.2 2524.58
   699.2 2525.93   719.1 2544.17   739.1 2559.33     789 2581.51     819 2590.25
#Mann= 3 , 0 , 0
       0      .1       0     402    .045       0     417      .1       0
Bank Sta=402,417
XS Rating Curve= 0 ,0
Exp/Cntr=0.3,0.1

Type RM Length L Ch R = 1 ,47718.2 ,402.7,417.4,432.2
XS GIS Cut Line= 2
      1951490.96      268106.018     1951783.659      267340.313
#Sta/Elev= 30
       0 2561.84      10 2559.66      40 2542.95      90 2528.38     110 2524.22
     160 2494.83   179.9 2486.37   199.9 2473.55   209.9  2470.1   259.9 2438.74
   269.9 2429.25   289.9  2405.6   299.9 2399.94   402.7 2381.09   417.7 2379.06
   429.9 2377.99   449.9 2381.14   499.8 2401.41   509.8 2401.46   589.8 2431.22
   609.8 2434.79   629.8 2447.79   649.8 2467.78   679.8 2489.31   699.8 2501.78
   719.8 2507.84   759.8 2532.93   799.8 2560.26   809.8 2560.95   819.7 2566.91
#Mann= 3 , 0 , 0
       0      .1       0   402.7    .045       0   417.7      .1       0
Bank Sta=402.7,417.7
XS Rating Curve= 0 ,0
Exp/Cntr=0.3,0.1

Type RM Length L Ch R = 1 ,47300.8 ,367.2,357.5,347.8
XS GIS Cut Line= 3
     1951586.002       268199.86     1951933.257      267982.825
     1952280.513      267765.791
#Sta/Elev= 30
       0 2556.24    49.9 2516.45    69.9 2492.54   149.8 2421.15   159.8 2410.58
   189.8 2391.08   199.8 2386.98   219.7 2382.81   359.6 2369.17   379.5 2364.91
   399.5 2363.15     402 2363.22     417 2363.47   429.5    2365   439.5 2368.79
   459.4 2381.77   469.4 2386.32   489.4  2392.3   539.3 2411.85   589.3 2436.32
   619.2 2452.79   629.2 2459.76   649.2 2477.57   689.2 2501.29   699.2 2506.67
   719.1 2512.64   729.1 2518.26   739.1 2526.34   759.1 2536.21     819 2560.73
#Mann= 3 , 0 , 0
       0      .1       0     402    .045       0     417      .1       0
Bank Sta=402,417
XS Rating Curve= 0 ,0
Exp/Cntr=0.3,0.1

Type RM Length L Ch R = 1 ,46943.3 ,444.9,471.2,497.6
XS GIS Cut Line= 3
     1951852.781      268531.527     1952074.509      268382.574
     1952389.472      267903.947
#Sta/Elev= 30
       0 2521.18    29.7 2491.54    49.5  2468.7    69.2  2453.3    79.2 2447.29
    98.9 2438.15   128.6 2418.47   148.4 2403.66   178.1 2390.16   207.8 2380.53
   247.3 2373.15   306.6 2367.02   385.7 2362.81   424.3 2356.26   439.3 2353.94
   444.9 2353.65   484.4  2358.4   494.3 2361.62   583.2 2409.15   593.1 2410.73
   622.8 2430.03   672.1 2456.29   691.9  2469.9   701.8 2472.22   751.2 2513.74
     761 2520.44   780.8 2529.84   800.6 2535.52   820.3 2545.44   840.1 2550.37
#Mann= 3 , 0 , 0
       0      .1       0   424.3    .045       0   439.3      .1       0
Bank Sta=424.3,439.3
XS Rating Curve= 0 ,0
Exp/Cntr=0.3,0.1

Type RM Length L Ch R = 1 ,46472.1 ,374.3,371.2,368.1
XS GIS Cut Line= 3
      1951888.64      268627.221     1952041.191      268573.512
     1952719.432      268688.752
#Sta/Elev= 30
       0 2530.98     9.5 2521.28    76.1 2473.25    95.1 2453.21   133.2 2427.57
   161.7 2410.56   171.7 2400.23   201.6 2383.38   241.5 2365.73   261.4 2355.12
   301.3 2344.19   341.2 2336.59   381.1 2334.44     437 2334.02     452 2333.54
   470.8 2332.48   480.8 2334.46   490.8 2341.41   500.7 2353.84   530.6  2372.8
   570.5 2395.44   580.5  2405.4   650.3 2436.44   660.2 2444.91     730 2476.39
     740 2484.47     750 2489.97   809.8  2518.4   829.8 2532.19   849.7 2539.35
#Mann= 3 , 0 , 0
       0      .1       0     437    .045       0     452      .1       0
Bank Sta=437,452
XS Rating Curve= 0 ,0
Exp/Cntr=0.3,0.1

Type RM Length L Ch R = 1 ,46100.8 ,408.5,404.6,400.9
XS GIS Cut Line= 3
     1951860.034      268971.686     1952269.299      268985.785
     1952678.629      268997.564
#Sta/Elev= 30
       0 2489.08      20 2480.38      30 2473.15      40 2467.73    99.9 2443.02
   109.9  2436.3   119.9 2431.11   179.8 2407.59   199.8 2396.28   259.7  2374.5
   279.7 2364.21   339.6 2344.73   359.6 2335.62   389.5 2326.01     402 2323.64
   409.5 2323.24     417 2323.96   439.5 2332.69   469.4 2342.67   499.4 2354.92
   519.4 2368.49   529.4 2373.42   549.3 2382.66   579.3  2394.1   599.3 2404.66
   659.2 2428.94   679.2 2442.03   749.1 2473.03   769.1  2486.5     819 2509.27
#Mann= 3 , 0 , 0
       0      .1       0     402    .045       0     417      .1       0
Bank Sta=402,417
XS Rating Curve= 0 ,0
Exp/Cntr=0.3,0.1

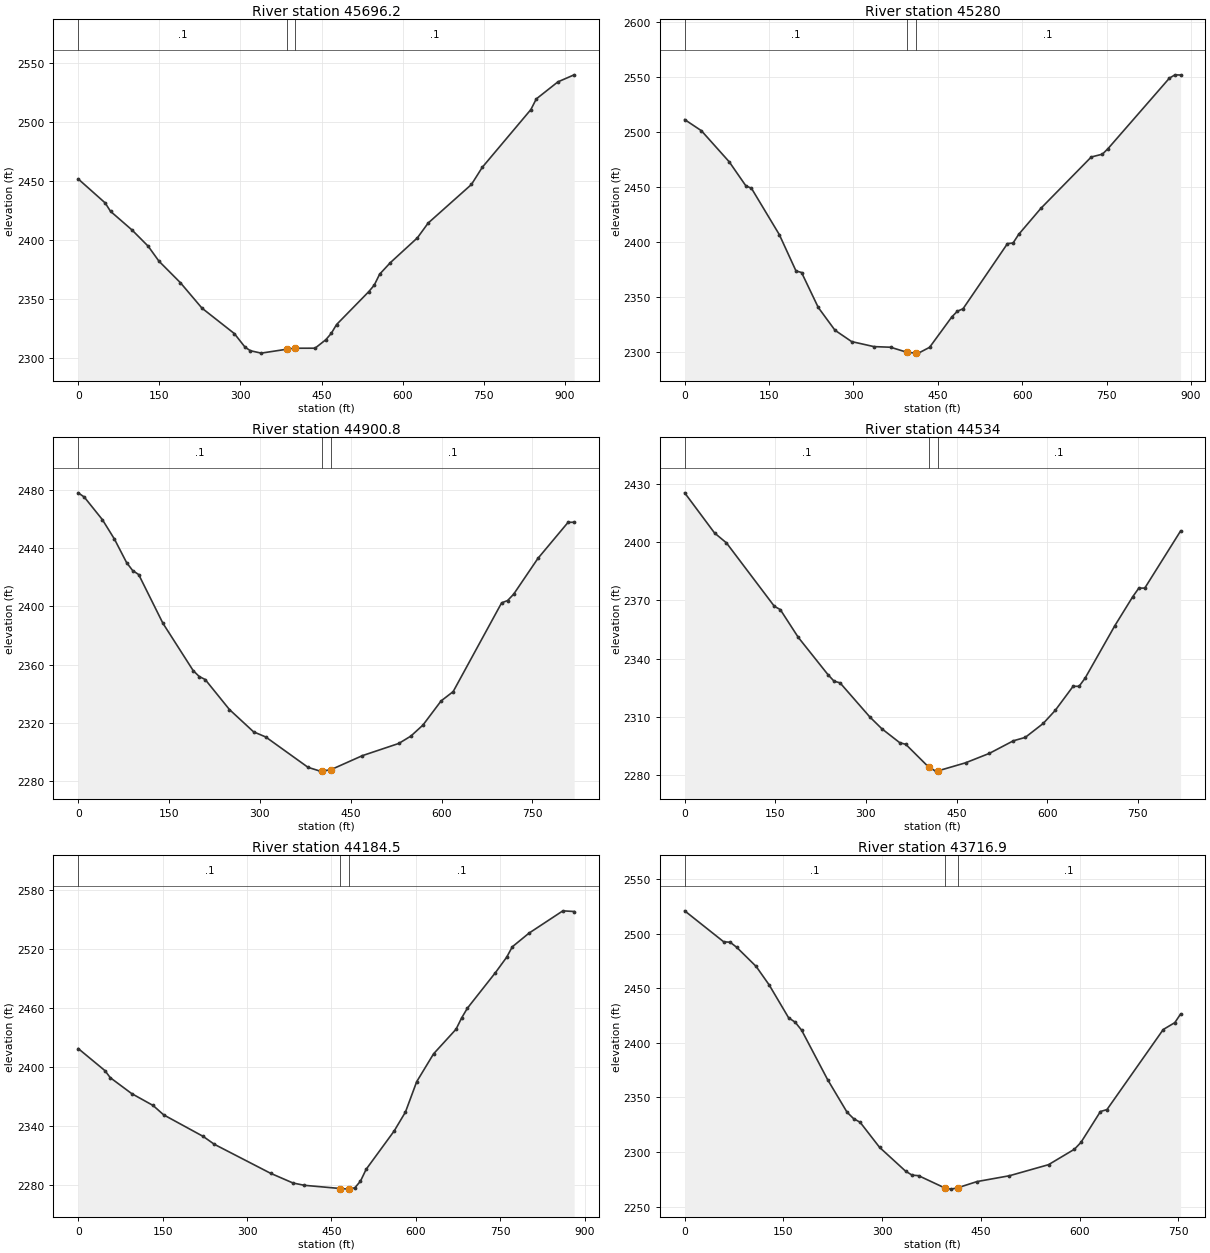
Type RM Length L Ch R = 1 ,45696.2 ,445.1,416.2,387.3
XS GIS Cut Line= 3
     1951832.412      269437.958     1952443.569      269353.922
     1952677.249      269165.944
#Sta/Elev= 30
       0 2451.89    49.8 2431.54    59.7 2424.42    99.5 2408.53   129.4 2394.74
   149.2  2382.1     189 2363.73   228.8 2342.17   288.6 2320.57   308.4 2309.03
   318.4 2305.98   338.3 2303.96   386.2 2307.33   401.2 2308.13   437.8 2308.14
   457.7 2315.33   467.7 2320.69   477.6 2328.23   537.3 2356.26   547.3 2361.75
   557.2    2371   577.1 2380.84   626.9 2401.82   646.9 2414.43   726.9 2447.19
   746.9 2461.74   836.8 2510.83   846.8 2519.86   886.8 2534.36   916.8 2540.33
#Mann= 3 , 0 , 0
       0      .1       0   386.2    .045       0   401.2      .1       0
Bank Sta=386.2,401.2
XS Rating Curve= 0 ,0
Exp/Cntr=0.3,0.1

Type RM Length L Ch R = 1 ,45280   ,373.3,379.2,385.1
XS GIS Cut Line= 3
     1952416.741      269995.981      1952514.05      269410.306
     1952739.425       269231.07
#Sta/Elev= 30
       0 2511.02    29.7  2500.9    79.2  2472.6   108.8 2450.74   118.7 2448.54
   168.2 2406.45   197.9 2373.35   207.8 2371.93   237.5 2340.12   267.2 2319.42
   296.8  2309.1   336.4 2304.53   366.1 2303.96   395.7 2299.28   410.7 2298.71
   415.6  2298.6   435.4 2303.87     475 2331.57   484.9 2336.77   494.8  2338.9
   573.9 2398.22   583.8 2398.74   593.7 2406.53   633.4 2430.36   722.8 2476.97
   742.6 2479.55   752.6 2484.58   861.8 2548.73   871.7 2551.72   881.7 2551.54
#Mann= 3 , 0 , 0
       0      .1       0   395.7    .045       0   410.7      .1       0
Bank Sta=395.7,410.7
XS Rating Curve= 0 ,0
Exp/Cntr=0.3,0.1

Type RM Length L Ch R = 1 ,44900.8 ,368,366.8,365.5
XS GIS Cut Line= 3
     1952678.432      270069.139     1952847.884      269696.344
     1953017.336      269323.548
#Sta/Elev= 30
       0 2478.29      10 2475.38      40 2459.76    59.9 2446.37    79.9 2430.22
    89.9 2424.77    99.9 2421.97   139.8 2388.49   189.8 2355.87   199.8 2351.76
   209.7 2349.69   249.7 2329.03   289.6 2313.65   309.6 2310.13   379.5 2289.21
   399.5 2286.58     402 2286.63     417 2287.52   469.4 2297.26   529.4 2305.65
   549.3  2310.7   569.3 2318.31   599.3 2334.95   619.2 2341.36   699.2 2402.48
   709.1 2404.09   719.1 2408.47   759.1 2433.09     809 2457.98     819 2458.02
#Mann= 3 , 0 , 0
       0      .1       0     402    .045       0     417      .1       0
Bank Sta=402,417
XS Rating Curve= 0 ,0
Exp/Cntr=0.3,0.1

Type RM Length L Ch R = 1 ,44534   ,330.7,349.5,368.3
XS GIS Cut Line= 2
     1953037.621      270220.205     1953334.725      269454.817
#Sta/Elev= 30
       0 2425.48    49.5 2404.76    69.2 2399.65   148.4 2366.99   158.3 2365.27
     188 2350.98   237.4 2331.66   247.3 2328.36   257.2  2327.5   306.6 2309.88
   326.4 2303.83   356.1 2296.62     366  2295.8   403.7 2284.13   415.5 2281.98
   418.7 2282.06   464.9 2286.26   504.5 2291.15   544.1 2297.62   563.8 2299.37
   593.5 2306.56   613.3 2313.25     643 2325.71   652.9 2325.72   662.8 2329.88
   712.2 2357.02   741.9 2371.99   751.8 2376.33   761.7 2376.37     821 2405.84
#Mann= 3 , 0 , 0
       0      .1       0   403.7    .045       0   418.7      .1       0
Bank Sta=403.7,418.7
XS Rating Curve= 0 ,0
Exp/Cntr=0.3,0.1

Type RM Length L Ch R = 1 ,44184.5 ,490.5,467.5,444.6
XS GIS Cut Line= 3
     1953052.263      270216.345     1953188.098      270148.428
     1953853.062      269848.688
#Sta/Elev= 30
       0 2418.82    47.5 2396.42      57 2389.25    94.9 2373.17   132.9 2361.13
   151.9 2351.55   221.8  2329.8   241.8 2321.76   341.7 2292.35   381.7 2282.46
   401.7 2280.13   465.9 2276.87   480.9 2276.27   481.6 2276.25   491.6 2277.62
   501.6 2284.34   511.6  2296.3   561.5 2335.25   581.5 2354.41   601.5 2385.21
   631.5 2413.47   671.4  2438.4   681.4  2449.9   691.4  2459.6   741.4 2495.79
   761.4 2511.45   771.4 2521.99   801.3 2535.93   861.3 2558.47   881.3 2557.78
#Mann= 3 , 0 , 0
       0      .1       0   465.9    .045       0   480.9      .1       0
Bank Sta=465.9,480.9
XS Rating Curve= 0 ,0
Exp/Cntr=0.3,0.1

Type RM Length L Ch R = 1 ,43716.9 ,383.7,379.9,376.1
XS GIS Cut Line= 3
     1953578.052      270799.738     1953708.371      270111.265
     1953712.216      270058.725
#Sta/Elev= 30
       0  2520.9    59.2 2492.57    69.1 2492.14      79 2487.53   108.6 2469.96
   128.3 2453.09   157.9 2422.94   167.8 2418.94   177.6 2411.65   217.1 2366.36
   246.7 2336.44   256.6 2330.61   266.5 2327.29   296.1 2304.28   335.6  2282.5
   345.4 2278.86   355.3 2278.36   394.8 2267.22   404.6 2266.04   414.5 2267.22
   444.1 2272.96   493.4  2278.3   552.7 2288.42   592.1 2302.59     602 2308.85
   631.6 2337.11   641.5 2338.88     727 2412.21   744.6 2418.52   753.4 2426.42
#Mann= 3 , 0 , 0
       0      .1       0   394.8    .045       0   414.5      .1       0
Bank Sta=394.8,414.5
XS Rating Curve= 0 ,0
Exp/Cntr=0.3,0.1

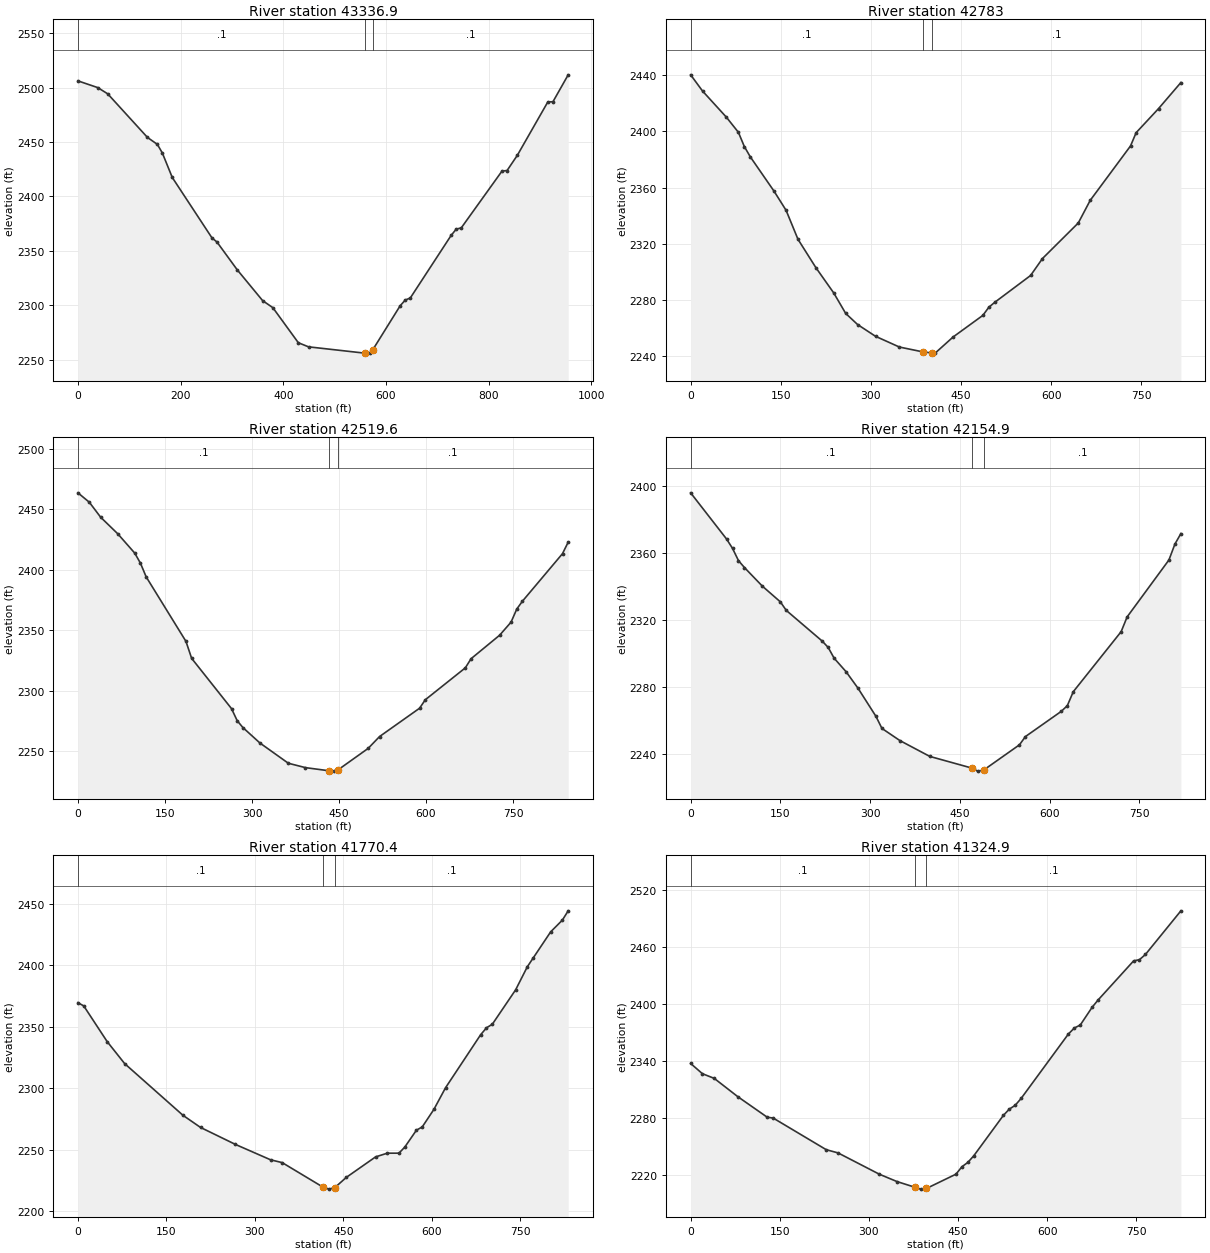
Type RM Length L Ch R = 1 ,43336.9 ,522.9,553.9,584.9
XS GIS Cut Line= 3
     1953815.789      270826.937     1953999.263       270614.88
     1954030.334      269941.272
#Sta/Elev= 30
       0 2506.16    38.7 2499.96      58 2494.26   135.4 2454.23   154.7 2447.85
   164.4 2439.93   183.7 2417.48   261.1 2361.93   270.7 2358.24   310.2 2332.69
   359.7 2304.38   379.6 2297.92   429.2 2265.73     449 2261.97   558.1 2256.19
   558.7 2256.21     568 2256.48   573.7 2258.92   627.5 2299.68   637.4 2304.89
   647.3 2306.86   726.7 2364.23   736.6    2370   746.5  2371.2   825.8 2423.33
   835.7 2423.84   855.6 2437.76   915.1 2486.87     925 2486.97   954.7 2511.71
#Mann= 3 , 0 , 0
       0      .1       0   558.7    .045       0   573.7      .1       0
Bank Sta=558.7,573.7
XS Rating Curve= 0 ,0
Exp/Cntr=0.3,0.1

Type RM Length L Ch R = 1 ,42783   ,262.7,263.6,267.8
XS GIS Cut Line= 3
     1953933.909      270735.337      1954619.49       270623.85
     1954738.666      270602.065
#Sta/Elev= 30
       0 2440.16    19.8 2428.64    59.5 2410.03    79.4 2399.34    89.3 2389.22
    99.2 2381.91   138.9 2357.38   158.8 2343.87   178.6 2323.27   208.4 2303.11
   238.1 2285.12     258 2270.58   277.8 2262.68   307.6 2254.33   347.3  2246.7
   386.9 2243.21   401.9 2242.44   406.8 2242.37   436.6 2253.81   486.2  2269.2
   496.1 2274.96   506.1 2278.52   565.6 2297.55   585.4 2309.61     645 2334.89
   664.8 2350.94   731.9 2389.63   741.2 2399.04   778.5 2416.16   815.7 2434.69
#Mann= 3 , 0 , 0
       0      .1       0   386.9    .045       0   401.9      .1       0
Bank Sta=386.9,401.9
XS Rating Curve= 0 ,0
Exp/Cntr=0.3,0.1

Type RM Length L Ch R = 1 ,42519.6 ,359.6,364.5,366.1
XS GIS Cut Line= 3
     1953911.067      270986.948     1954348.835      270932.771
     1954752.597      270944.136
#Sta/Elev= 30
       0 2463.62    19.6 2455.85    39.2 2443.42    68.6 2429.75      98  2413.7
   107.8 2405.35   117.6 2394.09   186.2  2340.7     196 2326.65   264.7 2285.06
   274.5 2275.07   284.3  2269.4   313.7  2256.6   362.7 2239.84   392.1 2236.23
   433.6 2233.57   441.1 2233.33   448.6 2234.48   500.2 2252.13   519.9 2261.95
   588.9  2285.4   598.7 2292.38   667.7 2318.78   677.6 2326.35   726.8 2345.78
   746.5 2356.59   756.4 2367.46   766.2 2373.97   835.2 2413.29     845 2422.81
#Mann= 3 , 0 , 0
       0      .1       0   433.6    .045       0   448.6      .1       0
Bank Sta=433.6,448.6
XS Rating Curve= 0 ,0
Exp/Cntr=0.3,0.1

Type RM Length L Ch R = 1 ,42154.9 ,366.5,384.4,402.3
XS GIS Cut Line= 2
     1953867.563      271250.923     1954683.684      271326.532
#Sta/Elev= 30
       0 2395.64      60  2368.1      70  2362.5      80 2355.16      90 2351.04
   119.9 2339.95   149.9 2330.61   159.9 2325.48   219.9 2307.19   229.9  2303.4
   239.9 2296.95   259.9 2288.88   279.9 2278.99   309.8 2262.26   319.8 2255.06
   349.8 2247.82   399.8 2238.36   469.8 2231.43   479.8 2229.58   489.8  2230.2
   549.7 2245.28   559.7  2250.2   619.7 2265.27   629.7 2268.63   639.7 2276.98
   719.7  2312.8   729.7  2321.6   799.6 2355.58   809.6 2365.07   819.6 2371.34
#Mann= 3 , 0 , 0
       0      .1       0   469.8    .045       0   489.8      .1       0
Bank Sta=469.8,489.8
XS Rating Curve= 0 ,0
Exp/Cntr=0.3,0.1

Type RM Length L Ch R = 1 ,41770.4 ,442.2,445.3,448.7
XS GIS Cut Line= 2
     1953873.537      271290.161     1954401.506      271931.983
#Sta/Elev= 30
       0 2369.72     9.9 2367.07    49.5 2338.11    79.2 2320.18   178.1 2278.13
   207.8 2268.29   267.1 2254.45   326.5 2241.98   346.3 2239.67   415.5 2219.73
   425.4 2218.12   435.3 2219.28   455.1 2227.71   504.6 2244.33   524.4 2247.34
   544.2 2247.36     554 2252.24   573.8 2266.02   583.7  2268.7   603.5 2282.99
   623.3 2300.63   682.7 2343.65   692.6 2349.29   702.5 2352.19     742 2380.16
   761.8  2398.9   771.7 2406.01   801.4  2427.3   821.2 2436.84   831.1  2444.4
#Mann= 3 , 0 , 0
       0      .1       0   415.5    .045       0   435.3      .1       0
Bank Sta=415.5,435.3
XS Rating Curve= 0 ,0
Exp/Cntr=0.3,0.1

Type RM Length L Ch R = 1 ,41324.9 ,355.8,349.1,342
XS GIS Cut Line= 3
       1953599.8      271552.083     1953818.498      271906.608
     1954021.754      272260.669
#Sta/Elev= 30
       0  2337.2    19.8 2326.42    39.7  2321.5    79.3 2302.24   128.9 2280.56
   138.8 2279.73   228.1  2246.4     248    2243   317.4 2220.59   347.1 2212.84
   376.9 2206.92   386.8 2204.86   396.7 2205.56   446.4 2220.62   456.4 2228.44
   466.3 2232.97   476.3 2239.94   526.1 2282.49     536 2289.06     546 2293.14
     556 2300.38   635.6 2368.29   645.6 2374.56   655.5 2377.69   675.4 2396.33
   685.4    2404   745.2 2445.21   755.1 2446.51   765.1 2451.97   824.8 2497.95
#Mann= 3 , 0 , 0
       0      .1       0   376.9    .045       0   396.7      .1       0
Bank Sta=376.9,396.7
XS Rating Curve= 0 ,0
Exp/Cntr=0.3,0.1

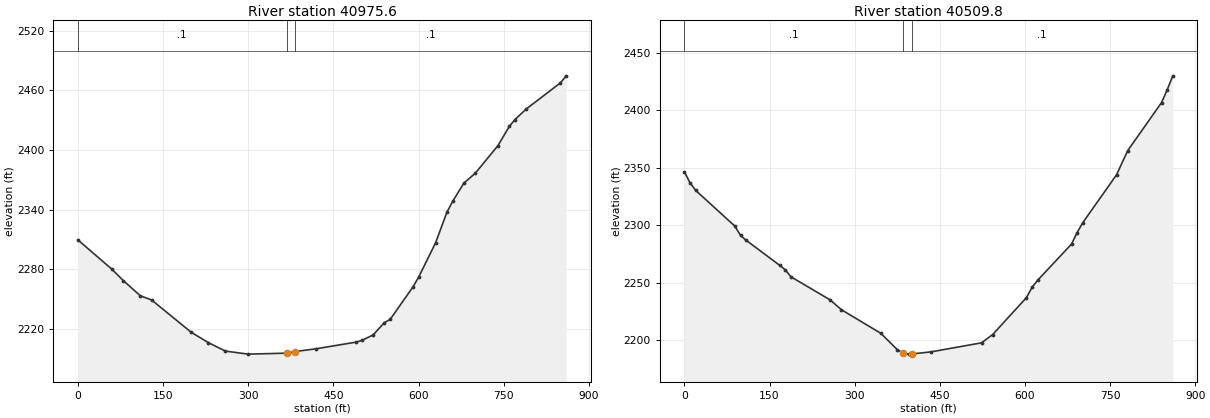
Type RM Length L Ch R = 1 ,40975.6 ,491.8,465.8,440
XS GIS Cut Line= 2
     1953215.009       271764.35     1953839.408      272355.736
#Sta/Elev= 30
       0 2309.52      60 2280.03      80 2268.62     110 2253.32     130 2249.05
     200 2216.47     230 2206.15     260 2197.66     300 2194.62   367.7 2195.59
   382.7 2197.22     420 2200.02     490  2206.7     500 2208.34     520  2213.9
     540 2226.37     550 2229.48     590 2261.99     600  2271.8     630 2306.43
     650 2337.23     660 2348.12     680 2366.66     700 2376.55     740 2404.33
     760 2423.71     770 2430.54     790 2441.23     850 2467.43     860 2474.47
#Mann= 3 , 0 , 0
       0      .1       0   367.7    .045       0   382.7      .1       0
Bank Sta=367.7,382.7
XS Rating Curve= 0 ,0
Exp/Cntr=0.3,0.1

Type RM Length L Ch R = 1 ,40509.8 ,374.5,382.3,391.4
XS GIS Cut Line= 3
     1952952.269      272507.335     1953443.109      272298.719
       1953768.6      272332.037
#Sta/Elev= 30
       0 2346.47     9.9  2336.9    19.8 2330.36    88.9 2299.27    98.8 2291.25
   108.6    2287   167.9 2265.19   177.8 2261.21   187.6 2255.25   256.8 2235.12
   276.5 2226.62   345.7  2206.2   375.3  2191.8   385.5 2188.76   395.1 2187.97
   400.5  2188.1   434.6 2189.94   523.5  2197.8   543.2 2205.02   602.7 2237.12
   612.6 2246.08   622.6  2252.3   682.1 2283.67     692 2293.65   701.9 2302.25
   761.4 2343.88   781.2 2364.99   840.7  2406.7   850.6  2417.7   860.5    2430
#Mann= 3 , 0 , 0
       0      .1       0   385.5    .045       0   400.5      .1       0
Bank Sta=385.5,400.5
XS Rating Curve= 0 ,0
Exp/Cntr=0.3,0.1