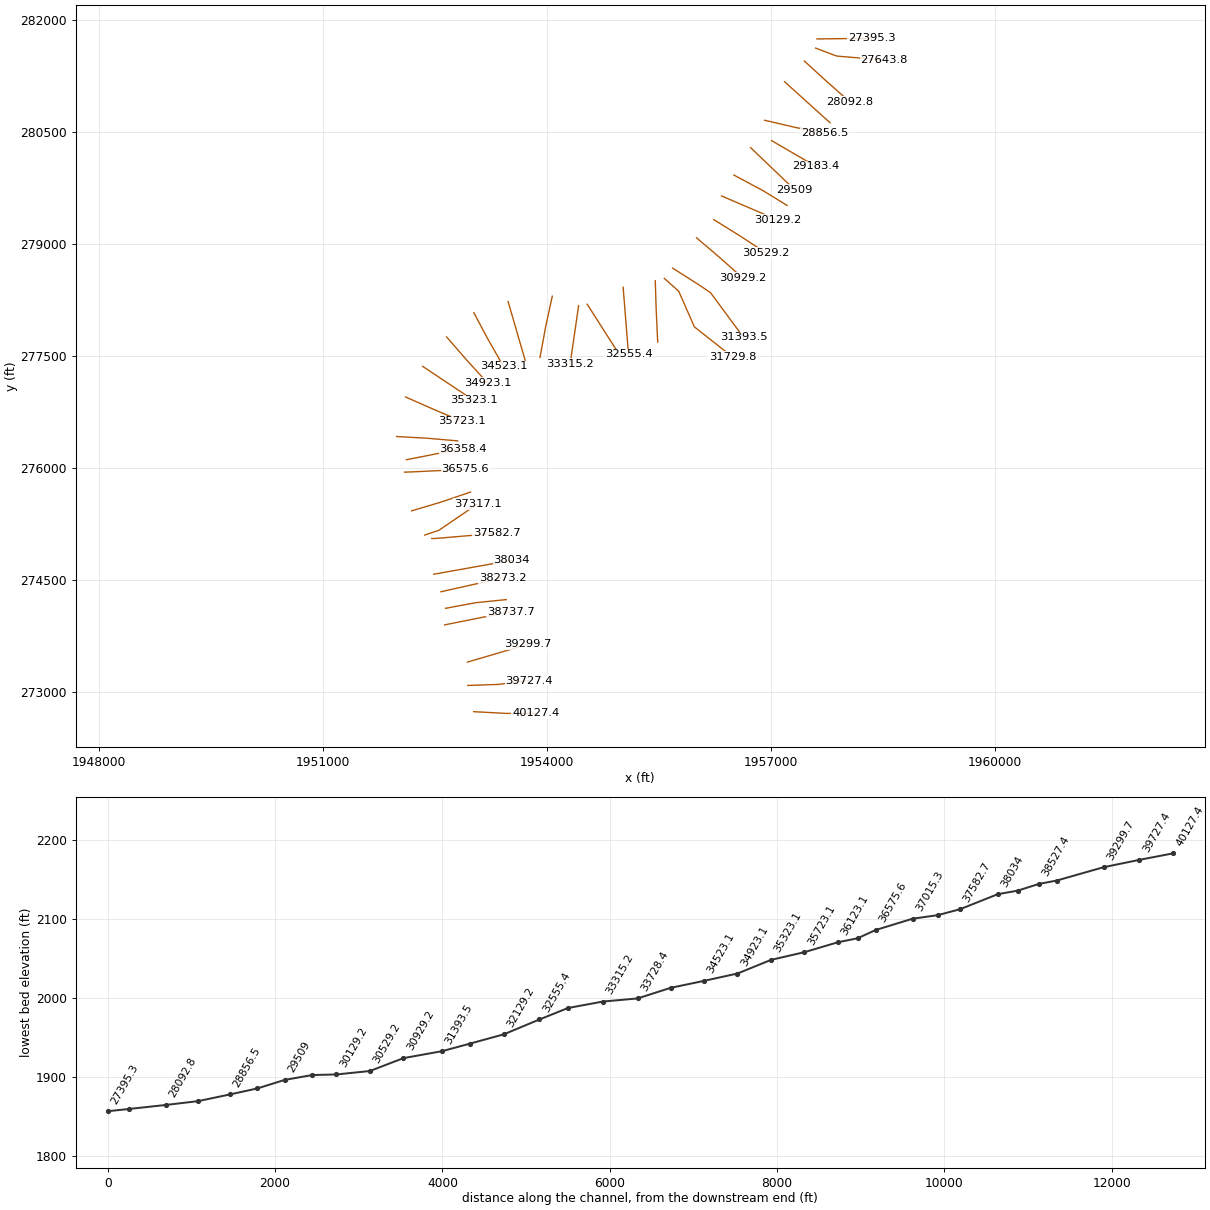
HEC-RAS study GldCrk.prj: GldCrk

--- GldCrk.g01 (geometry) --- (continued)

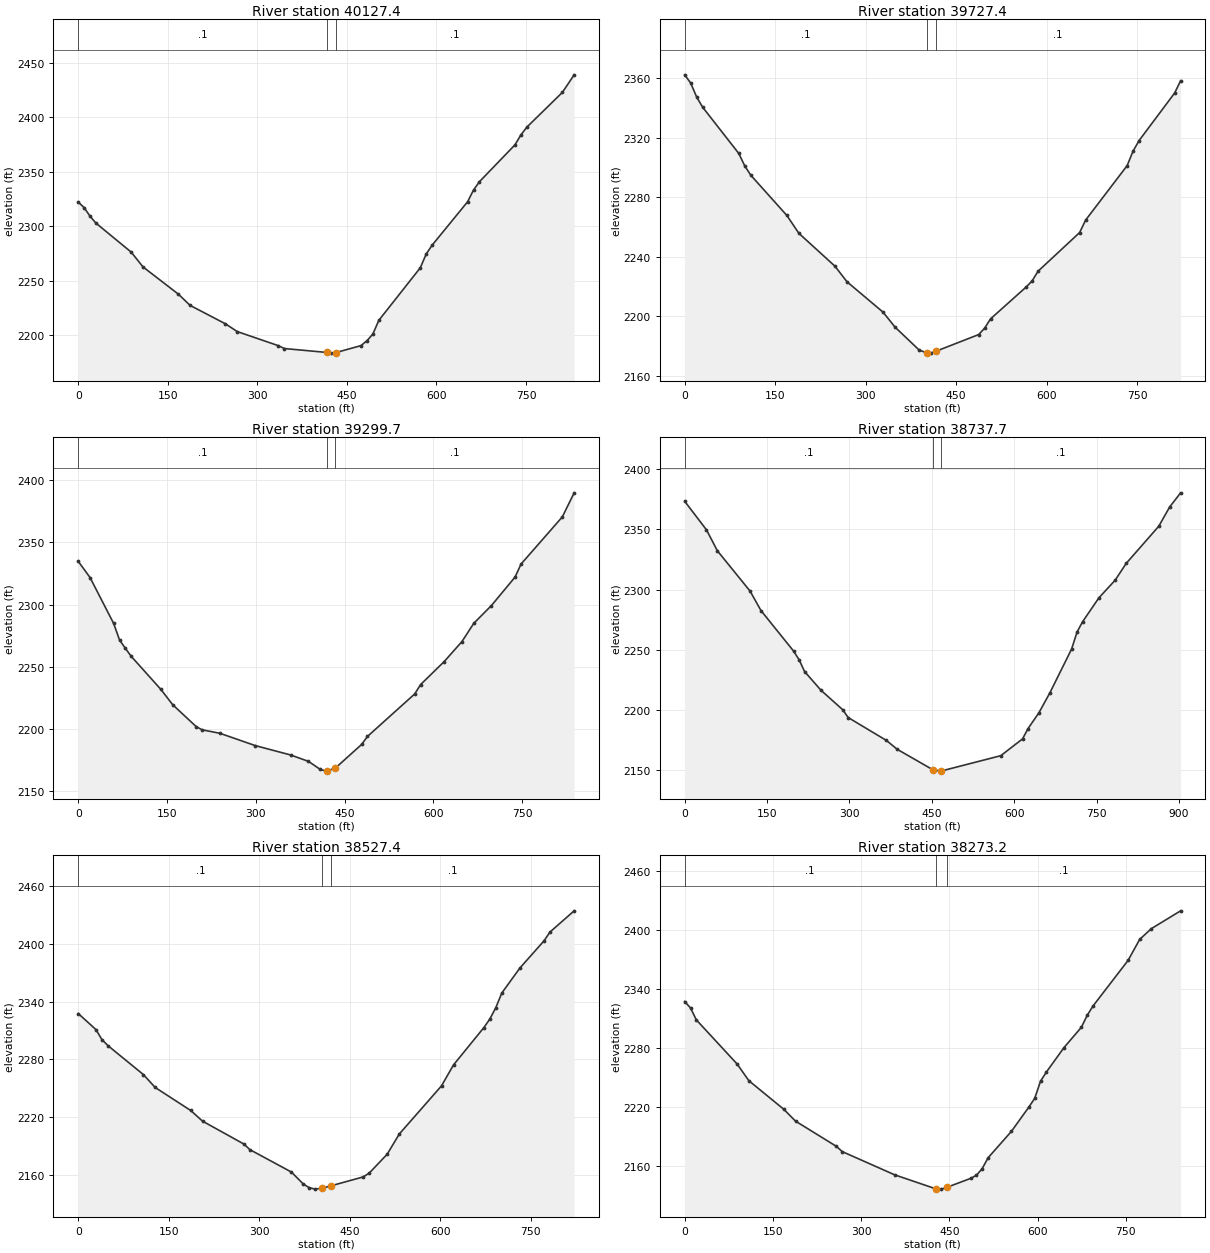
Type RM Length L Ch R = 1 ,40127.4 ,398.1,400,402.8
XS GIS Cut Line= 3
     1953020.463      272734.838     1953443.997      272712.093
     1953850.484      272711.886
#Sta/Elev= 30
       0 2322.08     9.9 2317.01    19.7 2309.17    29.6 2302.82    88.8 2276.14
   108.5 2262.59   167.7 2237.63   187.4 2227.29   246.6 2210.39   266.3 2203.29
   335.4  2190.3   345.2 2187.72   416.6 2184.11   424.1  2183.5   431.6 2184.01
   473.7 2190.42   483.6 2194.89   493.5 2201.01   503.5 2213.61   572.9 2261.78
   582.8 2274.39   592.7 2282.51   652.2  2322.4   662.1 2333.18     672 2340.78
   731.5  2374.6   741.4 2383.66   751.3 2390.79   810.8 2422.66   830.6 2438.82
#Mann= 3 , 0 , 0
       0      .1       0   416.6    .045       0   431.6      .1       0
Bank Sta=416.6,431.6
XS Rating Curve= 0 ,0
Exp/Cntr=0.3,0.1

Type RM Length L Ch R = 1 ,39727.4 ,422,427.4,430.6
XS GIS Cut Line= 3
     1952941.327       273085.99     1953349.659      273099.358
     1953759.902      273151.493
#Sta/Elev= 30
       0 2362.07      10 2356.55    19.9 2347.12    29.9 2340.29    89.7 2309.31
    99.6 2300.94   109.6 2294.71   169.4  2267.7   189.3 2255.73   249.1 2233.67
     269 2223.24   328.8 2202.84   348.8 2192.75   388.6 2177.43   401.1 2175.52
   408.6 2175.33   416.1 2176.52   487.3 2187.77   497.2 2192.05     507 2198.31
   566.1 2219.71   575.9 2223.76   585.8 2230.31   654.7 2256.23   664.6 2264.58
   733.5 2301.17   743.3  2310.9   753.2 2317.93   812.2 2349.87   822.1 2358.11
#Mann= 3 , 0 , 0
       0      .1       0   401.1    .045       0   416.1      .1       0
Bank Sta=401.1,416.1
XS Rating Curve= 0 ,0
Exp/Cntr=0.3,0.1

Type RM Length L Ch R = 1 ,39299.7 ,563.7,562,560.3
XS GIS Cut Line= 2
     1952936.932      273398.213      1953740.99      273634.237
#Sta/Elev= 30
       0 2334.76      20 2321.68    59.9 2284.75    69.8  2271.5    79.8 2264.66
    89.8  2258.2   139.7 2231.72   159.6 2219.45   199.5 2201.75   209.5 2199.23
   239.4 2196.45   299.3 2186.53   359.1 2178.98   389.1 2173.85     409  2167.4
     419 2166.02   419.7 2166.07   434.7 2168.54   478.8 2187.44   488.8 2193.93
   568.6  2228.1   578.6 2235.65   618.5 2254.15   648.4  2270.2   668.4 2284.86
   698.3  2299.2   738.2 2322.08   748.2 2332.48     818 2370.43     838  2389.8
#Mann= 3 , 0 , 0
       0      .1       0   419.7    .045       0   434.7      .1       0
Bank Sta=419.7,434.7
XS Rating Curve= 0 ,0
Exp/Cntr=0.3,0.1

Type RM Length L Ch R = 1 ,38737.7 ,210.6,210.3,208.1
XS GIS Cut Line= 2
     1952631.944      273896.701     1953517.465      274073.537
#Sta/Elev= 30
       0 2373.47    39.7 2349.69    59.5 2332.31   119.1 2298.74   138.9  2282.6
   198.5 2248.77   208.4 2241.62   218.3  2231.9   248.1 2216.34   287.8 2200.11
   297.7 2193.63   367.2 2174.62     387 2167.22   452.1 2150.16   466.4 2149.07
   467.1 2149.16   575.5  2161.9   615.2 2175.87   625.2 2184.46     645  2197.6
   664.8 2214.05   704.5 2250.58   714.5 2264.78   724.4 2273.24   754.2 2293.16
   783.9 2307.88   803.8 2321.74   863.3 2352.75   883.2 2368.81     903 2380.48
#Mann= 3 , 0 , 0
       0      .1       0   452.1    .045       0   467.1      .1       0
Bank Sta=452.1,467.1
XS Rating Curve= 0 ,0
Exp/Cntr=0.3,0.1

Type RM Length L Ch R = 1 ,38527.4 ,253.7,254.3,257.1
XS GIS Cut Line= 3
      1952643.66       274118.25     1953048.801      274193.564
     1953456.424      274235.067
#Sta/Elev= 30
       0 2327.54    29.4  2310.8    39.2 2300.47    49.1 2294.21   107.9 2264.07
   127.6 2250.59   186.4 2226.67     206 2215.59   274.7  2191.7   284.5 2185.93
   353.2 2162.66   372.8 2150.29   382.6 2146.41   392.5 2144.87   404.6 2145.89
   419.6 2148.45     472 2157.52     482 2161.38     512 2181.19     532 2202.16
     602 2252.28   621.9  2274.1   671.9 2312.67   681.9 2321.57   691.9 2333.45
   701.9 2348.84   731.9 2374.85   771.8 2403.07   781.8  2412.3   821.8 2434.33
#Mann= 3 , 0 , 0
       0      .1       0   404.6    .045       0   419.6      .1       0
Bank Sta=404.6,419.6
XS Rating Curve= 0 ,0
Exp/Cntr=0.3,0.1

Type RM Length L Ch R = 1 ,38273.2 ,240.2,239.2,237.8
XS GIS Cut Line= 2
     1952583.249      274340.087     1953405.796      274524.438
#Sta/Elev= 30
       0  2327.3     9.9  2320.8    19.8 2308.62    89.2 2263.64   109.1 2246.69
   168.6 2217.54   188.4 2205.54   257.8 2179.91   267.8 2174.53     357 2150.88
   426.4 2136.72   436.4 2136.33   446.3  2138.3   485.9 2147.21   495.8 2150.37
   505.8 2157.25   515.7  2168.2   555.4 2195.13   585.1  2219.9     595 2228.72
   604.9 2246.23   614.9 2255.54   644.6 2280.29   674.4 2301.13   684.3 2313.36
   694.2 2322.81   753.7 2369.15   773.5  2390.6   793.4 2401.52     843  2419.6
#Mann= 3 , 0 , 0
       0      .1       0   426.4    .045       0   446.3      .1       0
Bank Sta=426.4,446.3
XS Rating Curve= 0 ,0
Exp/Cntr=0.3,0.1

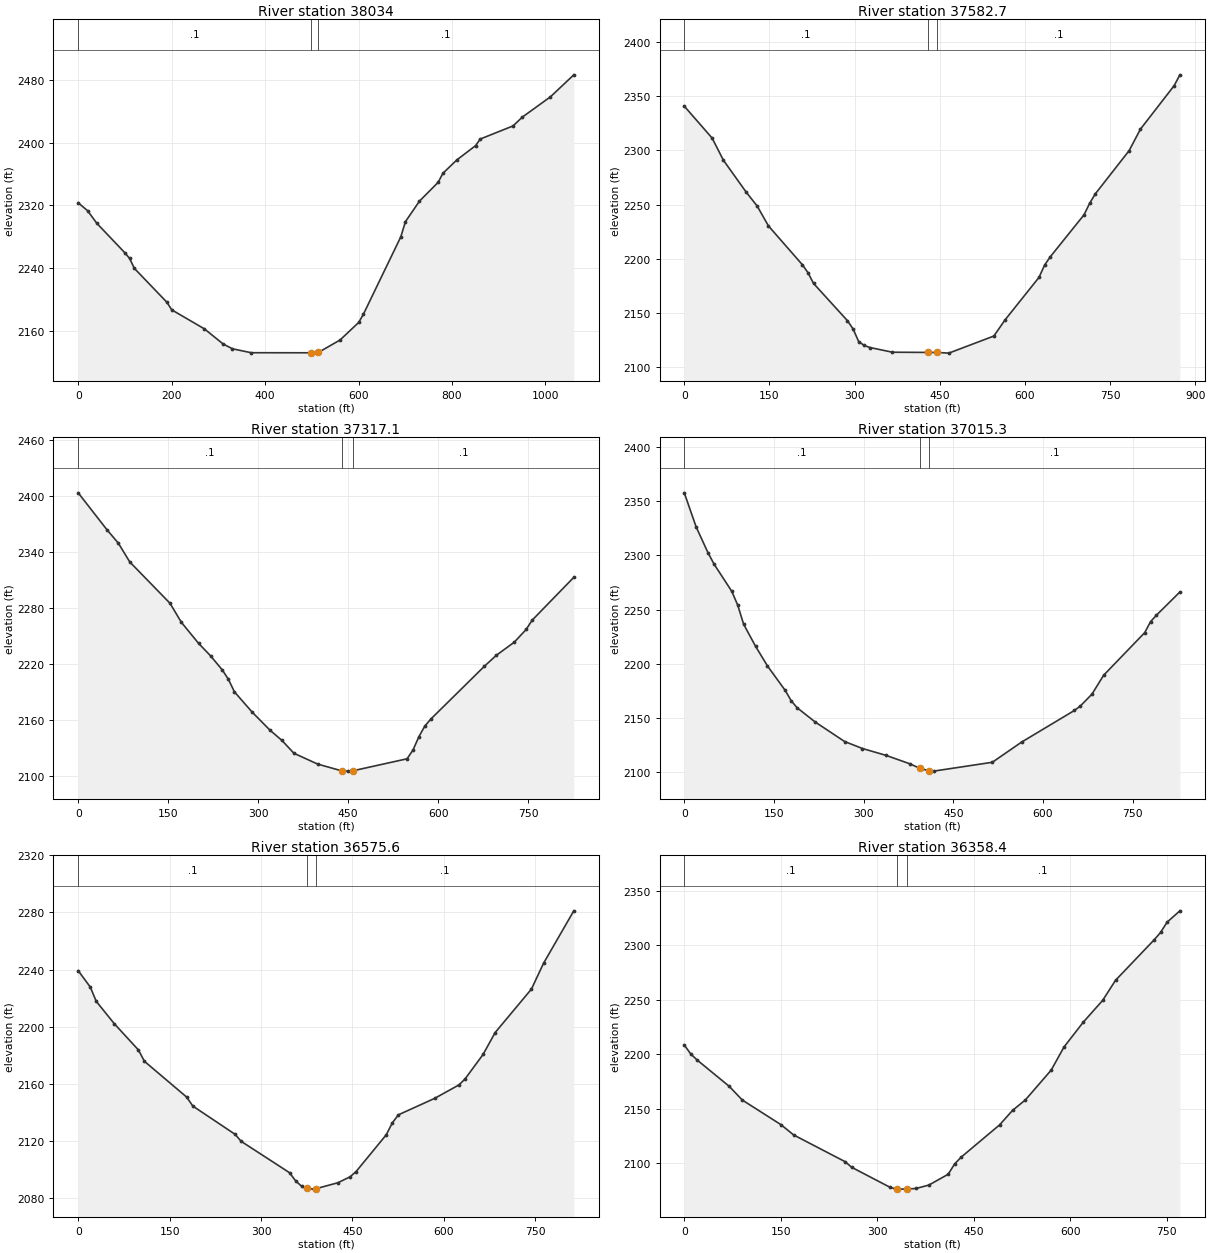
Type RM Length L Ch R = 1 ,38034   ,453.9,451.2,448.5
XS GIS Cut Line= 2
     1952485.858      274574.594     1953530.248      274760.406
#Sta/Elev= 30
       0 2323.36      20 2313.34      40 2297.16   100.1 2259.52   110.1 2252.39
   120.1 2239.89   190.1 2196.44   200.2 2186.96   270.2 2162.68   310.2 2143.45
   330.2 2137.29   370.3  2132.3   498.9 2132.22   510.4 2131.78   513.9 2132.61
   560.4 2148.48   600.4 2170.86   610.5  2181.4   690.5 2279.95   700.5 2299.39
   730.5 2325.51   770.6 2349.55   780.6 2360.96   810.6 2378.08   850.6  2396.2
   860.6 2404.64   930.7 2421.31   950.7 2432.58  1010.8  2458.4  1060.8 2486.45
#Mann= 3 , 0 , 0
       0      .1       0   498.9    .045       0   513.9      .1       0
Bank Sta=498.9,513.9
XS Rating Curve= 0 ,0
Exp/Cntr=0.3,0.1

Type RM Length L Ch R = 1 ,37582.7 ,253.6,265.4,277.4
XS GIS Cut Line= 3
     1952458.947      275052.579     1952517.894      275053.861
     1953329.059       275123.06
#Sta/Elev= 30
       0 2340.92    49.1 2311.39    68.9 2290.99   108.6 2261.84   128.5 2248.56
   148.3 2230.25   207.9  2194.5   217.8 2187.17   227.7 2177.16   287.3  2142.8
   297.2 2135.21   307.2 2123.47   317.1 2119.79     327 2117.93   366.7 2113.58
   429.7 2113.38   444.7  2113.4     466 2112.74   545.4 2128.53   565.3 2143.59
   624.9 2182.71   634.8 2194.09   644.7  2201.7   704.3 2240.59   714.2 2251.21
   724.2 2259.97   783.7 2299.84   803.6 2319.67   863.1 2359.94   873.1 2369.87
#Mann= 3 , 0 , 0
       0      .1       0   429.7    .045       0   444.7      .1       0
Bank Sta=429.7,444.7
XS Rating Curve= 0 ,0
Exp/Cntr=0.3,0.1

Type RM Length L Ch R = 1 ,37317.1 ,309.3,301.8,295.1
XS GIS Cut Line= 3
     1952364.723      275098.855     1952555.057      275162.785
     1953071.701      275515.315
#Sta/Elev= 30
       0 2403.35    47.8 2363.94    66.9 2349.44      86  2329.3     153 2285.08
   172.1 2264.54   200.8 2242.04   220.6  2228.8   240.5 2213.41   250.4 2203.62
   260.4 2190.22   290.1 2168.39   319.9    2149   339.8 2138.05   359.6 2124.38
   399.3 2112.76     439 2105.59     449 2105.24   458.9 2105.73   548.3 2118.47
   558.2 2127.92   568.1  2142.3     578 2153.63     588  2161.1   677.3 2217.65
   697.2 2229.38     727 2243.38   746.8 2257.01   756.8 2266.93   826.2 2312.82
#Mann= 3 , 0 , 0
       0      .1       0     439    .045       0   458.9      .1       0
Bank Sta=439,458.9
XS Rating Curve= 0 ,0
Exp/Cntr=0.3,0.1

Type RM Length L Ch R = 1 ,37015.3 ,444.7,439.8,434
XS GIS Cut Line= 3
     1952189.453       275422.79     1952579.833      275538.938
     1952979.042      275674.663
#Sta/Elev= 30
       0 2357.83    19.9 2326.24    39.7 2302.45    49.7 2292.07    79.5 2266.78
    89.4 2254.01    99.3  2236.4   119.2 2216.06   139.1 2197.91   168.9 2175.22
   178.8 2165.74   188.7  2159.3   218.6 2146.24   268.2 2128.06     298 2121.62
   337.8 2115.22   377.5 2107.44   394.3 2103.25   409.3 2101.03   417.1 2100.72
   515.2  2108.9   564.2 2127.55   652.4 2156.74   662.2 2160.78   681.8  2171.8
   701.5 2189.38   770.1 2228.67   779.9 2238.85   789.7 2244.79   828.9 2266.21
#Mann= 3 , 0 , 0
       0      .1       0   394.3    .045       0   409.3      .1       0
Bank Sta=394.3,409.3
XS Rating Curve= 0 ,0
Exp/Cntr=0.3,0.1

Type RM Length L Ch R = 1 ,36575.6 ,213.8,217.1,220.3
XS GIS Cut Line= 3
     1952095.012      275940.632     1952193.684      275944.476
     1952907.458      275977.794
#Sta/Elev= 30
       0 2239.26    19.8 2227.83    29.6 2217.83    59.2 2202.19    98.8 2183.81
   108.7 2175.86   178.1 2150.79   188.1 2144.56   257.5 2124.78   267.5 2119.86
   346.9 2097.91   356.8 2092.23   366.7 2088.43   375.2 2086.89   386.6 2086.44
   390.2 2086.74   426.2 2090.91   446.1 2095.04     456 2098.72   505.6 2124.48
   515.6 2132.87   525.5 2138.43     585 2149.94   624.7 2159.31   634.7 2163.44
   664.4 2180.64   684.3    2196   743.8 2226.39   763.7 2244.47   813.3 2281.13
#Mann= 3 , 0 , 0
       0      .1       0   375.2    .045       0   390.2      .1       0
Bank Sta=375.2,390.2
XS Rating Curve= 0 ,0
Exp/Cntr=0.3,0.1

Type RM Length L Ch R = 1 ,36358.4 ,240.9,235.3,229.1
XS GIS Cut Line= 2
      1952119.36      276107.222     1952875.422      276255.871
#Sta/Elev= 30
       0 2208.39      10  2200.2      20 2194.59      70 2170.35    90.1 2157.86
   150.1 2135.27   170.1 2125.72   250.2 2101.12   260.2 2096.02   320.2 2077.53
   330.2 2075.94   330.6 2075.94   345.6 2076.02   360.2 2076.52   380.3 2079.69
   410.3 2089.61   420.3  2099.1   430.3 2105.25   490.3 2135.04   510.4 2148.32
   530.4 2157.99   570.4 2185.29   590.4 2206.61   620.4 2229.44   650.4 2249.36
   670.5  2267.9   730.5 2305.06   740.5 2311.86   750.5 2321.21   770.5 2331.71
#Mann= 3 , 0 , 0
       0      .1       0   330.6    .045       0   345.6      .1       0
Bank Sta=330.6,345.6
XS Rating Curve= 0 ,0
Exp/Cntr=0.3,0.1

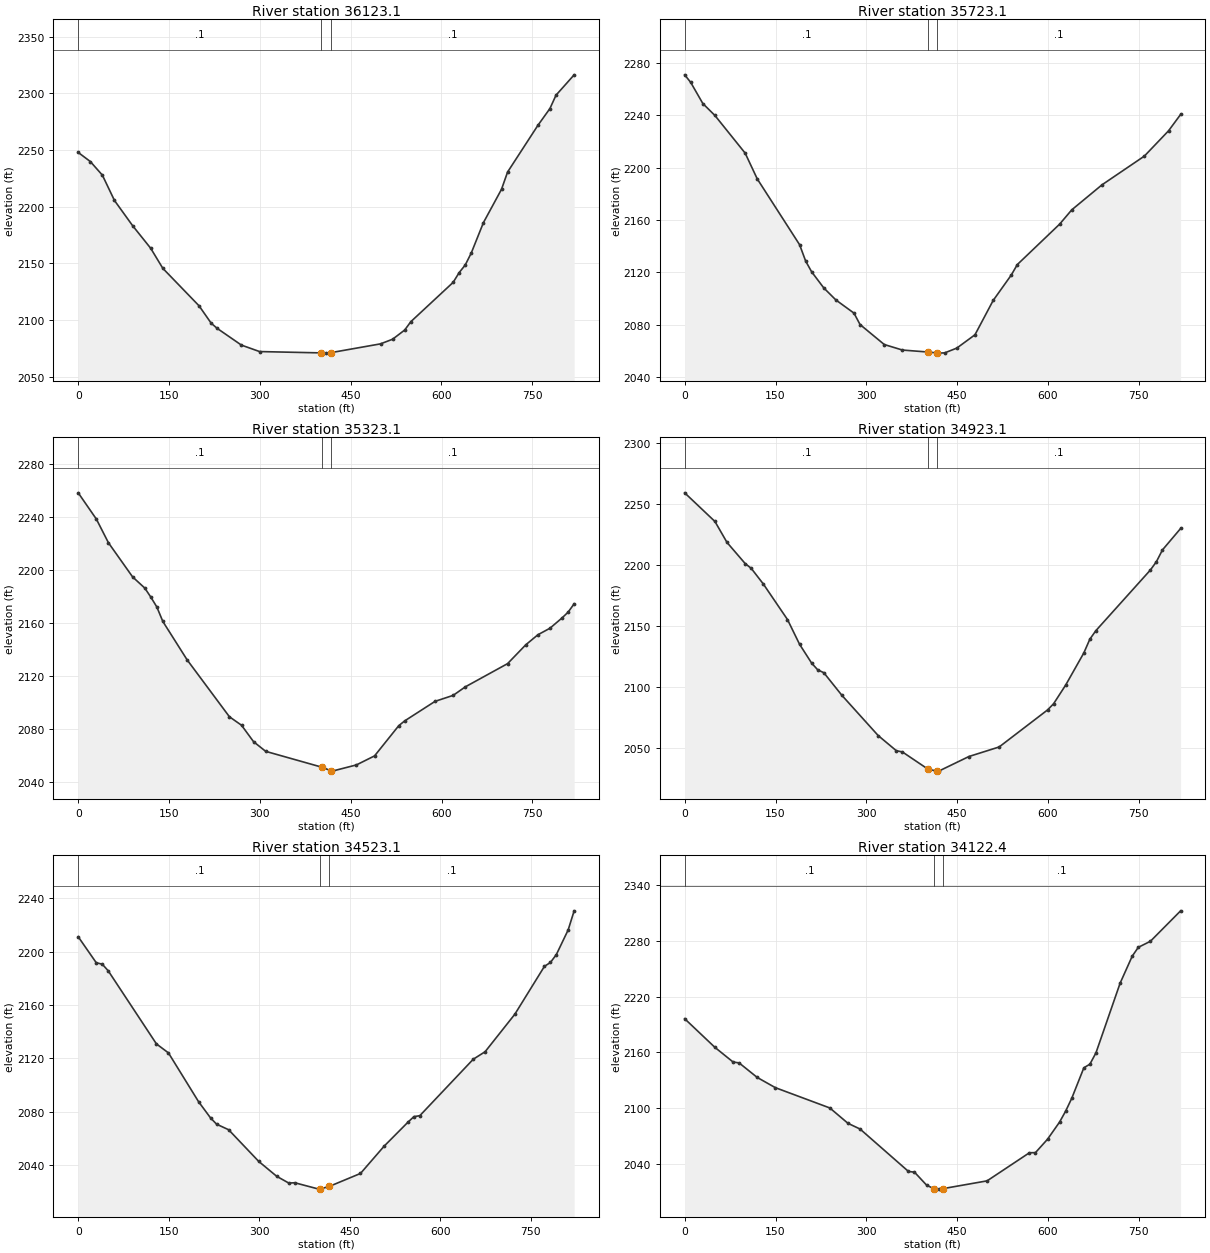
Type RM Length L Ch R = 1 ,36123.1 ,408,399.9,392.8
XS GIS Cut Line= 3
     1951987.748      276417.928     1952396.519        276395.1
       1952804.9       276359.78
#Sta/Elev= 30
       0 2247.88      20 2239.87    39.9 2227.86    59.9 2205.51    89.9 2183.27
   119.8 2163.32   139.8 2145.65   199.7 2112.56   219.7 2097.26   229.7 2092.66
   269.6 2077.96   299.6 2072.26   401.9 2071.08   409.4 2070.88   416.9 2071.25
   499.4 2079.05   519.4 2083.15   539.4 2091.27   549.4 2098.56   619.4  2133.3
   629.4 2141.94   639.4 2148.63   649.4 2159.27   669.4 2185.96   699.3 2215.38
   709.3 2230.57   759.3  2271.7   779.3 2286.63   789.3 2298.36   819.3 2316.34
#Mann= 3 , 0 , 0
       0      .1       0   401.9    .045       0   416.9      .1       0
Bank Sta=401.9,416.9
XS Rating Curve= 0 ,0
Exp/Cntr=0.3,0.1

Type RM Length L Ch R = 1 ,35723.1 ,403.8,399.9,395.7
XS GIS Cut Line= 3
     1952108.312      276947.548      1952482.93      276782.192
     1952860.179      276622.742
#Sta/Elev= 30
       0 2270.77      10 2264.97      30 2248.85    49.9 2239.76    99.9 2210.99
   119.8 2191.37   189.8 2141.08   199.8  2128.6   209.7 2120.37   229.7 2108.12
   249.7 2098.92   279.6 2088.87   289.6 2080.17   329.6 2064.91   359.6 2060.69
     402 2059.17     417 2058.45   419.5 2058.34   429.5 2058.55   449.4 2062.18
   479.4 2072.35   509.4 2098.52   539.4 2117.98   549.3 2125.93   619.3 2156.84
   639.2  2167.7   689.2 2186.82   759.1 2208.72   799.1 2228.06     819 2240.53
#Mann= 3 , 0 , 0
       0      .1       0     402    .045       0     417      .1       0
Bank Sta=402,417
XS Rating Curve= 0 ,0
Exp/Cntr=0.3,0.1

Type RM Length L Ch R = 1 ,35323.1 ,405.9,399.8,394.3
XS GIS Cut Line= 3
     1952336.544      277357.404     1952677.576      277130.716
     1953018.607      276904.028
#Sta/Elev= 30
       0 2258.31      30  2238.5    49.9 2220.68    89.9  2194.9   109.9 2186.54
   119.8 2179.79   129.8  2172.3   139.8 2161.33   179.8 2132.46   249.7 2089.53
   269.7 2083.13   289.6 2070.72   309.6 2063.46     402 2051.56     417 2048.94
   419.5 2048.55   459.4 2053.22   489.4 2060.04   529.4 2082.83   539.3 2086.46
   589.3 2101.14   619.2 2105.65   639.2 2112.05   709.1 2129.58   739.1 2143.76
   759.1 2151.32     779 2156.24     799 2164.01     809 2168.37     819 2174.67
#Mann= 3 , 0 , 0
       0      .1       0     402    .045       0     417      .1       0
Bank Sta=402,417
XS Rating Curve= 0 ,0
Exp/Cntr=0.3,0.1

Type RM Length L Ch R = 1 ,34923.1 ,405,400,395
XS GIS Cut Line= 3
     1952658.604      277750.906     1952926.994      277441.545
     1953203.278      277139.271
#Sta/Elev= 30
       0  2259.1      50 2235.63    69.9  2218.5    99.9  2201.2   109.9 2197.29
   129.9 2184.47   169.8 2155.37   189.8 2135.08   209.8 2119.63   219.8 2114.18
   229.8 2111.86   259.7 2093.31   319.6  2060.4   349.6 2047.99   359.6    2047
   402.1 2032.82   417.1 2031.32   419.6 2031.29   469.5 2043.26   519.4 2051.07
   599.3 2081.37   609.3 2086.44   629.3 2101.78   659.3 2128.09   669.2 2139.33
   679.2 2146.32   769.1 2195.88   779.1 2202.72   789.1 2212.36   819.1 2229.91
#Mann= 3 , 0 , 0
       0      .1       0   402.1    .045       0   417.1      .1       0
Bank Sta=402.1,417.1
XS Rating Curve= 0 ,0
Exp/Cntr=0.3,0.1

Type RM Length L Ch R = 1 ,34523.1 ,405.4,400.7,395.3
XS GIS Cut Line= 3
     1953022.548        278075.2     1953215.201      277714.772
     1953420.308      277356.306
#Sta/Elev= 30
       0 2211.06    29.9  2191.6    39.9 2190.51    49.8  2185.5   129.6 2130.79
   149.5 2124.05   199.4  2087.5   219.3 2075.32   229.3 2070.64   249.2 2066.49
     299  2042.8   328.9 2031.59   348.9 2026.53   358.8 2026.77   398.7 2021.99
   401.2 2022.13   416.2 2024.06   467.7 2033.74     507 2054.24   546.4 2072.17
   556.2 2076.29     566 2077.02   654.5  2119.3   674.2 2124.94   723.4 2153.01
   772.5 2188.91   782.4  2191.8   792.2 2197.71   811.8 2216.21   821.7 2230.49
#Mann= 3 , 0 , 0
       0      .1       0   401.2    .045       0   416.2      .1       0
Bank Sta=401.2,416.2
XS Rating Curve= 0 ,0
Exp/Cntr=0.3,0.1

Type RM Length L Ch R = 1 ,34122.4 ,404.9,394,383.5
XS GIS Cut Line= 3
     1953482.224      278223.147     1953596.533      277829.924
     1953710.842      277436.702
#Sta/Elev= 30
       0 2196.18    49.9 2165.42    79.9 2149.68    89.9  2148.7   119.8 2133.09
   149.8 2122.09   239.7  2100.3   269.7 2083.78   289.6 2077.68   369.6 2032.07
   379.5 2031.32   399.5  2017.4     412 2013.34   419.5 2013.09     427 2013.67
   499.4 2021.97   569.3 2052.17   579.3 2052.32   599.3 2066.77   619.2 2085.22
   629.2 2096.98   639.2 2110.66   659.2 2143.45   669.2 2147.35   679.2 2159.52
   719.1  2234.4   739.1 2263.41   749.1 2272.88   769.1 2279.38     819  2312.1
#Mann= 3 , 0 , 0
       0      .1       0     412    .045       0     427      .1       0
Bank Sta=412,427
XS Rating Curve= 0 ,0
Exp/Cntr=0.3,0.1

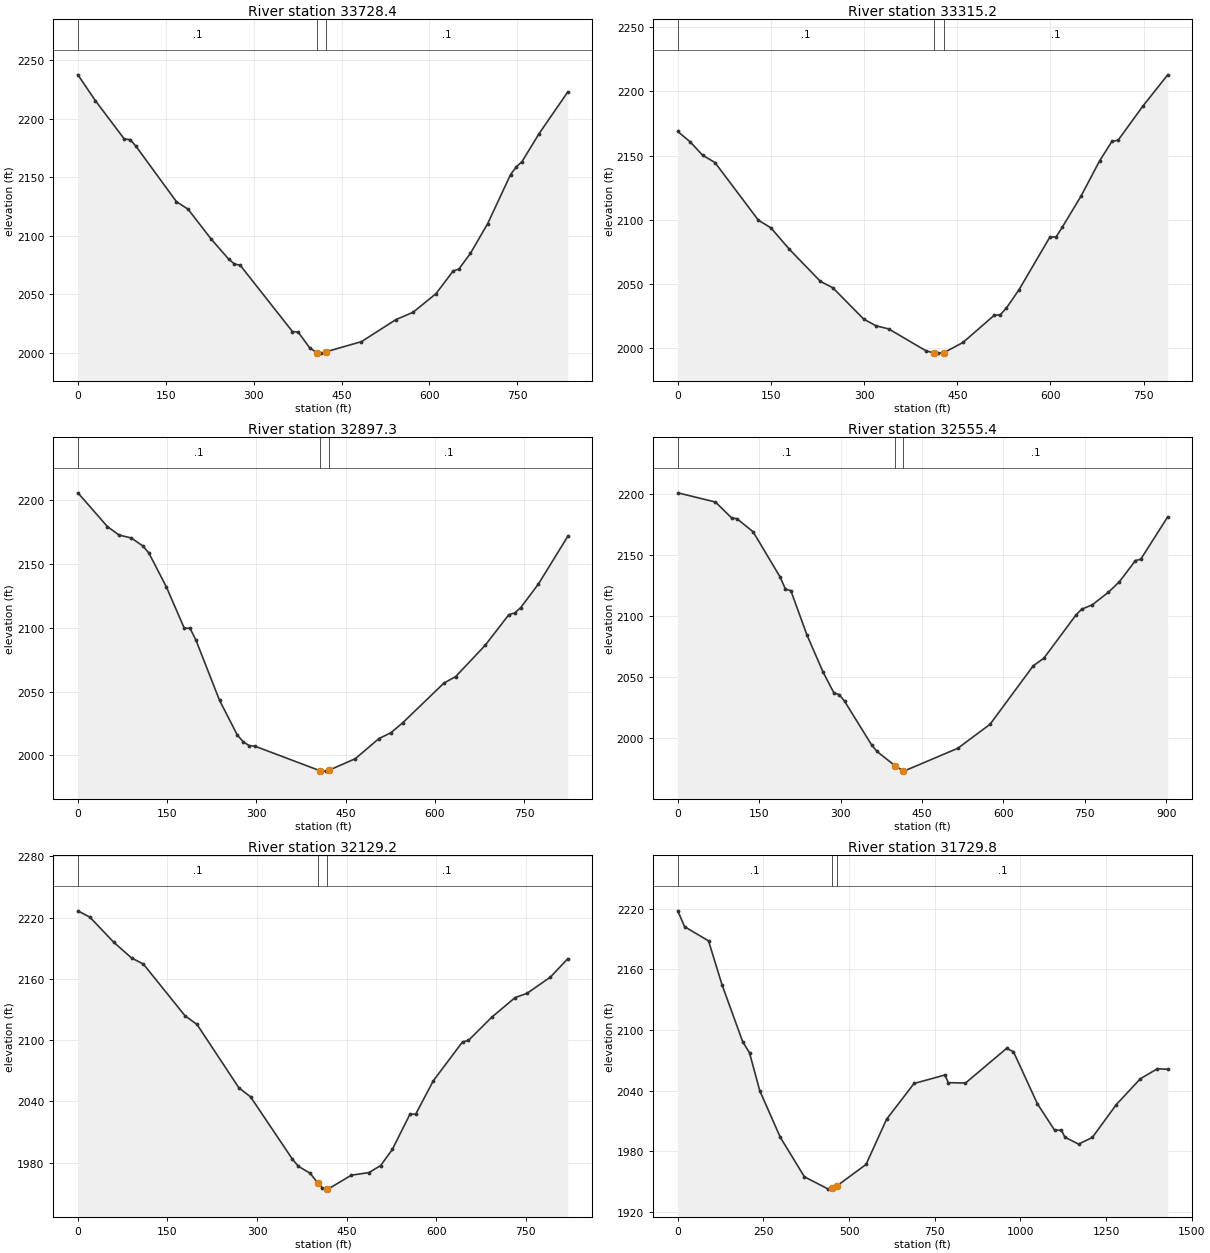
Type RM Length L Ch R = 1 ,33728.4 ,411.7,413.2,414.2
XS GIS Cut Line= 3
      1954074.09      278296.311      1953987.09      277899.966
     1953909.207      277476.494
#Sta/Elev= 30
       0 2237.37    29.7  2215.4    79.2 2182.52    89.1 2182.09      99 2176.49
   168.2 2129.01     188 2122.64   227.6 2097.05   257.3    2080   267.2 2075.83
   277.1 2074.73   366.2 2018.15   376.1 2017.55   395.9 2004.08   408.8 1999.82
   415.6 1999.69   423.8 2000.89   484.1 2009.51   542.8 2028.32   572.1 2034.54
   611.3 2050.49   640.6 2069.85   650.4 2071.54     670 2084.85   699.4 2110.16
   738.5 2152.11   748.3 2158.75   758.1 2163.26   787.4 2187.25   836.4 2222.83
#Mann= 3 , 0 , 0
       0      .1       0   408.8    .045       0   423.8      .1       0
Bank Sta=408.8,423.8
XS Rating Curve= 0 ,0
Exp/Cntr=0.3,0.1

Type RM Length L Ch R = 1 ,33315.2 ,401.9,417.9,433.9
XS GIS Cut Line= 2
     1954426.536      278170.579     1954313.221      277389.964
#Sta/Elev= 30
       0 2168.79      20  2160.7    39.9  2150.3    59.9 2144.54   129.8 2099.52
   149.8 2093.64   179.7 2076.84   229.6 2051.81   249.6  2046.8   299.5 2022.27
   319.5 2017.06   339.5  2014.7   399.4 1997.65   413.3  1995.8   419.4 1995.78
   428.3  1996.1   459.3 2004.14   509.2 2025.21   519.2 2025.75   529.2 2031.07
   549.2 2045.13   599.1 2086.39   609.1 2086.52   619.1 2094.13     649 2118.13
     679 2145.74   698.9 2161.02   708.9 2161.98   748.9 2188.65   788.8 2213.01
#Mann= 3 , 0 , 0
       0      .1       0   413.3    .045       0   428.3      .1       0
Bank Sta=413.3,428.3
XS Rating Curve= 0 ,0
Exp/Cntr=0.3,0.1

Type RM Length L Ch R = 1 ,32897.3 ,352.9,341.8,330.8
XS GIS Cut Line= 2
     1954541.268      278188.861     1954984.793      277494.952
#Sta/Elev= 30
       0 2205.78    49.6 2179.31    69.5 2172.59    89.3 2170.48   109.1 2164.17
   119.1 2158.74   148.8  2131.9   178.6 2099.78   188.5 2099.52   198.4 2090.29
   238.1 2043.03   267.9 2015.93   277.8 2010.61   287.7 2007.64   297.7 2007.12
   406.8 1987.92   416.7 1987.59   421.8 1988.25   466.3 1997.36     506 2013.14
   525.9 2017.64   545.7  2025.4   615.2 2056.62     635 2061.74   684.6 2086.28
   724.3 2110.24   734.2  2111.6   744.2 2115.75   773.9 2134.21   823.5 2171.77
#Mann= 3 , 0 , 0
       0      .1       0   406.8    .045       0   421.8      .1       0
Bank Sta=406.8,421.8
XS Rating Curve= 0 ,0
Exp/Cntr=0.3,0.1

Type RM Length L Ch R = 1 ,32555.4 ,426.9,426.2,425.9
XS GIS Cut Line= 2
     1955022.889      278416.588     1955094.912      277516.829
#Sta/Elev= 30
       0 2201.28    69.4 2193.74    99.2  2180.7   109.1 2180.06   138.9 2169.26
   188.5 2132.27   198.4 2122.23   208.3 2121.08   238.1 2084.55   267.8 2054.16
   287.6 2037.18   297.6  2035.8   307.5 2030.21   357.1 1994.53     367 1989.19
   400.8 1977.28   415.8 1973.16   416.6 1973.05   515.8 1991.78   575.3 2011.47
   654.7 2059.34   674.5  2065.7     734 2101.36   743.9 2105.78   763.8 2109.52
   793.5 2119.79   813.4 2128.28   843.1 2145.72     853 2146.86   902.6  2181.6
#Mann= 3 , 0 , 0
       0      .1       0   400.8    .045       0   415.8      .1       0
Bank Sta=400.8,415.8
XS Rating Curve= 0 ,0
Exp/Cntr=0.3,0.1

Type RM Length L Ch R = 1 ,32129.2 ,390.7,399.3,407.7
XS GIS Cut Line= 3
      1955453.25      278503.308     1955466.629      278094.618
     1955485.837      277683.603
#Sta/Elev= 30
       0 2226.65      20 2220.47    59.8 2196.03    89.8 2180.52   109.7 2174.49
   179.5 2123.81   199.5  2115.4   269.3 2053.57   289.2 2044.45     359 1983.72
     369 1976.63     389  1969.7   401.4 1960.32   408.9 1955.64   416.4 1954.54
   418.7  1954.2   457.9 1967.87   487.3 1970.41   506.9 1977.27   526.5  1993.1
   555.9 2027.42   565.7 2027.65     595  2060.2     644 2098.33   653.8 2099.71
     693 2122.51   732.2 2141.78   751.8 2145.81     791 2161.68   820.4 2179.84
#Mann= 3 , 0 , 0
       0      .1       0   401.4    .045       0   416.4      .1       0
Bank Sta=401.4,416.4
XS Rating Curve= 0 ,0
Exp/Cntr=0.3,0.1

Type RM Length L Ch R = 1 ,31729.8 ,321.8,336.3,350.5
XS GIS Cut Line= 4
      1955574.31      278535.306     1955767.679      278362.593
     1955977.061      277886.111     1956487.861      277483.511
#Sta/Elev= 30
       0 2217.88    19.9 2202.21    89.8 2188.14   129.6 2144.28   189.5  2088.4
   209.4 2077.45   239.3 2039.95   299.3 1993.84   369.4 1954.86   439.4 1942.58
   450.4 1943.27   465.4 1946.02   549.5 1966.99   609.6 2011.79   689.6 2047.07
   779.7 2055.47   789.7  2047.9   839.8 2047.53   959.8  2081.8   979.8 2078.56
  1049.9 2026.91  1099.9 2000.86  1119.9 2000.91  1129.9 1993.94    1170 1987.15
    1210 1993.67    1280  2026.2  1350.1 2051.74  1400.1 2061.72  1430.1  2061.1
#Mann= 3 , 0 , 0
       0      .1       0   450.4    .045       0   465.4      .1       0
Bank Sta=450.4,465.4
XS Rating Curve= 0 ,0
Exp/Cntr=0.3,0.1

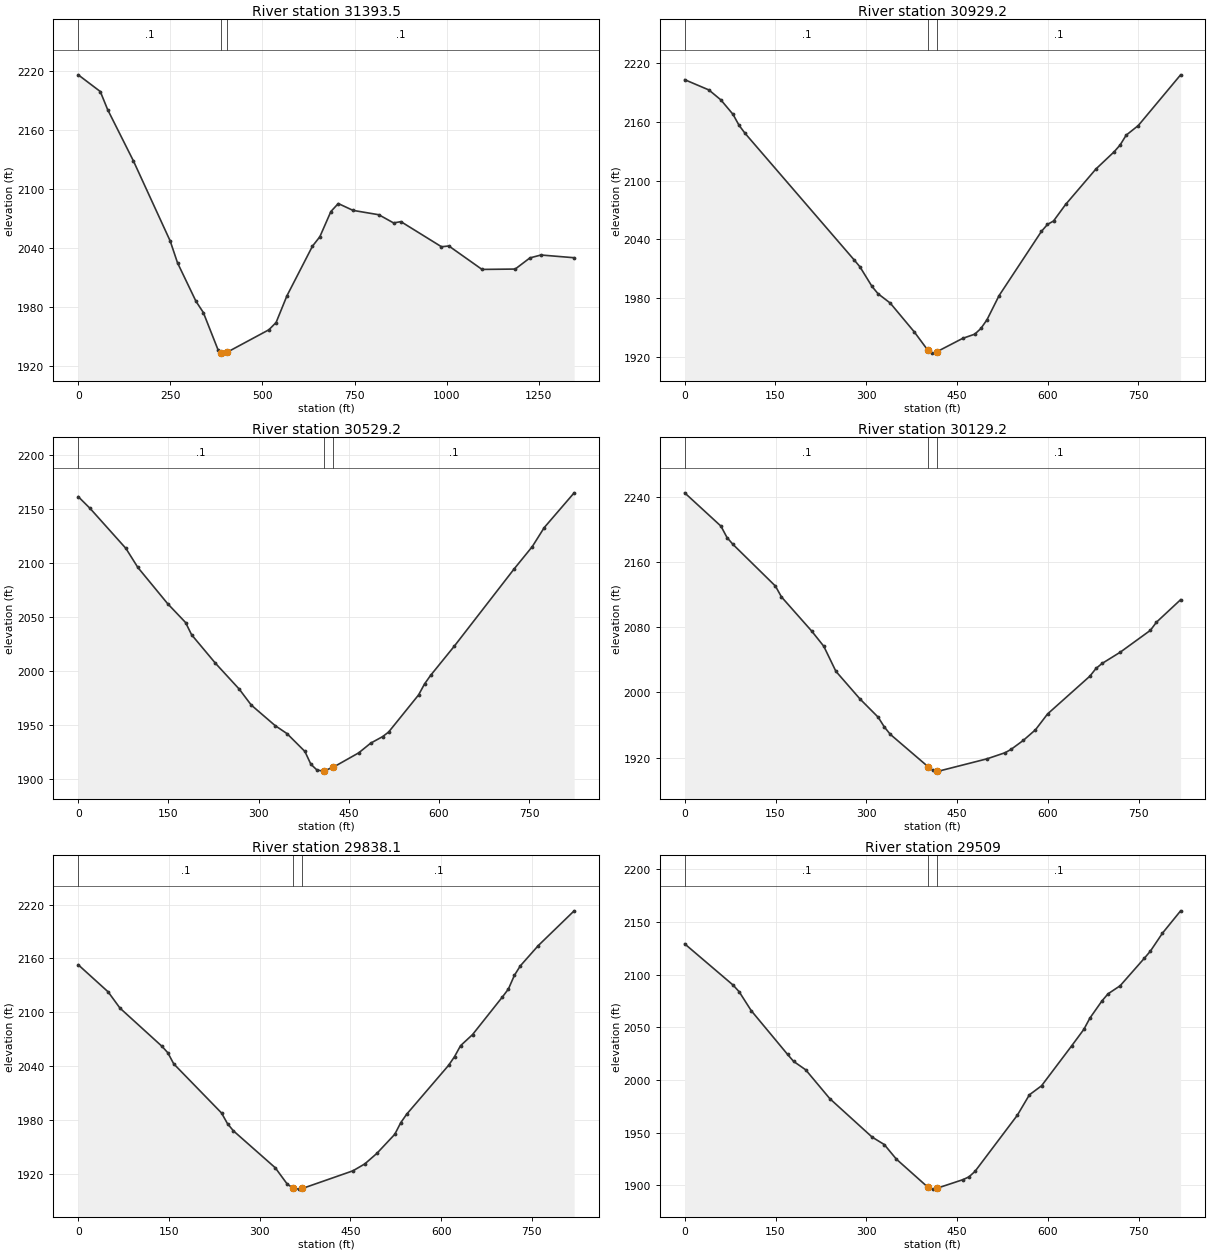
Type RM Length L Ch R = 1 ,31393.5 ,467.4,464.2,460.8
XS GIS Cut Line= 4
      1955685.79      278672.553     1956031.432      278453.023
     1956194.206      278343.076     1956633.947      277747.492
#Sta/Elev= 30
       0 2215.72    59.9 2198.76    79.9 2180.37   149.8 2128.28   249.7 2046.83
   269.6 2024.65   319.6 1985.64   339.6  1974.2   379.5 1936.33   388.5 1933.26
   389.5 1932.92   403.5 1933.69   517.5 1956.64   537.1 1964.01   566.6  1991.2
   635.9 2041.64   655.9 2051.18   685.9 2076.83   705.9 2084.92     746 2077.97
     816 2073.54     856 2065.23     876 2066.53   986.1 2041.01  1006.1 2041.81
  1096.1 2017.98  1186.2 2018.35  1226.2  2029.7  1256.2 2032.63  1346.2 2029.85
#Mann= 3 , 0 , 0
       0      .1       0   388.5    .045       0   403.5      .1       0
Bank Sta=388.5,403.5
XS Rating Curve= 0 ,0
Exp/Cntr=0.3,0.1

Type RM Length L Ch R = 1 ,30929.2 ,396.6,400,403.2
XS GIS Cut Line= 3
     1956006.137      279078.344     1956317.986       278812.78
     1956624.512      278540.124
#Sta/Elev= 30
       0    2203      40 2192.52    59.9 2182.32    79.9 2167.64    89.9 2156.43
    99.9 2148.21   279.7 2019.46   289.7 2012.11   309.7 1992.06   319.7  1984.6
   339.7 1975.17   379.6 1945.67   402.1 1926.89   409.6 1924.06   417.1 1925.54
   459.6 1939.13   479.6 1943.42   489.6 1949.19   499.7 1958.08   519.7 1982.72
   589.7 2048.23   599.7 2055.34   609.7 2058.83   629.7 2075.71   679.8 2111.88
   709.8 2129.36   719.8 2136.37   729.8  2146.4   749.8 2156.19   819.8 2207.94
#Mann= 3 , 0 , 0
       0      .1       0   402.1    .045       0   417.1      .1       0
Bank Sta=402.1,417.1
XS Rating Curve= 0 ,0
Exp/Cntr=0.3,0.1

Type RM Length L Ch R = 1 ,30529.2 ,396.5,399.9,403.9
XS GIS Cut Line= 3
     1956237.088       279321.48     1956591.259       279101.73
     1956932.939      278878.367
#Sta/Elev= 30
       0 2161.39    19.8 2150.48    79.4 2113.49    99.2 2095.95   148.9 2062.39
   178.6 2045.05   188.6 2033.77   228.2 2007.48     268 1983.42   287.8 1968.82
   327.5 1949.84   347.3 1942.41   377.1 1925.92     387 1914.12     397 1908.85
   406.9 1907.73   409.3 1908.08   424.3 1911.35   466.6 1924.61   486.5 1933.57
   506.4 1939.63   516.4 1943.87   566.2 1978.15   576.1 1988.27   586.1 1996.14
   625.9  2023.4   725.4 2094.76   755.3 2115.17   775.2 2132.76     825  2164.9
#Mann= 3 , 0 , 0
       0      .1       0   409.3    .045       0   424.3      .1       0
Bank Sta=409.3,424.3
XS Rating Curve= 0 ,0
Exp/Cntr=0.3,0.1

Type RM Length L Ch R = 1 ,30129.2 ,293.1,291.1,289.2
XS GIS Cut Line= 3
     1956341.132      279638.603     1956717.522      279477.293
     1957093.912      279315.984
#Sta/Elev= 30
       0 2244.89    59.9 2204.02    69.9 2190.04    79.9  2181.5   149.8 2130.51
   159.8  2117.2   209.7  2075.3   229.7 2056.62   249.7 2025.91   289.6 1991.86
   319.6  1969.5   329.6 1957.68   339.6 1948.51     402 1908.77   409.5 1904.64
     417  1903.7   419.5 1903.38   499.4  1918.5   529.4 1926.04   539.3 1930.24
   559.3 1941.15   579.3 1954.12   599.3 1973.56   669.2 2019.96   679.2 2029.32
   689.2 2035.46   719.1 2049.22   769.1 2076.17     779 2086.07     819 2113.76
#Mann= 3 , 0 , 0
       0      .1       0     402    .045       0     417      .1       0
Bank Sta=402,417
XS Rating Curve= 0 ,0
Exp/Cntr=0.3,0.1

Type RM Length L Ch R = 1 ,29838.1 ,335.2,329,322.9
XS GIS Cut Line= 3
     1956507.483      279917.525      1956899.21      279708.128
     1957219.363      279511.678
#Sta/Elev= 30
       0 2152.97    49.4 2122.76    69.1 2104.55   138.2 2062.13   148.1 2054.81
   157.9  2042.4   236.9 1987.59   246.8 1975.64   256.6 1967.62   325.7 1926.48
   345.5 1908.27   355.5 1903.59   365.2 1902.63   370.5 1903.36   454.1 1923.06
   473.8  1930.8   493.6 1942.46   523.3 1963.82   533.1 1976.68     543 1986.26
   612.2 2040.73   622.1 2050.46     632 2062.66   651.8 2075.02   701.2 2117.02
   711.1 2125.86     721 2141.11   730.8 2151.72   760.5 2174.36   819.8 2213.13
#Mann= 3 , 0 , 0
       0      .1       0   355.5    .045       0   370.5      .1       0
Bank Sta=355.5,370.5
XS Rating Curve= 0 ,0
Exp/Cntr=0.3,0.1

Type RM Length L Ch R = 1 ,29509   ,320.3,325.6,330.9
XS GIS Cut Line= 3
     1956730.678        280285.1     1957026.743      280002.193
     1957322.807      279719.287
#Sta/Elev= 30
       0 2129.26    79.9 2090.14    89.9 2083.84   109.9 2065.85   169.8  2024.4
   179.8 2017.72   199.8 2009.71   239.7  1982.3   309.6  1945.8   329.6 1938.75
   349.6  1924.9     402 1898.06   409.5 1896.43     417 1897.32   459.4  1905.4
   469.4 1908.05   479.4 1913.24   549.3 1966.54   569.3 1985.97   589.3 1994.51
   639.2 2032.53   659.2 2048.08   669.2 2058.79   689.2 2075.15   699.2 2081.84
   719.1 2089.45   759.1 2115.58   769.1 2122.36     789 2139.37     819 2160.59
#Mann= 3 , 0 , 0
       0      .1       0     402    .045       0     417      .1       0
Bank Sta=402,417
XS Rating Curve= 0 ,0
Exp/Cntr=0.3,0.1

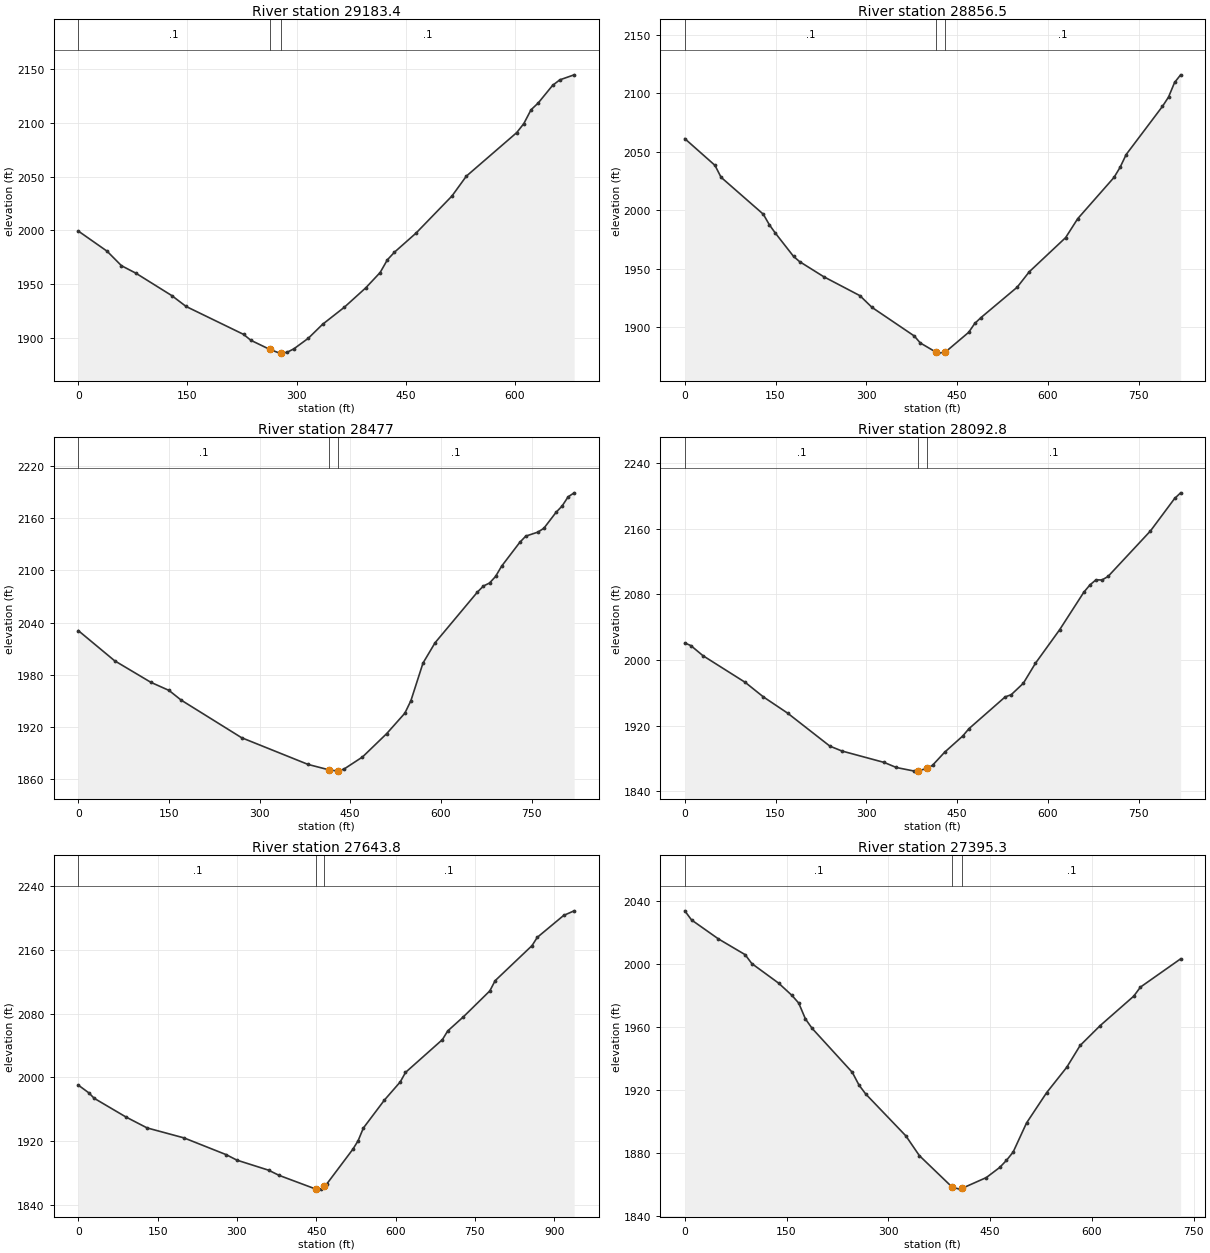
Type RM Length L Ch R = 1 ,29183.4 ,319.7,326.8,334.1
XS GIS Cut Line= 2
     1957010.697      280379.613     1957600.169      280037.463
#Sta/Elev= 30
       0 1999.31    39.5 1980.58    59.3 1967.06      79 1960.13   128.4 1939.25
   148.2 1929.08   227.2 1903.09   237.1 1897.63     263 1889.17   276.6 1885.65
     278 1885.74   286.5 1886.27   296.3 1889.64   316.1 1899.47   335.8 1912.51
   365.5 1928.28   395.1 1946.43   414.9 1960.72   424.8 1972.52   434.6 1979.66
   464.3 1997.46   513.6 2031.95   533.4 2050.45   602.6 2090.97   612.4 2099.39
   622.3 2112.24   632.2 2118.59   651.9 2134.94   661.8 2140.11   681.6 2144.81
#Mann= 3 , 0 , 0
       0      .1       0     263    .045       0     278      .1       0
Bank Sta=263,278
XS Rating Curve= 0 ,0
Exp/Cntr=0.3,0.1

Type RM Length L Ch R = 1 ,28856.5 ,391.2,379.5,367.5
XS GIS Cut Line= 3
     1956918.917      280651.377     1957317.504      280558.439
     1957719.339       280475.27
#Sta/Elev= 30
       0 2061.27    49.9 2038.45    59.9 2028.31   129.8 1996.73   139.8  1987.7
   149.7 1980.59   179.7 1960.76   189.7 1956.27   229.6 1943.37   289.5 1927.16
   309.4 1917.17   379.3 1892.74   389.3 1886.76   415.8 1878.74   419.3 1878.09
   430.8 1879.04   469.3 1895.88   479.3 1903.44   489.4 1908.36   549.4 1934.38
   569.4 1947.56   629.5 1976.74   649.5 1992.92   709.5 2028.16   719.5 2036.74
   729.6 2047.71   789.6 2088.86   799.6 2096.77   809.6 2109.24   819.6 2115.78
#Mann= 3 , 0 , 0
       0      .1       0   415.8    .045       0   430.8      .1       0
Bank Sta=415.8,430.8
XS Rating Curve= 0 ,0
Exp/Cntr=0.3,0.1

Type RM Length L Ch R = 1 ,28477   ,384.3,384.2,384.2
XS GIS Cut Line= 2
      1957185.64      281167.334     1957795.042       280617.82
#Sta/Elev= 30
       0  2030.8      60 1996.25   120.1 1971.47   150.1  1962.2   170.1 1951.12
   270.2 1907.94   380.3 1877.27   414.9 1871.06   429.9 1869.62   430.3  1869.6
   440.3 1872.24   470.3 1885.84   510.4 1912.68   540.4 1936.08   550.4 1950.42
   570.4 1993.53   590.4 2016.87   660.5 2075.03   670.5 2081.98   680.5 2085.39
   690.5 2092.91   700.5 2104.69   730.5 2131.98   740.5 2139.22   760.5 2143.79
   770.5 2148.24   790.6 2166.48   800.6 2173.73   810.6 2184.28   820.6 2188.89
#Mann= 3 , 0 , 0
       0      .1       0   414.9    .045       0   429.9      .1       0
Bank Sta=414.9,429.9
XS Rating Curve= 0 ,0
Exp/Cntr=0.3,0.1

Type RM Length L Ch R = 1 ,28092.8 ,433.8,448.9,463.8
XS GIS Cut Line= 3
     1957450.096      281444.707     1957752.452      281168.643
     1958060.331      280898.009
#Sta/Elev= 30
       0 2020.79      10 2017.62      30 2005.33    99.9 1972.81   129.8 1955.16
   169.8 1935.43   239.7 1895.21   259.6 1889.26   329.5 1875.33   349.5 1869.19
   379.5 1864.76   385.8 1865.15   400.8 1868.16   409.4 1871.91   429.4 1887.82
   459.4 1907.59   469.4 1916.36   529.4 1955.15   539.4 1957.84   559.4 1971.75
   579.4 1996.09   619.4 2036.93   659.4 2082.64   669.4 2091.45   679.4 2097.65
   689.4  2097.5   699.4 2101.81   769.4 2157.16   809.4 2196.76   819.3 2203.61
#Mann= 3 , 0 , 0
       0      .1       0   385.8    .045       0   400.8      .1       0
Bank Sta=385.8,400.8
XS Rating Curve= 0 ,0
Exp/Cntr=0.3,0.1

Type RM Length L Ch R = 1 ,27643.8 ,246.3,248.5,250.6
XS GIS Cut Line= 3
     1957601.731      281617.659      1957882.09      281511.143
     1958517.695      281457.322
#Sta/Elev= 30
       0 1990.27      20 1980.51      30 1973.74      90 1950.27     130 1936.52
   199.9 1923.96   279.9 1902.84   299.9 1896.02   359.7 1883.42   379.6 1876.91
   449.4 1859.58     450 1859.59   459.4 1859.81     465 1863.06   469.4 1865.61
   519.2 1909.69   529.2 1920.43   539.1 1936.36     579 1971.57   608.9 1994.34
   618.8 2006.23   688.6 2047.48   698.6 2058.36   728.5 2076.26   778.3 2108.73
   788.3 2121.52   858.1 2165.62     868 2175.98   917.9 2203.55   937.8 2209.35
#Mann= 3 , 0 , 0
       0      .1       0     450    .045       0     465      .1       0
Bank Sta=450,465
XS Rating Curve= 0 ,0
Exp/Cntr=0.3,0.1

Type RM Length L Ch R = 1 ,27395.3 ,485.2,458,430.7
XS GIS Cut Line= 2
     1957619.013      281740.249     1958349.824      281748.214
#Sta/Elev= 30
       0 2033.52     9.9 2027.74    49.4 2015.73    88.9 2005.69    98.8 2000.01
   138.3 1987.59     158 1979.77   167.9 1974.94   177.8 1964.86   187.6 1958.91
   246.9 1930.93   256.8 1922.83   266.7 1917.17   325.9 1890.56   345.7 1878.06
   394.1 1858.03   404.9 1856.77   409.1 1857.36   444.4 1864.11   464.2 1870.56
   474.1 1875.05   483.9 1880.27   503.7  1898.8   533.3 1918.03     563 1934.18
   582.7 1948.01   612.3 1960.65   661.7 1979.33   671.6 1985.08   730.8 2003.02
#Mann= 3 , 0 , 0
       0      .1       0   394.1    .045       0   409.1      .1       0
Bank Sta=394.1,409.1
XS Rating Curve= 0 ,0
Exp/Cntr=0.3,0.1