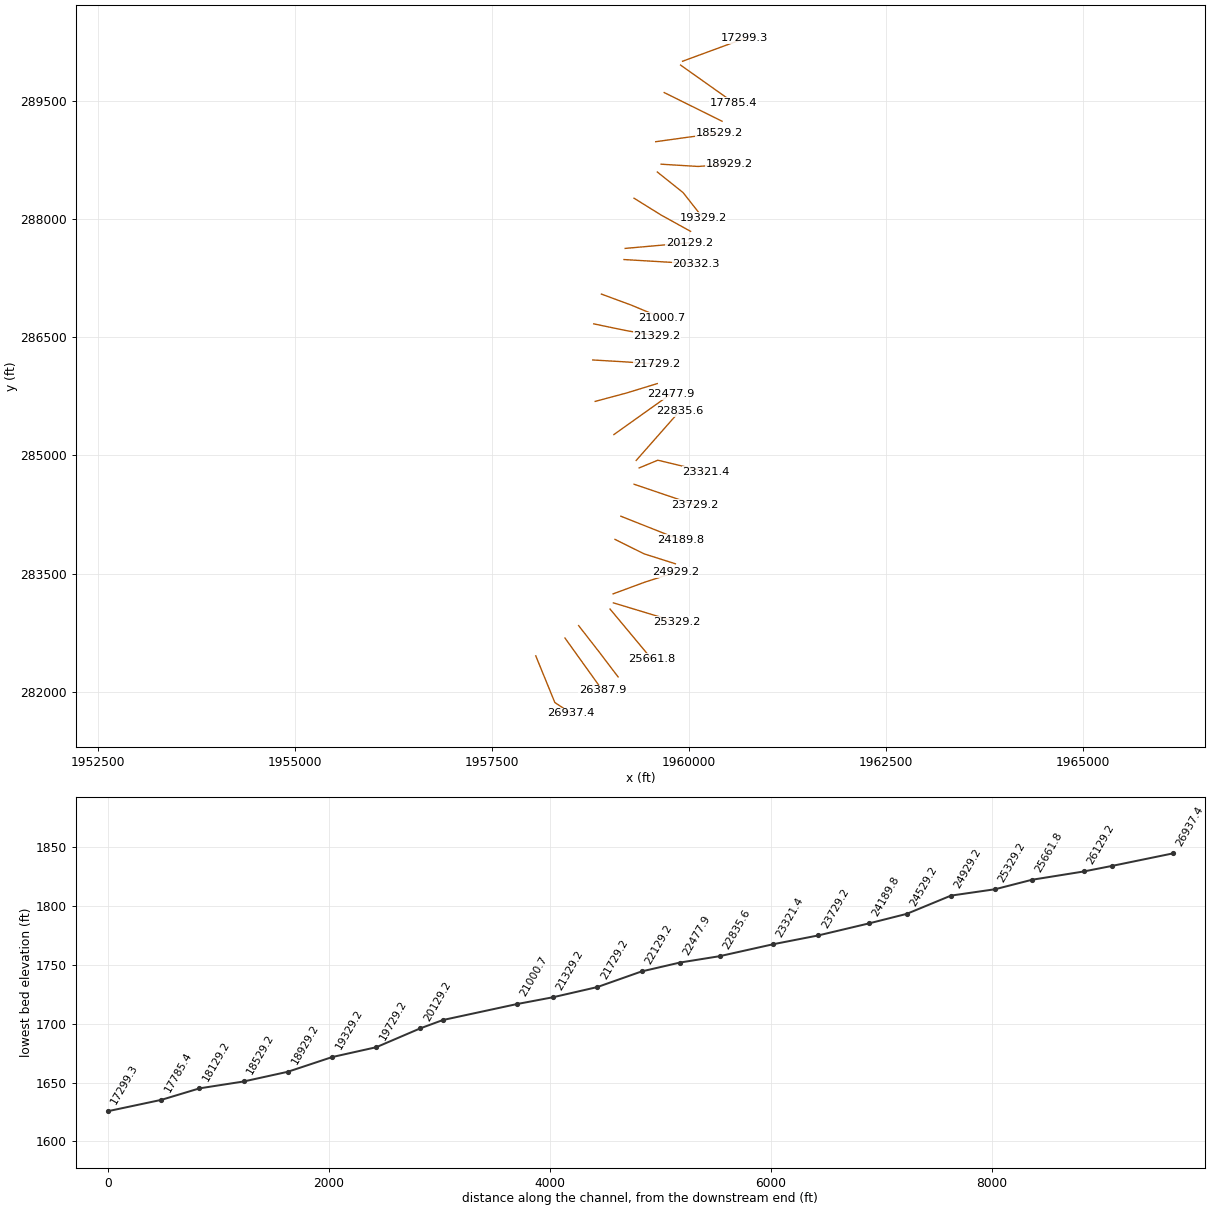
HEC-RAS study GldCrk.prj: GldCrk

--- GldCrk.g01 (geometry) --- (continued)

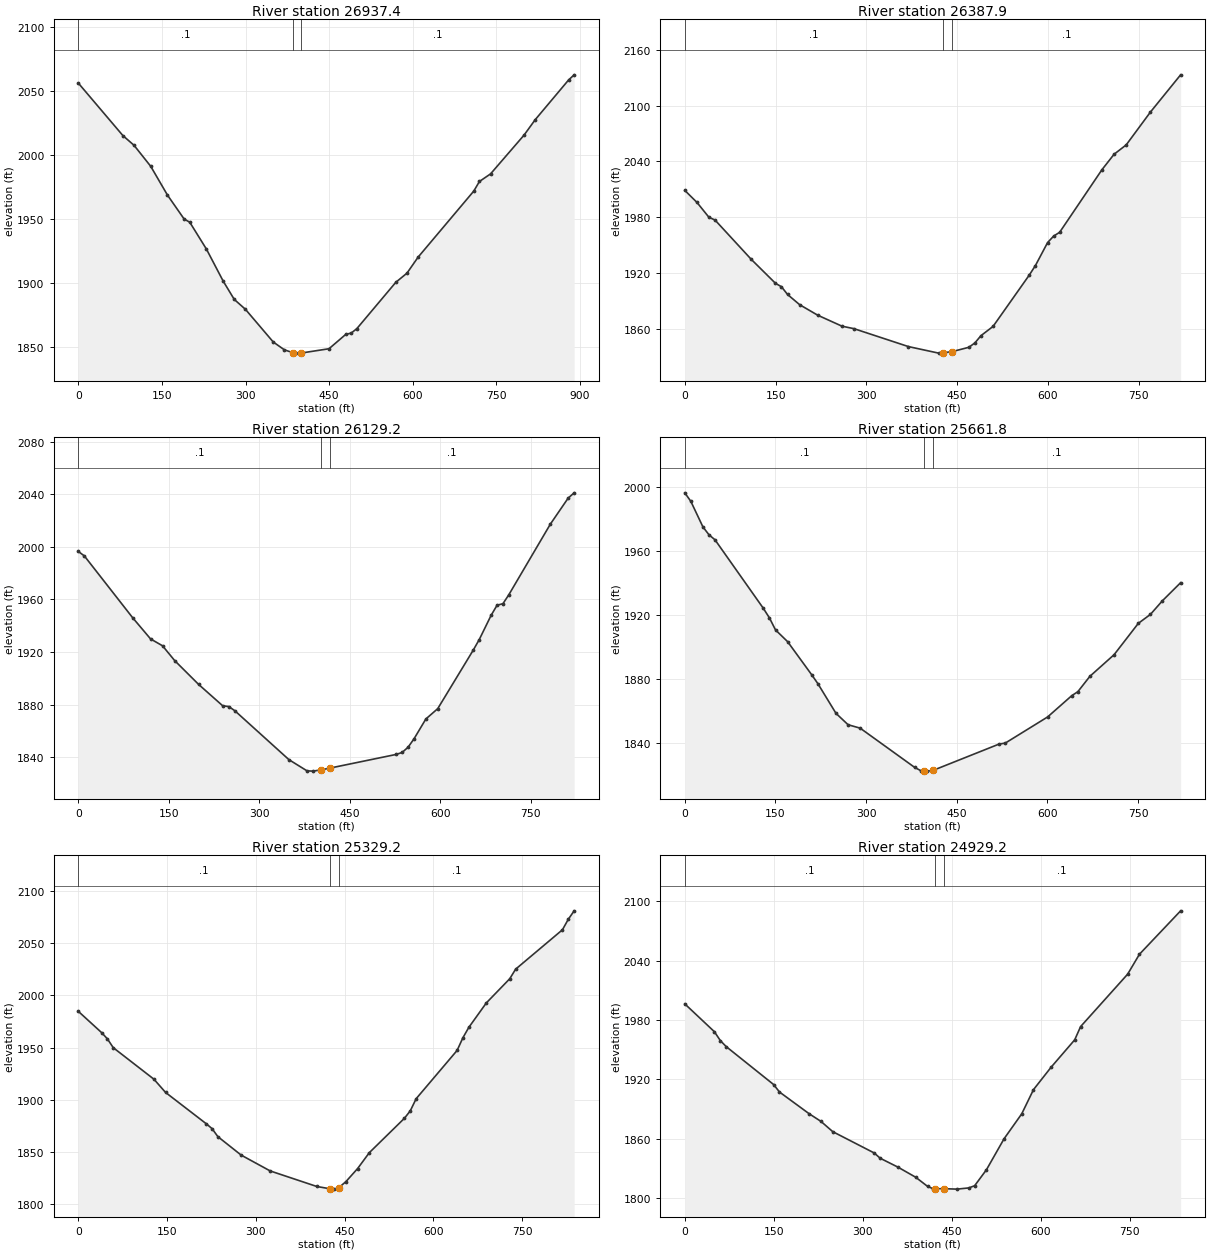
Type RM Length L Ch R = 1 ,26937.4 ,543.6,549.3,555
XS GIS Cut Line= 3
     1958058.932      282456.862     1958301.128      281864.827
     1958509.788      281727.099
#Sta/Elev= 30
       0 2055.82      80  2014.8     100 2007.21   129.9 1990.81   159.9 1968.37
   189.9  1949.6   199.9 1947.18   229.9 1926.12   259.9 1901.16   279.8 1886.85
   299.8 1879.14   349.8 1853.57   369.8 1847.46   385.3 1845.21   389.8  1844.9
   400.3    1845   449.8 1848.33   479.7 1859.48   489.7 1860.59   499.7    1864
   569.7 1900.23   589.7 1907.36   609.7 1919.88   709.7 1971.54   719.7 1978.97
   739.7 1984.91   799.7 2015.14   819.7 2027.17   879.7 2058.26   889.7 2062.28
#Mann= 3 , 0 , 0
       0      .1       0   385.3    .045       0   400.3      .1       0
Bank Sta=385.3,400.3
XS Rating Curve= 0 ,0
Exp/Cntr=0.3,0.1

Type RM Length L Ch R = 1 ,26387.9 ,257.7,258.6,259.3
XS GIS Cut Line= 3
     1958429.634      282683.139     1958668.078      282350.458
     1958906.995      282017.641
#Sta/Elev= 30
       0 2008.92      20  1996.1    39.9 1980.04    49.9 1977.14   109.8 1934.91
   149.8  1909.2   159.7 1905.53   169.7 1897.26   189.7 1886.28   219.6 1874.98
   259.6 1863.23   279.5 1860.53   369.4 1841.32   419.3  1834.3   426.9 1834.66
   441.9 1835.97   469.3 1840.58   479.2 1845.29   489.2 1853.03   509.2 1862.99
   569.2 1918.24   579.2 1928.33   599.2 1952.87   609.2 1959.86   619.2 1963.99
   689.1 2031.18   709.1 2047.72   729.1 2057.74     769 2092.88     819 2132.94
#Mann= 3 , 0 , 0
       0      .1       0   426.9    .045       0   441.9      .1       0
Bank Sta=426.9,441.9
XS Rating Curve= 0 ,0
Exp/Cntr=0.3,0.1

Type RM Length L Ch R = 1 ,26129.2 ,466.6,467.4,468.4
XS GIS Cut Line= 3
     1958603.172      282840.342     1958854.661      282517.918
      1959104.55      282189.266
#Sta/Elev= 30
       0 1996.46      10 1993.04    89.8 1946.22   119.7    1930   139.6 1924.75
   159.6 1913.56   199.5 1895.36   239.4 1879.13   249.3  1878.6   259.3 1875.45
   349.1 1838.22     379 1829.74     389 1829.52   401.4 1830.42   416.4 1831.76
   526.9 1842.22   536.7 1843.72   546.5 1847.67   556.4 1854.08     576 1869.14
   595.7    1877   654.7  1921.6   664.5 1929.49   684.2 1947.94     694 1955.58
   703.8 1956.77   713.6 1963.61   782.4 2017.25   811.9 2037.02   821.8    2041
#Mann= 3 , 0 , 0
       0      .1       0   401.4    .045       0   416.4      .1       0
Bank Sta=401.4,416.4
XS Rating Curve= 0 ,0
Exp/Cntr=0.3,0.1

Type RM Length L Ch R = 1 ,25661.8 ,319.5,332.6,345.8
XS GIS Cut Line= 2
     1959001.744      283050.922     1959527.028      282420.582
#Sta/Elev= 30
       0  1996.3      10 1990.97      30 1975.01      40  1970.1      50 1966.95
   130.1 1924.09   140.1 1918.15   150.1 1910.69   170.1 1903.36   210.1 1882.61
   220.1 1877.18   250.2 1858.57   270.2 1851.46   290.2 1849.32   380.2 1824.86
   390.2 1822.82   395.6 1822.64   400.2 1822.48   410.6 1822.91   520.3 1839.41
   530.3 1839.98   600.4 1856.32   640.4 1869.63   650.4 1872.08   670.4 1881.72
   710.4  1895.2   750.5 1914.78   770.5 1920.36   790.5 1928.93   820.5 1940.17
#Mann= 3 , 0 , 0
       0      .1       0   395.6    .045       0   410.6      .1       0
Bank Sta=395.6,410.6
XS Rating Curve= 0 ,0
Exp/Cntr=0.3,0.1

Type RM Length L Ch R = 1 ,25329.2 ,385.3,400,413.8
XS GIS Cut Line= 3
     1959044.448      283129.139      1959458.29      283004.034
     1959846.263      282886.344
#Sta/Elev= 30
       0 1984.76    39.3 1964.41    49.1  1958.4      59 1949.96   127.7 1919.77
   147.4 1907.08   216.2 1877.06     226 1872.39   235.8 1864.71   275.1 1847.06
   324.2 1831.87   402.9 1816.99   424.8 1814.84   432.3 1814.45   439.8 1815.71
   452.1 1821.62   471.9 1834.16   491.7 1849.39     551 1882.31   560.9 1889.46
   570.8 1901.06     640 1947.32   649.9 1959.54   659.8  1969.4   689.4 1992.83
     729 2016.02   738.9 2025.16     818  2062.9   827.9 2072.98   837.8 2081.06
#Mann= 3 , 0 , 0
       0      .1       0   424.8    .045       0   439.8      .1       0
Bank Sta=424.8,439.8
XS Rating Curve= 0 ,0
Exp/Cntr=0.3,0.1

Type RM Length L Ch R = 1 ,24929.2 ,419,400,385.5
XS GIS Cut Line= 3
     1959040.605      283243.099     1959443.084      283391.662
     1959830.157      283516.405
#Sta/Elev= 30
       0 1996.34    49.9 1968.17    59.9 1959.21    69.8 1953.12   149.7 1914.78
   159.6 1907.21   209.5 1885.29   229.5 1877.51   249.4 1867.12   319.3 1845.56
   329.2  1840.3   359.2 1831.27   389.1 1821.07   409.1 1811.83     419 1809.27
   421.5 1809.32   436.5 1809.48   458.8 1809.02   478.6 1810.24   488.5 1812.44
   508.4 1828.59   538.1 1859.93   567.9 1885.15   587.7 1909.61   617.5 1932.36
   657.2    1960   667.1 1973.35   746.4 2026.37   766.3 2046.52   835.7 2090.42
#Mann= 3 , 0 , 0
       0      .1       0   421.5    .045       0   436.5      .1       0
Bank Sta=421.5,436.5
XS Rating Curve= 0 ,0
Exp/Cntr=0.3,0.1

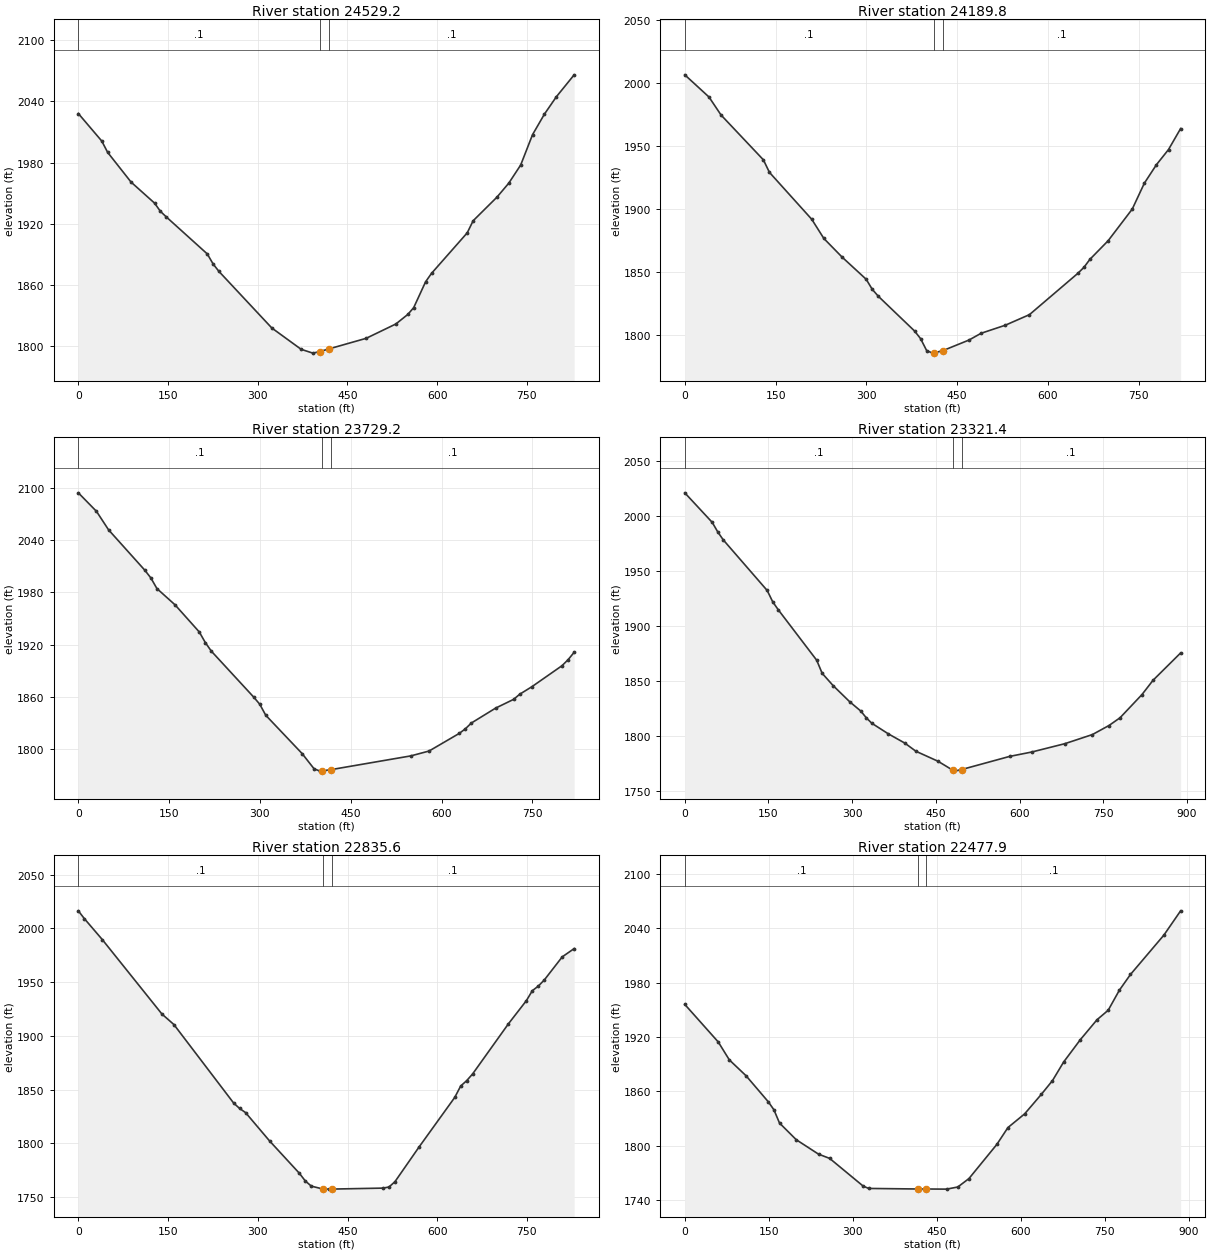
Type RM Length L Ch R = 1 ,24529.2 ,337.5,339.4,337.8
XS GIS Cut Line= 3
     1959064.796      283934.368     1959433.443       283751.14
     1959831.265       283625.02
#Sta/Elev= 30
       0    2028    39.2 2001.05      49    1990    88.2 1960.87   127.4 1940.34
   137.2  1932.3     147 1926.84   215.6 1890.59   225.4 1880.71   235.2  1873.4
   323.5  1818.1   372.5 1797.25   392.1  1793.5   404.2 1795.08   419.2 1797.67
   481.2 1807.98   530.9 1822.03   550.8 1831.34   560.7    1838   580.6 1863.29
   590.5 1871.56   650.2 1911.21   660.1 1923.04   699.8 1946.08   719.7 1959.85
   739.6  1977.6   759.4 2007.28   779.3 2027.42   799.2 2044.36     829 2065.87
#Mann= 3 , 0 , 0
       0      .1       0   404.2    .045       0   419.2      .1       0
Bank Sta=404.2,419.2
XS Rating Curve= 0 ,0
Exp/Cntr=0.3,0.1

Type RM Length L Ch R = 1 ,24189.8 ,459.4,460.6,461.7
XS GIS Cut Line= 3
     1959139.457      284227.923     1959520.162      284077.078
     1959900.866      283926.232
#Sta/Elev= 30
       0 2006.43      40 1988.79    59.9  1974.5   129.8 1938.93   139.8 1928.99
   209.7 1891.72   229.7 1876.49   259.7 1861.75   299.6  1844.1   309.6 1836.14
   319.6 1830.62   379.5 1803.03   389.5 1796.93   399.5 1787.47   409.5 1785.45
   411.1 1785.55   426.1  1787.4   469.4 1795.83   489.4 1801.21   529.4 1807.61
   569.3 1816.01   649.2 1848.79   659.2 1853.52   669.2 1859.94   699.2 1874.66
   739.1 1899.83   759.1  1920.4     779 1935.03     799 1947.11     819 1963.78
#Mann= 3 , 0 , 0
       0      .1       0   411.1    .045       0   426.1      .1       0
Bank Sta=411.1,426.1
XS Rating Curve= 0 ,0
Exp/Cntr=0.3,0.1

Type RM Length L Ch R = 1 ,23729.2 ,405.7,407.7,409.8
XS GIS Cut Line= 3
       1959307.5      284633.762     1959695.306      284502.245
     1960083.112      284370.727
#Sta/Elev= 30
       0 2094.02      30 2072.78    49.9 2051.66   109.9  2005.3   119.8  1996.5
   129.8 1984.36   159.8 1965.66   199.8  1934.6   209.7 1922.54   219.7 1912.62
   289.6 1860.05   299.6 1851.88   309.6 1839.19   369.6 1795.33   389.5 1777.76
   399.5 1775.18     402  1775.4     417 1776.84   549.3 1792.65   579.3  1798.2
   629.2 1818.39   639.2  1823.6   649.2 1830.29   689.2 1847.35   719.1 1857.44
   729.1  1863.3   749.1 1871.86     799    1896     809 1902.87     819 1911.32
#Mann= 3 , 0 , 0
       0      .1       0     402    .045       0     417      .1       0
Bank Sta=402,417
XS Rating Curve= 0 ,0
Exp/Cntr=0.3,0.1

Type RM Length L Ch R = 1 ,23321.4 ,461.2,485.8,510.4
XS GIS Cut Line= 3
     1959371.993      284841.019     1959608.646      284938.838
     1960223.894      284791.416
#Sta/Elev= 30
       0 2020.94    49.2 1994.03    59.1 1985.34    68.9 1978.15   147.7 1932.07
   157.6 1921.75   167.4 1914.62   236.4 1868.63   246.2 1856.71     266 1845.44
   295.6 1830.82   315.4 1822.39   325.3 1816.22   335.2 1811.26   364.8 1801.62
   394.5 1793.16   414.2  1785.8   453.8  1776.7     481 1768.33   483.4  1767.7
     496 1769.12   582.3  1781.1   621.8 1785.08   681.1 1792.66   730.6 1800.98
   760.2 1809.19     780  1816.2   819.5 1837.41   839.3  1850.4   888.7 1875.24
#Mann= 3 , 0 , 0
       0      .1       0     481    .045       0     496      .1       0
Bank Sta=481,496
XS Rating Curve= 0 ,0
Exp/Cntr=0.3,0.1

Type RM Length L Ch R = 1 ,22835.6 ,363.8,357.7,351.7
XS GIS Cut Line= 2
      1959333.47      284935.442     1959881.805      285557.084
#Sta/Elev= 30
       0 2016.44      10 2009.22      40 1989.73   139.8  1920.4   159.8 1910.62
   259.7 1837.56   269.6 1832.57   279.6  1828.7   319.6 1802.42   369.5 1772.27
   379.5 1765.07   389.5 1760.29     409 1757.61   419.4 1757.51     424 1757.55
   509.3 1758.46   519.3 1759.47   529.3 1764.42   569.3 1796.47   629.2 1842.79
   639.2 1853.42   649.2 1858.43   659.1 1864.64   719.1 1911.39     749 1932.85
     759 1942.14     769 1946.42     779 1952.12     809 1973.62   828.9 1981.31
#Mann= 3 , 0 , 0
       0      .1       0     409    .045       0     424      .1       0
Bank Sta=409,424
XS Rating Curve= 0 ,0
Exp/Cntr=0.3,0.1

Type RM Length L Ch R = 1 ,22477.9 ,356.7,348.5,341
XS GIS Cut Line= 2
     1959050.926      285264.227     1959772.673      285777.768
#Sta/Elev= 30
       0 1956.09    59.7 1914.67    79.6 1894.81   109.5 1877.28   149.3 1848.46
   159.2 1839.74   169.2 1825.11   199.1  1806.7   238.9 1790.74   258.8 1786.05
   318.5 1755.55   328.4 1752.88   416.8 1752.26   431.8 1752.26   467.8 1752.12
   487.7 1754.46   507.6 1763.75   557.4 1801.43   577.3 1820.12   607.1  1835.2
     637 1856.81   656.9 1871.98   676.8 1892.48   706.6 1917.12   736.5 1939.21
   756.4 1949.65   776.3 1971.71   796.2 1989.16   855.9 2032.62   885.8 2059.43
#Mann= 3 , 0 , 0
       0      .1       0   416.8    .045       0   431.8      .1       0
Bank Sta=416.8,431.8
XS Rating Curve= 0 ,0
Exp/Cntr=0.3,0.1

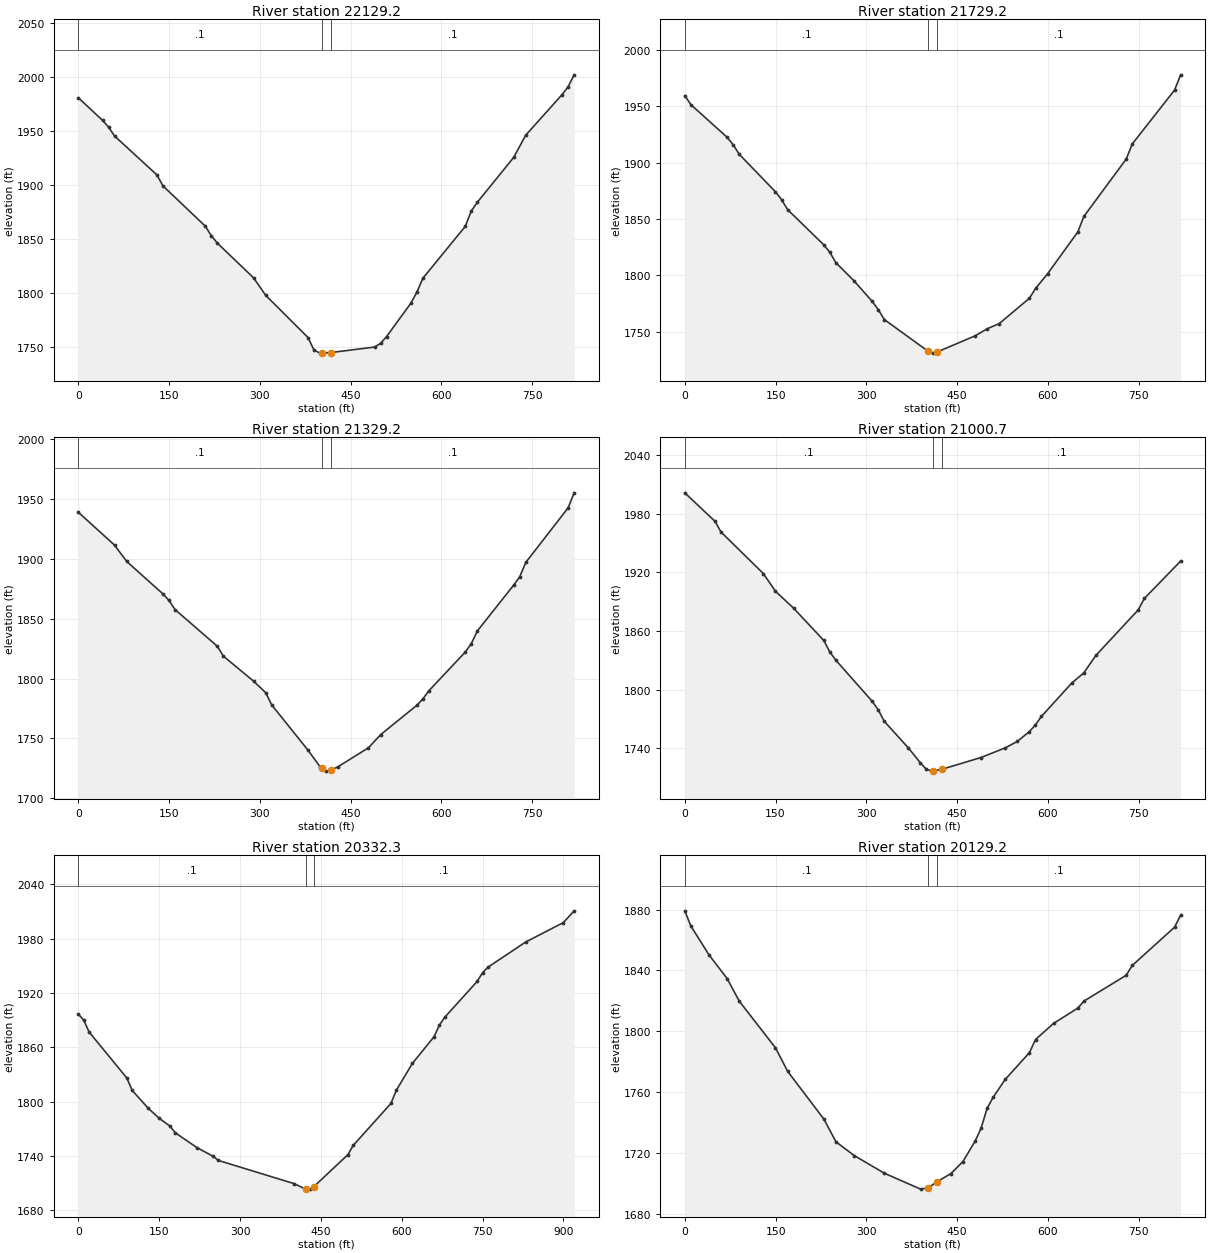
Type RM Length L Ch R = 1 ,22129.2 ,407.2,400,391.7
XS GIS Cut Line= 3
     1958813.835      285685.032     1959209.378      285790.818
     1959601.278      285910.653
#Sta/Elev= 30
       0 1980.72      40 1959.84    49.9 1953.58    59.9 1945.35   129.8 1909.39
   139.8 1899.26   209.7 1862.01   219.7  1853.2   229.7 1846.27   289.6 1814.15
   309.6    1798   379.5 1758.96   389.5  1747.3   399.5 1744.53   401.9 1744.58
   416.9 1745.04   489.4 1750.14   499.4 1753.54   509.4  1759.9   549.4 1790.63
   559.4 1800.93   569.4 1813.84   639.3 1861.72   649.3 1875.94   659.3 1884.05
   719.3  1925.5   739.3 1946.12   799.3 1983.62   809.3 1990.86   819.3 2001.94
#Mann= 3 , 0 , 0
       0      .1       0   401.9    .045       0   416.9      .1       0
Bank Sta=401.9,416.9
XS Rating Curve= 0 ,0
Exp/Cntr=0.3,0.1

Type RM Length L Ch R = 1 ,21729.2 ,403.3,400,397.6
XS GIS Cut Line= 3
     1958782.599      286210.327     1959191.442      286186.496
     1959599.924       286157.73
#Sta/Elev= 30
       0 1959.25      10 1951.28    69.9 1922.32    79.9 1915.79    89.9 1907.33
   149.8 1874.07   159.8 1867.22   169.8 1858.32   229.7 1827.08   239.7 1820.39
   249.7 1811.25   279.7 1795.17   309.6 1776.99   319.6 1769.77   329.6 1760.97
     402  1732.9   409.5 1731.26     417 1732.32   479.4 1746.53   499.4 1752.81
   519.4 1757.41   569.3 1779.87   579.3 1788.48   599.3 1801.57   649.2 1838.58
   659.2 1852.28   729.1 1903.04   739.1 1916.42     809 1964.14     819 1977.64
#Mann= 3 , 0 , 0
       0      .1       0     402    .045       0     417      .1       0
Bank Sta=402,417
XS Rating Curve= 0 ,0
Exp/Cntr=0.3,0.1

Type RM Length L Ch R = 1 ,21329.2 ,332.1,328.4,323.5
XS GIS Cut Line= 3
     1958794.831      286668.478     1959195.772      286585.356
     1959599.094       286513.39
#Sta/Elev= 30
       0 1939.06    59.9 1911.56    79.9 1897.94   139.8 1870.77   149.8 1865.32
   159.8 1857.67   229.7 1827.01   239.7 1818.74   289.6 1797.82   309.6 1788.22
   319.6 1777.94   379.5 1740.11   399.5 1726.22     402 1725.32   409.5 1722.62
     417 1723.23   429.4  1726.4   479.4 1742.17   499.4 1753.08   559.4 1777.72
   569.4 1783.12   579.3 1789.91   639.3 1822.16   649.3 1829.26   659.3 1839.86
   719.2 1878.11   729.2 1885.02   739.2 1897.07   809.2 1942.73   819.2  1955.3
#Mann= 3 , 0 , 0
       0      .1       0     402    .045       0     417      .1       0
Bank Sta=402,417
XS Rating Curve= 0 ,0
Exp/Cntr=0.3,0.1

Type RM Length L Ch R = 1 ,21000.7 ,661,668.3,676.1
XS GIS Cut Line= 3
     1958892.208      287046.288     1959276.286      286904.475
     1959654.558      286746.491
#Sta/Elev= 30
       0 2001.31    49.9 1972.19    59.9  1961.2   129.8  1918.8   149.8 1900.73
   179.8 1883.37   229.7 1850.38   239.7 1838.58   249.6 1830.23   309.6 1788.24
   319.6 1779.54   329.5 1767.85   369.5 1740.52   389.4 1725.25   399.4 1718.62
   409.4 1716.79   410.8 1716.93   425.8 1718.85   489.4  1730.7   529.4 1740.54
   549.4  1747.1   569.4 1757.18   579.4 1764.03   589.4 1772.75   639.4 1806.77
   659.4 1817.23   679.4 1835.11   749.4 1881.69   759.4 1893.29   819.4 1931.53
#Mann= 3 , 0 , 0
       0      .1       0   410.8    .045       0   425.8      .1       0
Bank Sta=410.8,425.8
XS Rating Curve= 0 ,0
Exp/Cntr=0.3,0.1

Type RM Length L Ch R = 1 ,20332.3 ,199.8,203.2,206.5
XS GIS Cut Line= 2
     1959178.956      287484.256     1960097.309      287429.998
#Sta/Elev= 30
       0 1896.48      10 1889.95      20 1876.77      90 1825.96     100  1812.2
     130 1792.37     150 1781.53     170 1772.82     180 1765.43     220 1749.13
     250 1739.55     260 1734.91     400 1709.37   421.7 1703.27     430 1703.25
   436.7 1705.83     500 1741.22     510 1751.52     580 1797.86     590 1812.44
     620 1842.22     660 1871.53     670 1884.38     680 1893.14     740 1932.67
     750 1942.26     760 1948.32     830 1976.15     900 1997.63     920 2010.61
#Mann= 3 , 0 , 0
       0      .1       0   421.7    .045       0   436.7      .1       0
Bank Sta=421.7,436.7
XS Rating Curve= 0 ,0
Exp/Cntr=0.3,0.1

Type RM Length L Ch R = 1 ,20129.2 ,414.5,399.9,386.5
XS GIS Cut Line= 3
     1959193.894      287625.606     1959601.786      287661.866
     1960009.677      287698.125
#Sta/Elev= 30
       0 1879.24      10 1869.28      40 1850.24    69.9 1834.73    89.9 1819.86
   149.8 1789.16   169.8 1773.76   229.7 1742.29   249.7 1727.33   279.7 1718.33
   329.6 1706.68   389.5 1696.22     402 1697.04     417 1701.19   439.5 1706.42
   459.4 1714.34   479.4 1727.67   489.4 1736.24   499.4 1749.45   509.4 1756.66
   529.4 1768.45   569.3    1786   579.3 1794.61   609.3 1805.24   649.2 1815.27
   659.2 1819.86   729.1 1836.85   739.1 1843.31     809 1868.48     819 1876.43
#Mann= 3 , 0 , 0
       0      .1       0     402    .045       0     417      .1       0
Bank Sta=402,417
XS Rating Curve= 0 ,0
Exp/Cntr=0.3,0.1

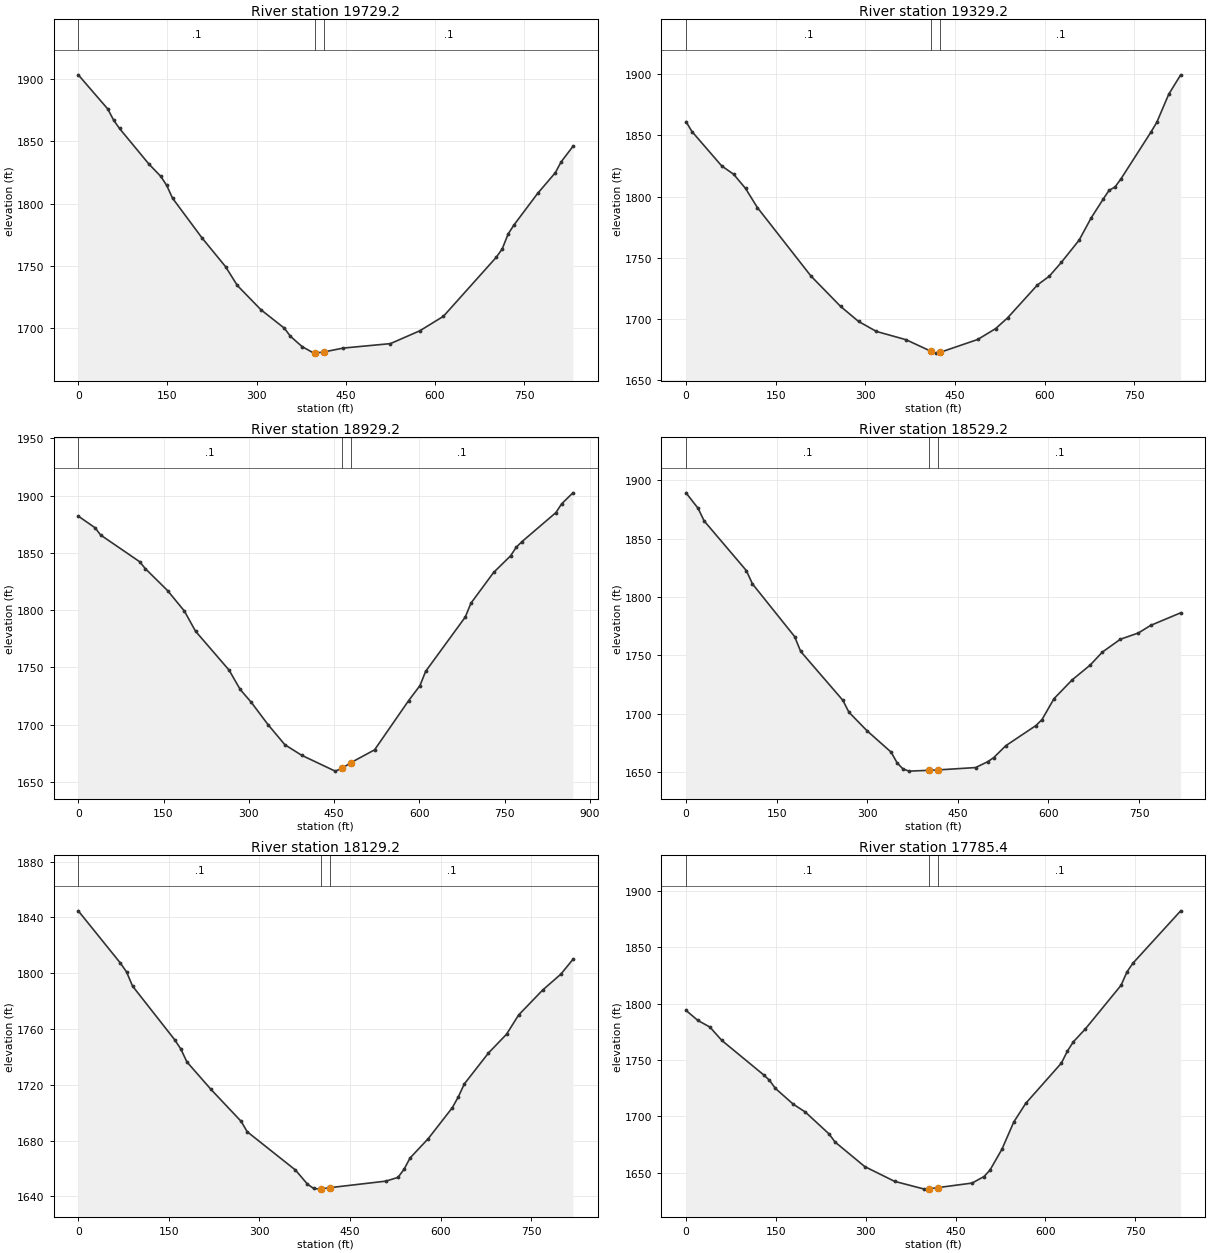
Type RM Length L Ch R = 1 ,19729.2 ,402.1,399.6,390.5
XS GIS Cut Line= 3
     1959306.409      288262.672     1959651.496      288048.084
     1960024.316      287842.194
#Sta/Elev= 30
       0 1903.28    49.6 1875.92    59.5 1866.95    69.4 1860.25   118.9 1831.71
   138.8 1821.89   148.7 1814.68   158.6 1804.38   208.1 1772.57   247.8 1749.47
   267.6  1734.4   307.2 1714.97   346.9 1700.06   356.8 1693.71   376.6 1685.36
   396.4 1680.12   398.9 1680.18   413.9 1681.13     446 1684.18   525.2 1687.74
   574.7 1698.04   614.4 1709.65   703.5 1757.09   713.4 1763.76   723.3 1775.67
   733.2 1782.95   772.8 1808.13   802.6 1824.72   812.4 1833.44   832.3 1845.92
#Mann= 3 , 0 , 0
       0      .1       0   398.9    .045       0   413.9      .1       0
Bank Sta=398.9,413.9
XS Rating Curve= 0 ,0
Exp/Cntr=0.3,0.1

Type RM Length L Ch R = 1 ,19329.2 ,386.3,400,422.1
XS GIS Cut Line= 3
      1959602.33      288594.749     1959928.938      288333.964
     1960182.328      288012.215
#Sta/Elev= 30
       0 1861.28      10 1853.15    59.7 1825.02    79.6 1818.25    99.5 1806.64
   119.4 1790.92     209 1734.86   258.7 1709.94   288.6  1697.7   318.4 1689.52
   368.2  1682.7   410.4 1673.11     418 1671.74   425.4 1672.45   487.9 1682.91
   517.8 1691.78   537.8 1700.56   587.8 1727.54   607.7 1734.73   627.7 1745.96
   657.7 1764.34   677.7 1782.46   697.6 1797.67   707.6 1804.99   717.6 1807.78
   727.6 1814.46   777.6 1852.63   787.5 1860.73   807.5 1883.73   827.5 1899.64
#Mann= 3 , 0 , 0
       0      .1       0   410.4    .045       0   425.4      .1       0
Bank Sta=410.4,425.4
XS Rating Curve= 0 ,0
Exp/Cntr=0.3,0.1

Type RM Length L Ch R = 1 ,18929.2 ,395.1,399.8,401.3
XS GIS Cut Line= 3
     1959649.841      288694.011      1960120.38      288665.234
      1960517.94      288693.631
#Sta/Elev= 30
       0 1882.17    29.5 1871.98    39.3 1865.65     108 1842.29   117.8 1836.31
   157.1 1817.06   186.6 1799.18   206.2  1781.6   265.2 1747.57   284.8 1730.65
   304.5 1719.27   333.9  1699.8   363.4 1682.33   392.8 1673.16   451.8 1659.26
   463.9 1661.67   478.9 1666.52   521.2 1677.89     581 1720.88     601 1734.03
   610.9 1746.43   680.7 1793.97   690.6 1806.03   730.5 1832.91   760.4 1847.45
   770.4 1855.03   780.3 1859.82   840.1 1885.24   850.1 1892.87     870 1902.51
#Mann= 3 , 0 , 0
       0      .1       0   463.9    .045       0   478.9      .1       0
Bank Sta=463.9,478.9
XS Rating Curve= 0 ,0
Exp/Cntr=0.3,0.1

Type RM Length L Ch R = 1 ,18529.2 ,413.4,400,386.7
XS GIS Cut Line= 3
     1959581.765       288979.21     1959987.332      289035.786
     1960393.547      289087.802
#Sta/Elev= 30
       0 1889.22      20 1875.91      30 1865.17    99.9 1822.65   109.9 1811.33
   179.8 1766.19   189.8 1753.48   259.7 1711.61   269.7 1701.42   299.6  1685.6
   339.6 1667.24   349.6 1657.99   359.6  1652.7   369.5    1651     402 1651.69
     417 1652.03   479.4 1654.05   499.4 1659.06   509.4 1662.55   529.4 1672.75
   579.3    1690   589.3 1695.08   609.3 1713.05   639.2 1729.05   669.2  1741.8
   689.2 1752.85   719.1 1763.88   749.1 1769.29   769.1  1775.7     819 1786.52
#Mann= 3 , 0 , 0
       0      .1       0     402    .045       0     417      .1       0
Bank Sta=402,417
XS Rating Curve= 0 ,0
Exp/Cntr=0.3,0.1

Type RM Length L Ch R = 1 ,18129.2 ,347.3,343.8,340.3
XS GIS Cut Line= 3
     1959690.096       289602.46     1960057.065      289420.735
     1960424.034      289239.011
#Sta/Elev= 30
       0 1844.65    69.9 1807.11    79.9 1800.88    89.9 1790.69   159.8 1752.14
   169.8 1745.59   179.8 1736.39   219.7 1716.65   269.7 1693.72   279.7 1686.29
   359.6 1658.84   379.5 1648.72   389.5  1645.7   399.5 1645.15     402 1645.28
     417 1646.22   509.4 1650.89   529.4 1653.58   539.3 1659.31   549.3 1667.45
   579.3 1681.28   619.2 1703.46   629.2 1711.26   639.2 1720.58   679.2 1742.75
   709.1  1756.2   729.1 1769.99   769.1 1787.95     799 1799.24     819 1809.86
#Mann= 3 , 0 , 0
       0      .1       0     402    .045       0     417      .1       0
Bank Sta=402,417
XS Rating Curve= 0 ,0
Exp/Cntr=0.3,0.1

Type RM Length L Ch R = 1 ,17785.4 ,464.2,486.1,508.1
XS GIS Cut Line= 2
     1959897.481      289951.195     1960571.577      289474.085
#Sta/Elev= 30
       0 1793.97    19.9 1785.04    39.8 1779.22    59.7 1767.37   129.4 1736.88
   139.3 1732.02   149.2 1724.78   179.1 1710.73     199 1703.88   238.8 1684.37
   248.8 1677.21   298.5 1655.37   348.2 1642.31     398  1635.4   406.4 1635.65
   421.4 1636.81   477.6 1640.78   497.5 1646.57   507.4  1652.2   527.4 1670.77
   547.2 1694.94   567.2 1711.52   626.8 1747.29   636.8 1757.94   646.8 1766.17
   666.7 1777.52   726.4 1816.31   736.3 1828.24   746.3 1835.95   825.9 1882.34
#Mann= 3 , 0 , 0
       0      .1       0   406.4    .045       0   421.4      .1       0
Bank Sta=406.4,421.4
XS Rating Curve= 0 ,0
Exp/Cntr=0.3,0.1

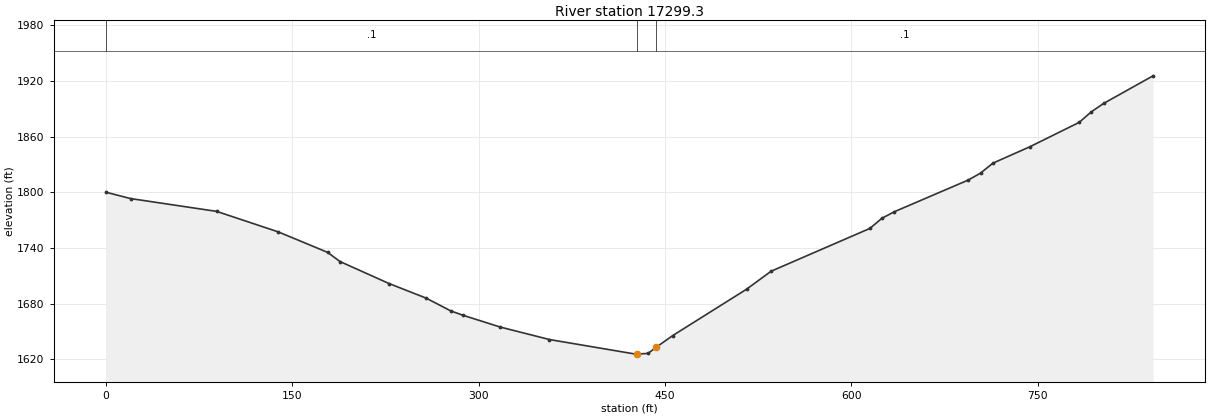
Type RM Length L Ch R = 1 ,17299.3 ,378.5,370,359.5
XS GIS Cut Line= 2
     1959922.461       290000.04      1960713.58      290290.622
#Sta/Elev= 30
       0 1800.08    19.8 1793.24    89.2 1779.41   138.8  1757.3   178.5 1735.27
   188.4 1725.41     228 1701.66   257.8 1685.98   277.6 1672.23   287.5 1667.51
   317.3 1654.89     357 1641.41   426.4  1625.7   427.8 1625.81   436.3 1626.47
   442.8 1632.98   456.1 1645.59   515.6 1695.58   535.4 1714.99   614.8 1761.03
   624.7  1772.1   634.6 1779.06   694.1 1813.19     704 1820.69   713.9 1831.35
   743.6    1849   783.3 1875.24   793.2 1886.72   803.1 1895.75   842.8 1925.41
#Mann= 3 , 0 , 0
       0      .1       0   427.8    .045       0   442.8      .1       0
Bank Sta=427.8,442.8
XS Rating Curve= 0 ,0
Exp/Cntr=0.3,0.1