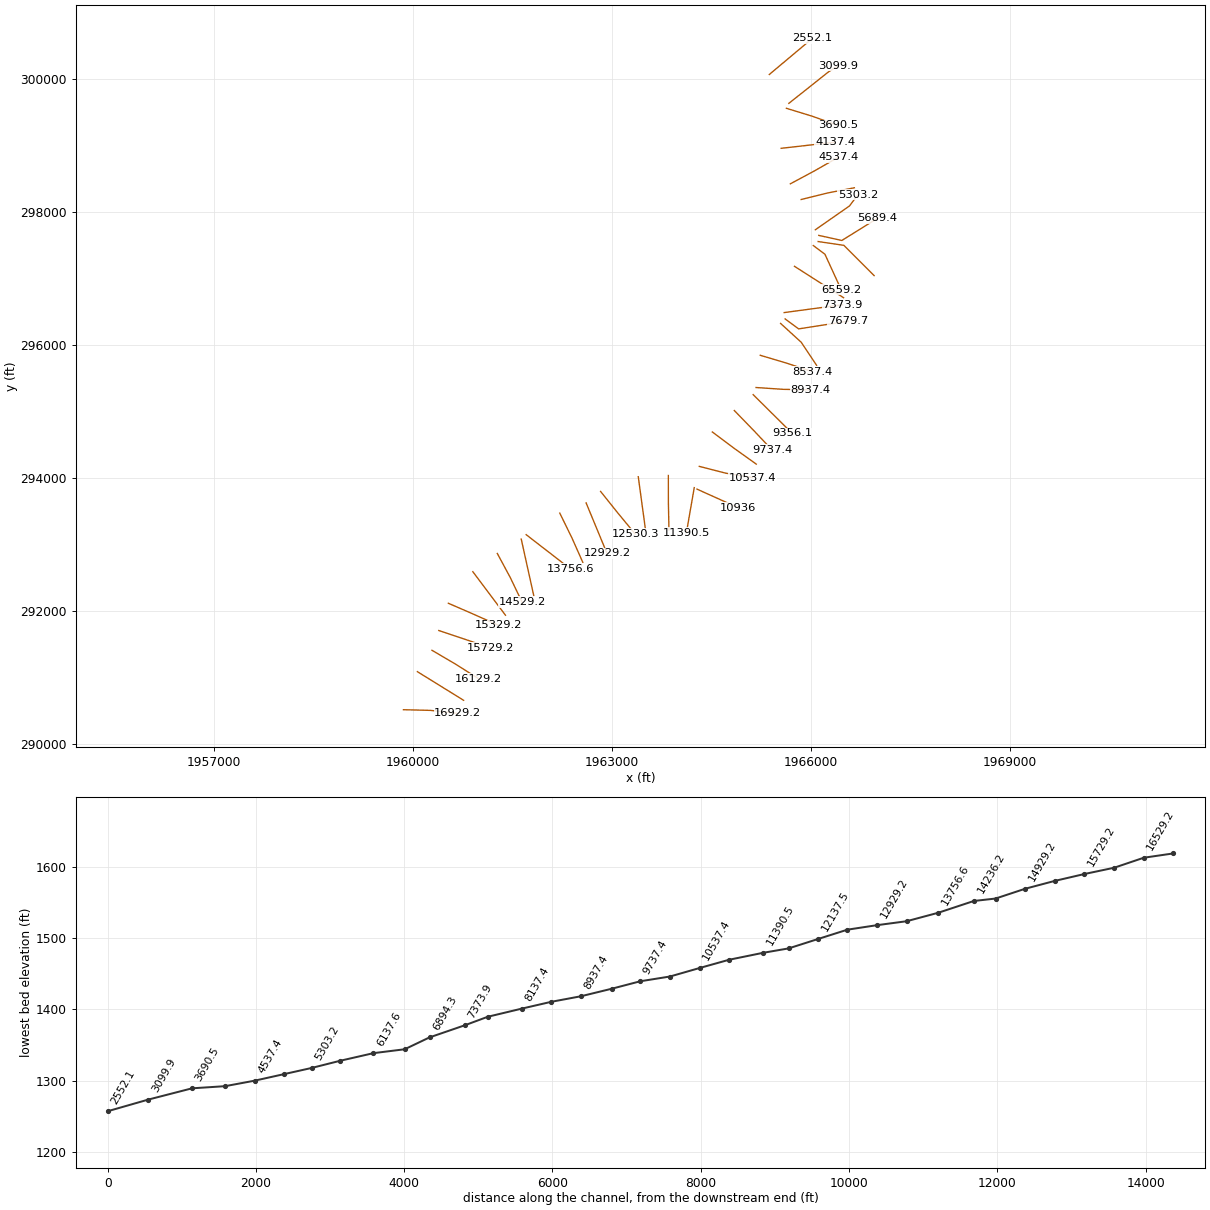
HEC-RAS study GldCrk.prj: GldCrk

--- GldCrk.g01 (geometry) --- (continued)

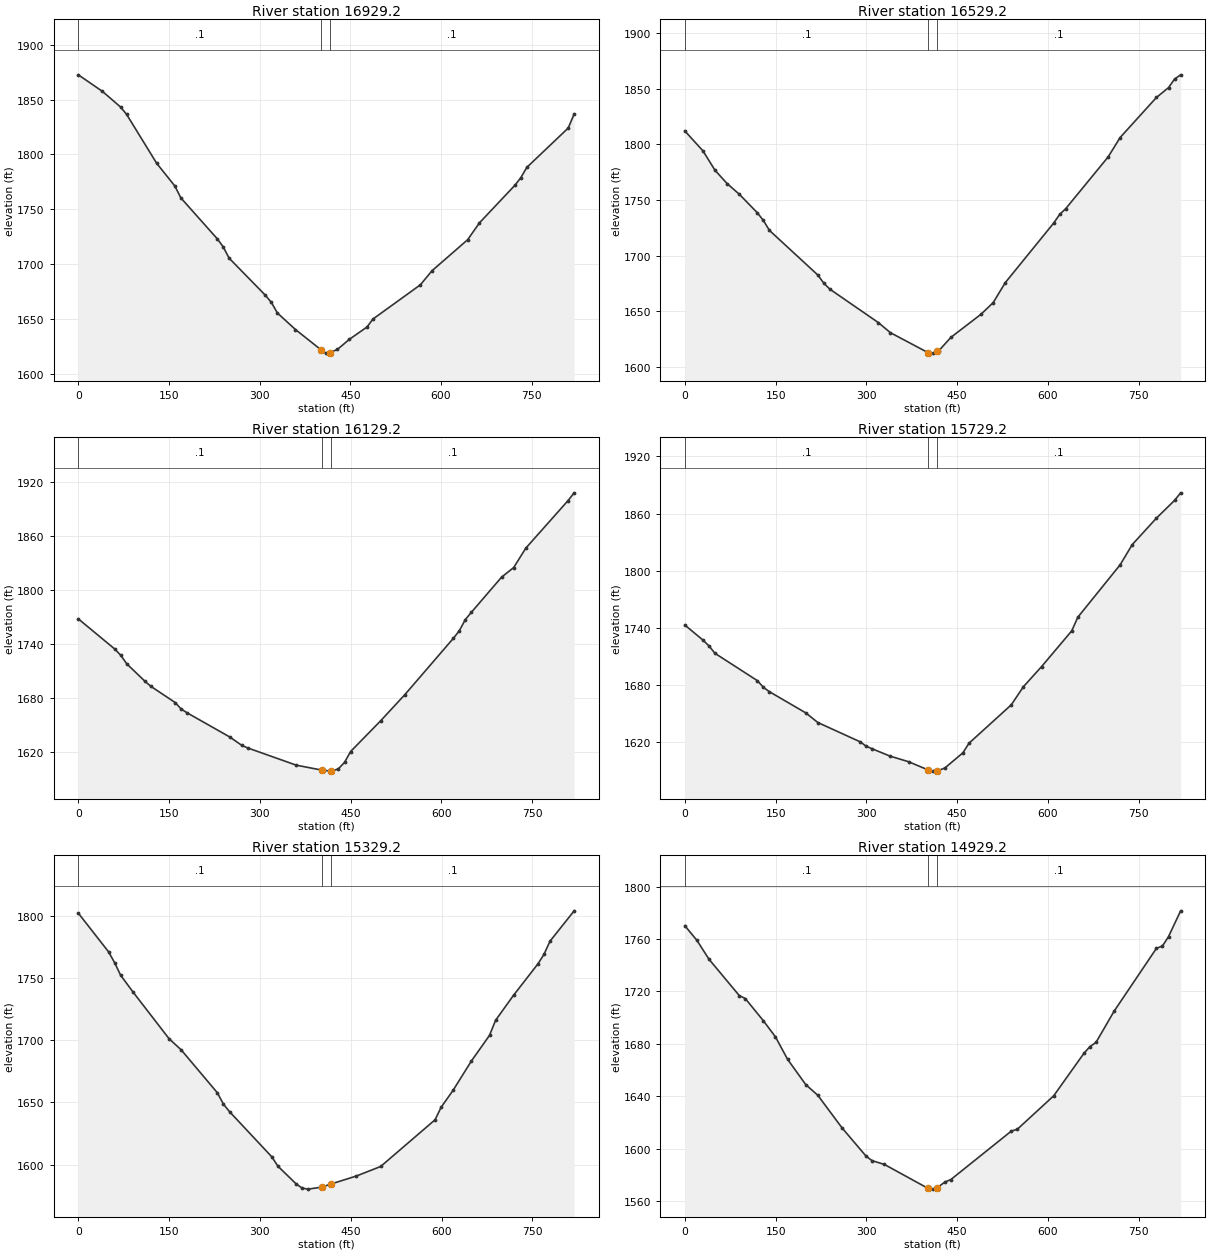
Type RM Length L Ch R = 1 ,16929.2 ,411.9,400,390
XS GIS Cut Line= 3
     1959852.994      290515.995     1960262.053       290505.77
     1960670.871      290460.894
#Sta/Elev= 30
       0 1872.53    39.9 1857.43    69.9 1843.16    79.8 1836.53   129.7 1791.81
   159.7 1771.14   169.7 1760.26   229.5 1723.24   239.5 1715.86   249.5 1705.34
   309.4 1671.57   319.4 1664.98   329.4 1655.33   359.3 1640.23   401.7 1621.71
   409.2 1618.71   416.7 1619.23   428.8 1622.09   448.4 1631.26   477.7 1642.54
   487.5 1649.78   565.9 1680.96   585.4  1693.9   644.2 1722.11   663.8 1737.54
   722.5 1771.82   732.3 1778.78   742.1 1788.06   810.7 1824.02   820.5 1836.82
#Mann= 3 , 0 , 0
       0      .1       0   401.7    .045       0   416.7      .1       0
Bank Sta=401.7,416.7
XS Rating Curve= 0 ,0
Exp/Cntr=0.3,0.1

Type RM Length L Ch R = 1 ,16529.2 ,399.3,399.8,399.6
XS GIS Cut Line= 3
     1960062.586      291088.377     1960410.987      290873.188
     1960759.389      290657.999
#Sta/Elev= 30
       0 1811.97      30 1794.06    49.9 1776.66    69.9 1764.72    89.9 1755.22
   119.8 1738.56   129.8 1731.63   139.8 1722.74   219.7 1682.73   229.7  1675.3
   239.7 1669.98   319.6 1640.09   339.6    1631     402 1613.04   409.5 1612.65
     417 1614.19   419.5  1614.7   439.5 1626.78   489.4 1647.57   509.4 1657.94
   529.4 1675.91   609.3 1729.29   619.2 1737.06   629.2 1742.23   699.2 1788.57
   719.1 1806.05     779 1841.94     799 1850.77     809 1858.47     819 1862.27
#Mann= 3 , 0 , 0
       0      .1       0     402    .045       0     417      .1       0
Bank Sta=402,417
XS Rating Curve= 0 ,0
Exp/Cntr=0.3,0.1

Type RM Length L Ch R = 1 ,16129.2 ,395.2,399.9,405.3
XS GIS Cut Line= 3
       1960282.3      291410.259     1960635.963       291202.93
     1960982.538      290984.961
#Sta/Elev= 30
       0 1768.11      60 1734.64      70 1727.68      80 1718.08     110  1698.7
     120 1692.95     160 1674.98     170  1667.7     180 1663.42     250 1636.72
     270 1627.36     280  1624.4     360 1605.28   402.5 1599.72   417.5 1598.64
   419.9 1598.61   429.9 1601.34   439.9 1608.28   449.9 1620.39   499.8 1654.78
   539.8  1683.9   619.7 1746.41   629.6 1754.85   639.6 1767.38   649.6 1775.48
   699.5 1814.58   719.5 1825.28   739.5 1846.85   809.4 1899.88   819.4 1908.43
#Mann= 3 , 0 , 0
       0      .1       0   402.5    .045       0   417.5      .1       0
Bank Sta=402.5,417.5
XS Rating Curve= 0 ,0
Exp/Cntr=0.3,0.1

Type RM Length L Ch R = 1 ,15729.2 ,401.8,399.9,397.7
XS GIS Cut Line= 3
     1960385.493      291707.362     1960773.832      291577.427
     1961162.171      291447.491
#Sta/Elev= 30
       0  1743.1      30 1727.29      40 1721.11    49.9 1713.36   119.8 1684.76
   129.8 1677.73   139.8 1673.12   199.8 1650.94   219.7 1640.82   289.6 1620.59
   299.6 1615.97   309.6  1613.2   339.6 1605.44   369.6  1599.7     402 1591.05
   409.5 1589.82     417    1590   429.5 1593.07   459.4 1609.05   469.4 1619.08
   539.3 1659.37   559.3 1678.38   589.3 1699.46   639.2 1737.01   649.2 1751.28
   719.1 1806.24   739.1 1827.45     779 1855.19     809 1873.81     819 1881.74
#Mann= 3 , 0 , 0
       0      .1       0     402    .045       0     417      .1       0
Bank Sta=402,417
XS Rating Curve= 0 ,0
Exp/Cntr=0.3,0.1

Type RM Length L Ch R = 1 ,15329.2 ,411.6,399.9,388.4
XS GIS Cut Line= 3
     1960529.464      292117.338     1960905.301      291954.756
     1961279.343      291788.001
#Sta/Elev= 30
       0 1802.43    49.9 1771.33    59.9 1762.59    69.9 1752.42    89.9 1739.21
   149.8 1701.36   169.8  1692.4   229.7 1657.74   239.7  1648.6   249.7 1642.59
   319.6 1606.17   329.6 1598.68   359.6 1584.48   369.5 1581.02   379.5 1580.17
     402 1581.77     417 1584.24   459.4 1590.74   499.4 1598.41   589.3 1636.05
   599.3 1646.13   619.2  1659.9   649.2 1683.32   679.2 1704.03   689.2 1716.13
   719.1 1736.46   759.1 1761.54   769.1 1769.22   779.1 1779.87     819 1804.32
#Mann= 3 , 0 , 0
       0      .1       0     402    .045       0     417      .1       0
Bank Sta=402,417
XS Rating Curve= 0 ,0
Exp/Cntr=0.3,0.1

Type RM Length L Ch R = 1 ,14929.2 ,403.4,400,395.6
XS GIS Cut Line= 3
     1960899.155      292592.309     1961145.046      292264.853
     1961390.938      291937.396
#Sta/Elev= 30
       0 1770.21      20 1759.01      40 1744.57    89.9  1716.9    99.9 1714.59
   129.8 1697.65   149.8 1685.31   169.8  1668.2   199.8 1648.92   219.7 1640.77
   259.7 1615.89   299.6 1594.23   309.6 1590.82   329.6 1588.03     402 1569.67
   409.5 1569.15     417 1570.24   429.5 1574.55   439.5 1576.47   539.3 1613.42
   549.3 1614.86   609.3 1640.35   659.2 1672.74   669.2 1677.94   679.2 1681.08
   709.1 1704.92     779 1752.87     789 1754.71     799 1761.83     819 1781.53
#Mann= 3 , 0 , 0
       0      .1       0     402    .045       0     417      .1       0
Bank Sta=402,417
XS Rating Curve= 0 ,0
Exp/Cntr=0.3,0.1

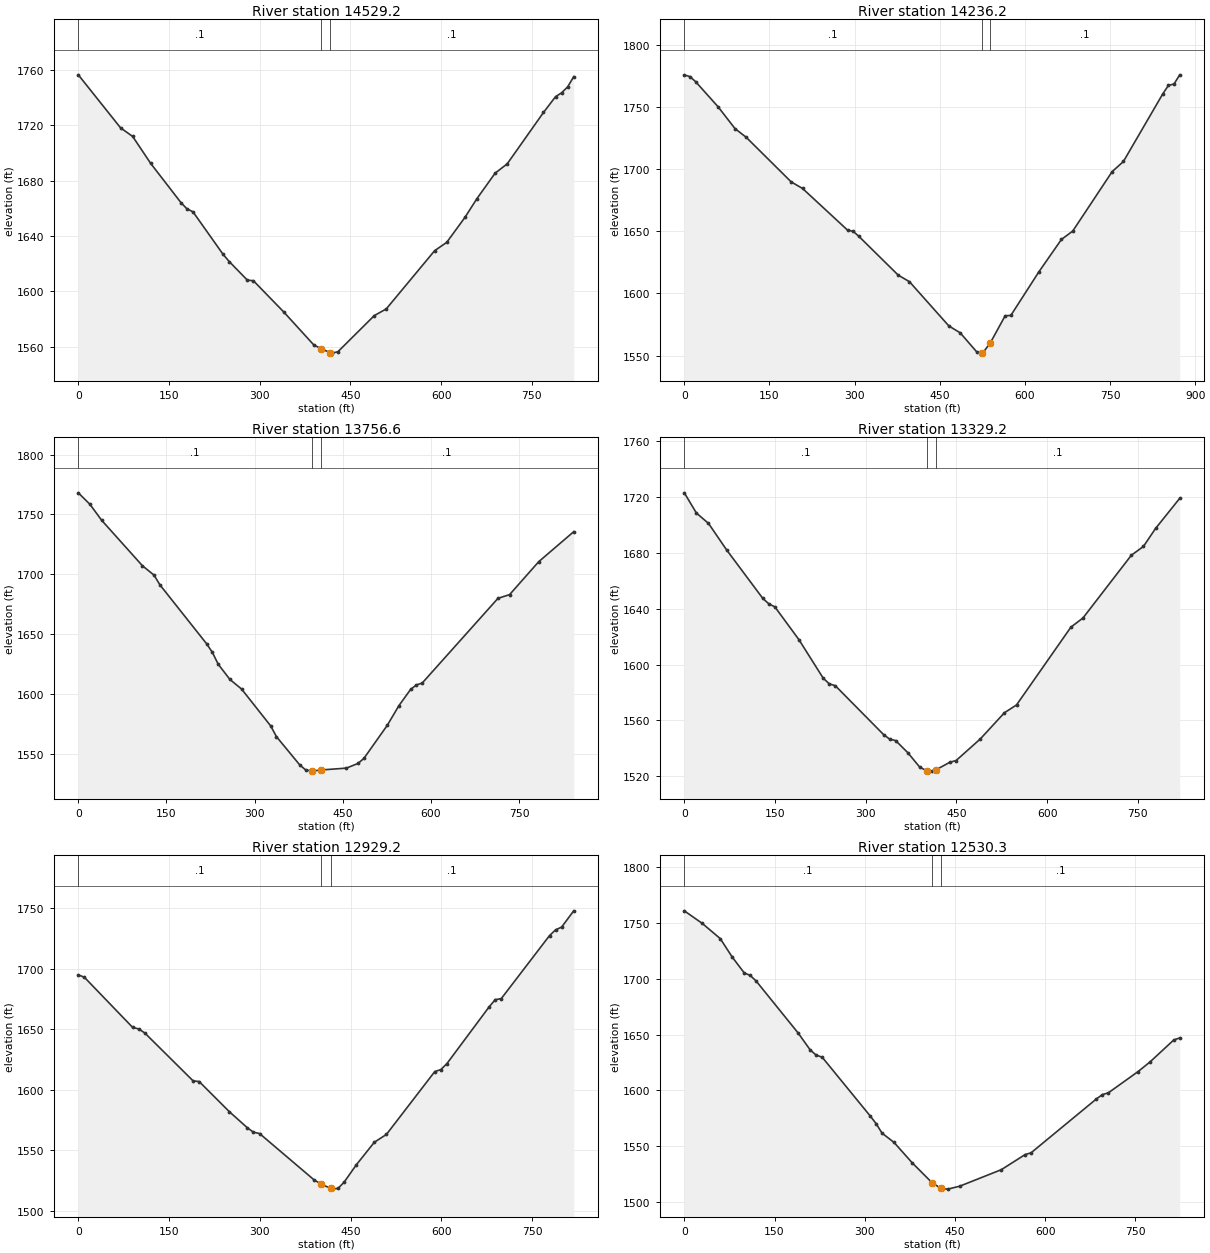
Type RM Length L Ch R = 1 ,14529.2 ,299.2,293,287.8
XS GIS Cut Line= 3
     1961268.219      292866.025     1961462.658       292505.74
     1961640.303      292136.174
#Sta/Elev= 30
       0  1756.4    69.9  1718.1    89.9 1711.89   119.8 1692.37   169.8 1664.09
   179.7 1659.61   189.7 1657.45   239.6 1626.65   249.6 1621.55   279.6 1608.11
   289.6 1607.68   339.5 1585.26   389.4 1561.35   401.9 1558.49   416.9 1555.74
   419.4 1555.39   429.4  1556.4   489.4 1582.44   509.4 1587.35   589.4  1629.4
   609.4  1635.4   639.4 1653.38   659.4 1667.03   689.4 1685.36   709.4  1692.1
   769.4 1729.23   789.4 1740.64   799.4 1743.42   809.4  1747.7   819.4 1755.09
#Mann= 3 , 0 , 0
       0      .1       0   401.9    .045       0   416.9      .1       0
Bank Sta=401.9,416.9
XS Rating Curve= 0 ,0
Exp/Cntr=0.3,0.1

Type RM Length L Ch R = 1 ,14236.2 ,463.8,479.5,495.2
XS GIS Cut Line= 2
     1961628.798      293082.381     1961817.884      292230.352
#Sta/Elev= 30
       0 1775.87     9.9 1774.59    19.8 1770.54    59.5 1750.27    89.3 1732.72
   109.1 1725.68   188.4 1689.76   208.3 1684.53   287.6 1650.98   297.5 1650.02
   307.4 1646.03   376.9 1614.74   396.7 1609.45   466.1 1573.83     486 1568.34
   515.7 1552.69   524.2 1552.06   525.6 1551.96   539.2 1560.28   565.3 1582.05
   575.2 1582.26   624.8 1617.49   664.5 1643.52   684.3  1650.2   753.8 1698.08
   773.6 1706.22     843 1760.67   852.9 1767.46   862.8 1768.63   872.8 1775.99
#Mann= 3 , 0 , 0
       0      .1       0   524.2    .045       0   539.2      .1       0
Bank Sta=524.2,539.2
XS Rating Curve= 0 ,0
Exp/Cntr=0.3,0.1

Type RM Length L Ch R = 1 ,13756.6 ,437.5,427.1,416
XS GIS Cut Line= 2
      1961703.14      293148.892     1962370.564      292634.043
#Sta/Elev= 30
       0 1767.99    19.8 1758.38    39.7 1745.07   109.1 1707.06   128.9 1699.21
   138.8 1691.13   218.2 1641.94   228.1  1634.7     238 1624.82   257.8 1612.13
   277.7 1604.09   327.2 1573.33   337.2 1564.23   376.8 1540.63   386.8 1536.49
   396.7 1535.46   397.4 1535.49   412.4  1536.4   456.2 1537.98     476 1541.91
   485.9  1546.1   525.6 1573.67   545.4  1590.1   565.3 1603.68   575.2  1607.5
   585.1 1609.04     714 1679.82   733.8 1682.93   783.4 1710.47   842.9 1735.52
#Mann= 3 , 0 , 0
       0      .1       0   397.4    .045       0   412.4      .1       0
Bank Sta=397.4,412.4
XS Rating Curve= 0 ,0
Exp/Cntr=0.3,0.1

Type RM Length L Ch R = 1 ,13329.2 ,401.4,400,399.4
XS GIS Cut Line= 3
     1962209.794      293473.456     1962390.225      293105.914
     1962557.325      292731.698
#Sta/Elev= 30
       0 1723.13      20 1708.64      40 1701.22    69.9 1682.24   129.8 1647.43
   139.8 1643.51   149.8 1641.34   189.7 1617.75   229.7 1590.22   239.7 1586.18
   249.7 1584.82   329.6 1549.75   339.5 1546.56   349.5 1545.46   369.5 1536.84
   389.5 1526.35   401.9 1523.64   409.4 1523.56   416.9 1524.68   439.4 1529.96
   449.4 1531.13   489.4 1546.58   529.4 1565.42   549.4 1571.01   639.4 1626.82
   659.3 1633.37   739.3 1678.36   759.3 1684.68   779.3 1697.55   819.3 1719.18
#Mann= 3 , 0 , 0
       0      .1       0   401.9    .045       0   416.9      .1       0
Bank Sta=401.9,416.9
XS Rating Curve= 0 ,0
Exp/Cntr=0.3,0.1

Type RM Length L Ch R = 1 ,12929.2 ,392.3,398.8,405.6
XS GIS Cut Line= 3
     1962606.674      293627.025     1962763.577      293248.777
      1962920.48      292870.528
#Sta/Elev= 30
       0 1695.02      10 1693.05    89.9 1651.58    99.9 1650.37   109.9 1647.02
   189.8 1607.45   199.8 1606.91   249.7    1582   279.7 1568.61   289.6 1565.05
   299.6 1563.97   389.5 1525.78     402    1522     417 1518.74   419.5 1518.03
   429.5 1518.68   439.5 1523.83   459.4 1537.98   489.4 1556.76   509.4 1563.22
   589.3 1615.14   599.3 1616.75   609.3 1621.67   679.2  1668.6   689.2 1674.53
   699.2 1675.38     779 1727.46     789 1732.22     799 1734.48     819 1747.92
#Mann= 3 , 0 , 0
       0      .1       0     402    .045       0     417      .1       0
Bank Sta=402,417
XS Rating Curve= 0 ,0
Exp/Cntr=0.3,0.1

Type RM Length L Ch R = 1 ,12530.3 ,405.1,392.8,380.3
XS GIS Cut Line= 3
     1962824.627      293800.373     1963079.903      293481.455
     1963344.688      293161.703
#Sta/Elev= 30
       0 1760.68    29.9 1749.41    59.8 1735.81    79.7  1719.3    99.6 1705.17
   109.6 1702.88   119.6 1697.78   189.3 1651.37   209.2 1636.33   219.2 1631.62
   229.2 1629.76   308.9 1577.29   318.8 1570.39   328.8 1561.79   348.7 1553.52
   378.6 1535.44   411.7 1517.58   426.7 1512.41   438.2 1511.72   457.9 1514.35
   527.1 1529.12   566.7 1542.65   576.5 1544.18   685.3 1592.46   695.2 1596.31
     705 1597.85   754.5 1616.89   774.2 1625.44   813.8 1645.16   823.7    1647
#Mann= 3 , 0 , 0
       0      .1       0   411.7    .045       0   426.7      .1       0
Bank Sta=411.7,426.7
XS Rating Curve= 0 ,0
Exp/Cntr=0.3,0.1

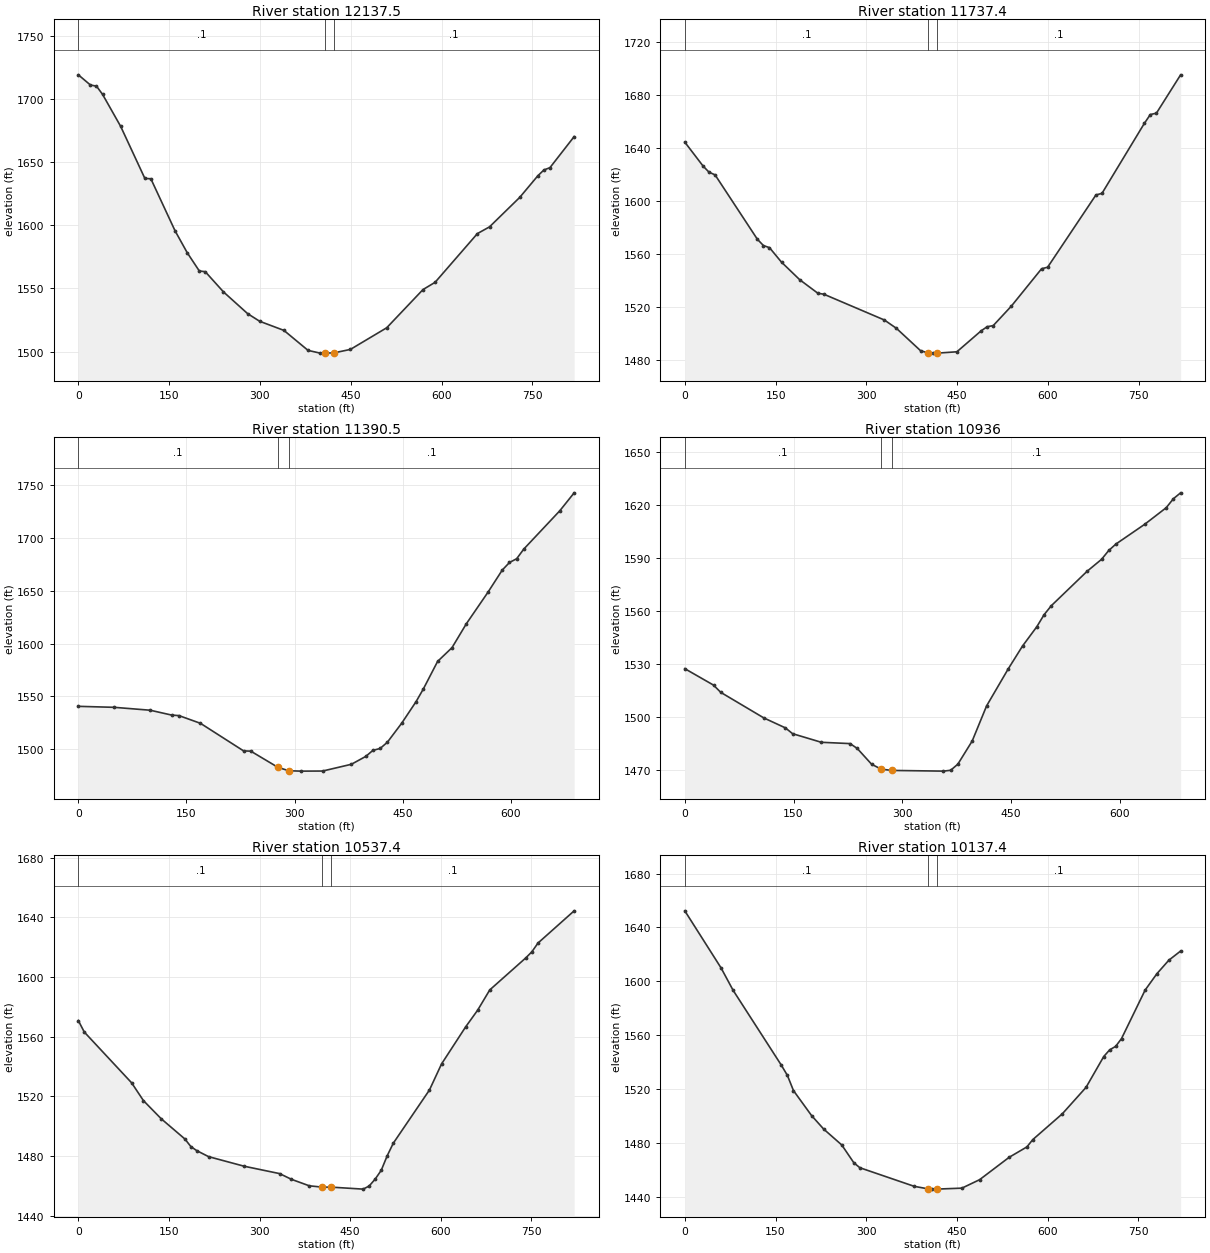
Type RM Length L Ch R = 1 ,12137.5 ,403.1,400.1,397.5
XS GIS Cut Line= 3
     1963393.069      294020.736      1963448.52      293615.008
     1963503.972      293209.279
#Sta/Elev= 30
       0 1718.95      20 1710.88      30    1710      40  1703.5    69.9 1678.19
   109.9 1636.96   119.8 1636.71   159.8  1595.5   179.8 1578.24   199.8 1563.75
   209.7 1563.16   239.7  1547.2   279.7 1529.95   299.6 1523.92   339.6 1516.72
   379.5 1500.88   399.5 1498.73   406.8 1498.78   421.8 1498.88   449.4 1501.67
   509.4  1518.8   569.3 1549.02   589.3 1554.77   659.2 1593.32   679.2 1598.65
   729.1 1621.97   759.1 1639.12   769.1 1643.69     779 1645.48     819 1670.08
#Mann= 3 , 0 , 0
       0      .1       0   406.8    .045       0   421.8      .1       0
Bank Sta=406.8,421.8
XS Rating Curve= 0 ,0
Exp/Cntr=0.3,0.1

Type RM Length L Ch R = 1 ,11737.4 ,350.8,346.9,342.5
XS GIS Cut Line= 3
     1963846.344      294039.185     1963847.283      293629.594
     1963856.075      293220.205
#Sta/Elev= 30
       0 1644.36      30 1626.45      40 1621.72      50 1619.71   119.9  1571.2
   129.9 1566.46   139.9 1564.89   159.8 1553.93   189.8 1540.75   219.8 1530.55
   229.8  1529.8   329.7 1510.39   349.6 1504.12   389.6 1487.22   402.1 1485.59
   409.6 1485.44   417.1 1485.44   449.5 1486.45   489.5 1502.21   499.5 1505.33
   509.5 1506.16   539.4 1520.81   589.4 1548.99   599.4 1550.14   679.2 1604.59
   689.2 1605.77   759.2 1658.51   769.1 1665.16   779.1 1666.16   819.1 1695.05
#Mann= 3 , 0 , 0
       0      .1       0   402.1    .045       0   417.1      .1       0
Bank Sta=402.1,417.1
XS Rating Curve= 0 ,0
Exp/Cntr=0.3,0.1

Type RM Length L Ch R = 1 ,11390.5 ,424.4,454.5,484.5
XS GIS Cut Line= 2
     1964237.283      293856.953     1964119.206      293179.473
#Sta/Elev= 30
       0  1540.6    49.8 1539.66    99.7 1536.91   129.6 1532.29   139.5 1531.83
   169.4 1524.51   229.2 1498.38   239.2 1498.14     277 1482.74     292 1479.56
     309 1479.21   338.9  1479.3   378.7 1485.69   398.7 1493.16   408.6  1498.9
   418.6 1500.68   428.6 1506.56   448.5 1524.61   468.4 1545.01   478.4  1556.9
   498.3 1583.15   518.3 1596.21   538.2 1618.88   568.1 1648.66     588 1669.74
     598  1676.9     608 1680.48   617.9 1689.65   667.8 1725.91   687.7  1742.9
#Mann= 3 , 0 , 0
       0      .1       0     277    .045       0     292      .1       0
Bank Sta=277,292
XS Rating Curve= 0 ,0
Exp/Cntr=0.3,0.1

Type RM Length L Ch R = 1 ,10936   ,394.7,398.6,404.5
XS GIS Cut Line= 2
      1964278.29      293834.172     1964901.991      293553.684
#Sta/Elev= 30
       0  1527.5    39.6  1518.2    49.6  1514.1     109 1499.64   138.8    1494
   148.7 1490.72   188.3 1485.86     228 1485.12   237.9 1482.36   257.7 1473.43
   271.1 1470.63   286.1 1469.94   356.8 1469.55   366.7 1470.03   376.6 1473.48
   396.4 1486.57   416.3 1506.46     446  1527.3   465.8 1540.28   485.6 1551.25
   495.6 1558.03   505.5 1563.08     555 1582.61   574.8 1589.32   584.8 1594.35
   594.7 1597.99   634.3 1609.13     664 1618.51     674 1623.63   683.9 1626.94
#Mann= 3 , 0 , 0
       0      .1       0   271.1    .045       0   286.1      .1       0
Bank Sta=271.1,286.1
XS Rating Curve= 0 ,0
Exp/Cntr=0.3,0.1

Type RM Length L Ch R = 1 ,10537.4 ,408.8,400,389.7
XS GIS Cut Line= 3
     1964313.421      294176.352     1964712.019      294073.938
     1965115.903      294008.577
#Sta/Elev= 30
       0 1570.82     9.8 1563.17    88.2 1529.14   107.8 1517.21   137.2 1505.07
   176.4 1491.52   186.2 1486.48     196 1483.73   215.6 1479.71   274.4  1473.3
   333.2 1468.35   352.8 1464.52   382.2 1460.19     404 1459.28     419 1459.28
   471.4 1457.96   481.4 1460.05   491.4  1464.7   501.4 1470.58   511.3 1480.35
   521.3 1488.69   581.2 1524.35   601.2 1541.78   641.1  1566.6     661  1577.8
     681 1591.34   740.8 1612.84   750.8 1616.92   760.8 1622.71   820.7  1644.3
#Mann= 3 , 0 , 0
       0      .1       0     404    .045       0     419      .1       0
Bank Sta=404,419
XS Rating Curve= 0 ,0
Exp/Cntr=0.3,0.1

Type RM Length L Ch R = 1 ,10137.4 ,403.6,400,395.6
XS GIS Cut Line= 3
        1964510.      294693.415      1964838.03      294448.616
     1965172.446      294210.364
#Sta/Elev= 30
       0 1652.35    59.9 1610.07    79.9 1593.42   159.7 1537.87   169.7 1530.29
   179.7 1519.08   209.6 1500.58   229.6 1490.56   259.6 1478.74   279.5 1465.58
   289.5 1461.88   379.4 1448.09   401.8 1446.27   409.3 1446.02   416.8 1446.04
   458.2 1446.75   487.5 1453.02   536.4 1469.63   565.7 1477.32   575.5 1482.76
   624.4 1501.92   663.5 1521.47   692.8 1544.34   702.6  1549.3   712.4 1551.83
   722.2 1557.66   761.2 1593.59   780.8  1605.8   800.4 1615.74   819.9 1622.55
#Mann= 3 , 0 , 0
       0      .1       0   401.8    .045       0   416.8      .1       0
Bank Sta=401.8,416.8
XS Rating Curve= 0 ,0
Exp/Cntr=0.3,0.1

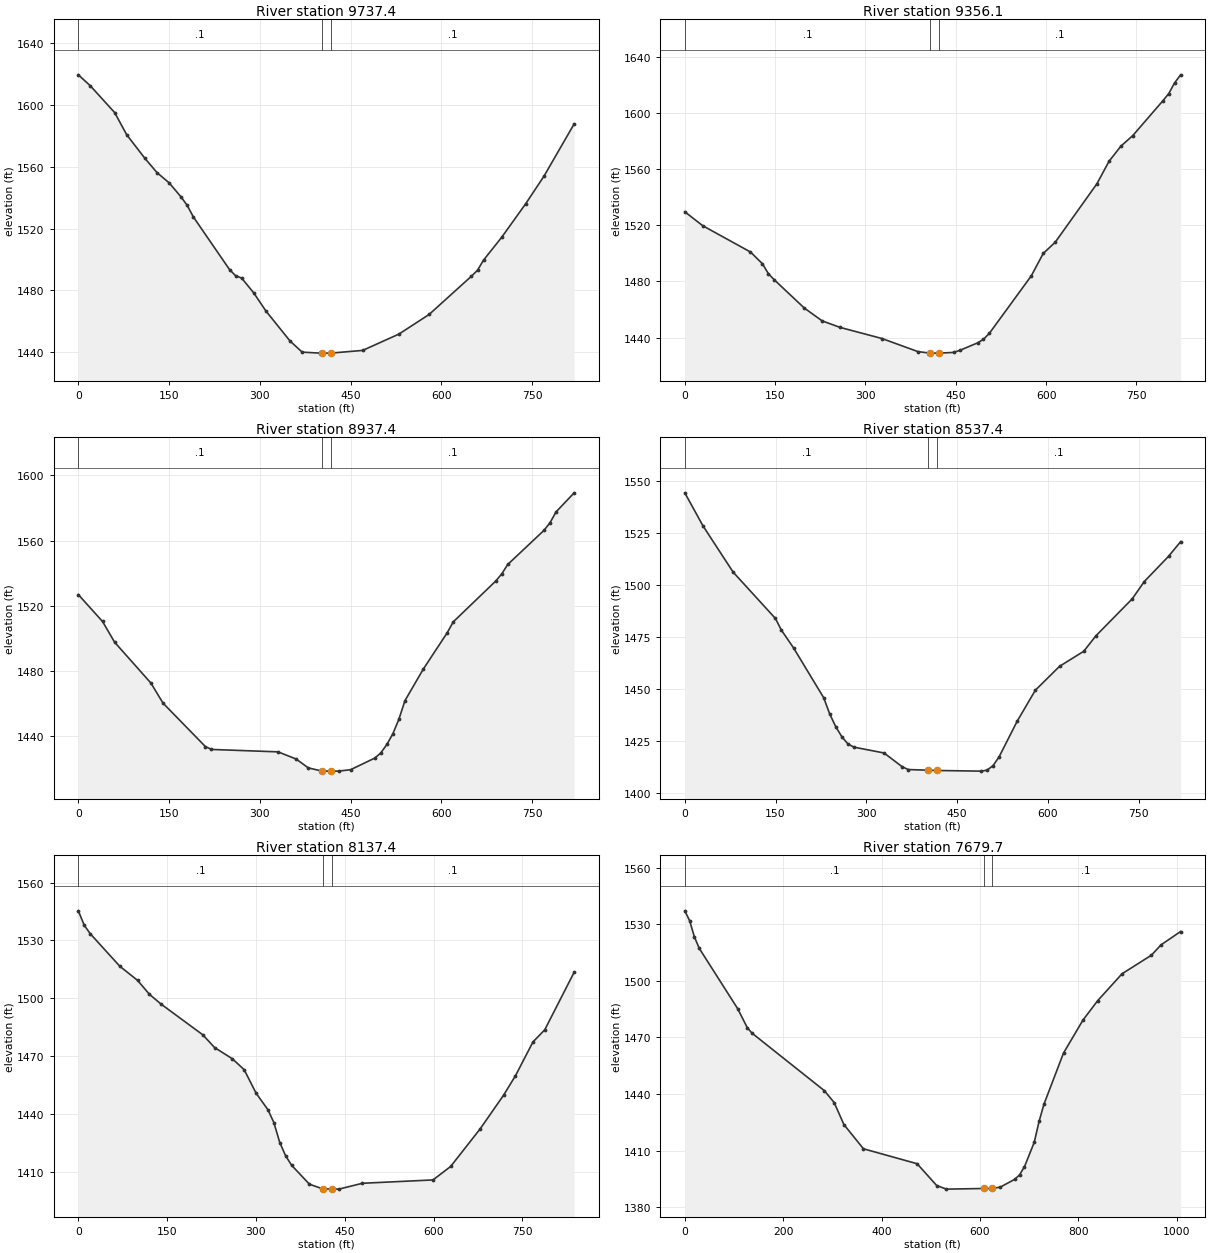
Type RM Length L Ch R = 1 ,9737.4  ,380.9,381.3,382
XS GIS Cut Line= 3
     1964841.107      295016.524     1965127.157      294722.915
     1965408.771      294425.754
#Sta/Elev= 30
       0 1619.44      20 1612.27      60 1595.03      80 1580.62     110  1565.4
     130 1556.16     150 1549.58     170 1540.32     180 1534.89     190 1527.53
     250 1493.35     260  1489.4   269.9 1487.92   289.9 1478.31   309.9 1466.66
   349.9 1447.17   369.9    1440   399.9 1439.36   402.4 1439.36   417.4 1439.38
   469.8 1441.11   529.7 1451.68   579.7 1464.39   649.6 1489.15   659.6 1492.98
   669.5 1499.52   699.5 1514.29   739.4 1536.13   769.4 1553.84   819.3 1587.69
#Mann= 3 , 0 , 0
       0      .1       0   402.4    .045       0   417.4      .1       0
Bank Sta=402.4,417.4
XS Rating Curve= 0 ,0
Exp/Cntr=0.3,0.1

Type RM Length L Ch R = 1 ,9356.1  ,402.5,418.7,435.8
XS GIS Cut Line= 2
     1965125.158      295255.801     1965710.276      294676.471
#Sta/Elev= 30
       0  1529.6    29.8 1519.68   109.1 1500.96     129 1492.57   138.9 1485.46
   148.8 1481.09   198.4 1461.09   228.2 1451.91   257.9 1447.29   327.4 1439.38
   386.9  1430.1   406.7 1428.98   407.1 1428.98   422.1 1428.99   446.4 1429.48
   456.3 1430.88   486.1 1436.25     496 1438.83   505.9 1443.15   575.4 1483.98
   595.2 1499.91   615.1  1507.9   684.5 1549.61   704.4 1565.48   724.2 1576.31
     744 1583.86   793.6 1608.46   803.6 1613.68   813.5 1621.42   823.4 1627.09
#Mann= 3 , 0 , 0
       0      .1       0   407.1    .045       0   422.1      .1       0
Bank Sta=407.1,422.1
XS Rating Curve= 0 ,0
Exp/Cntr=0.3,0.1

Type RM Length L Ch R = 1 ,8937.4  ,405,400,393.3
XS GIS Cut Line= 3
      1965169.39      295362.619     1965578.482      295335.329
     1965987.797       295326.43
#Sta/Elev= 30
       0 1526.79      40 1510.27      60 1497.53     120 1472.43     140  1460.1
     210 1433.43     220 1431.67     330 1430.18     360 1425.77     380 1420.34
   402.5 1418.39   417.5 1418.37     430 1418.34   449.9 1419.21   489.9 1426.35
   499.9 1429.52   509.9 1434.75   519.8 1441.29   529.8 1450.26   539.8 1461.65
   569.8 1480.86   609.7 1503.41   619.7 1510.09   689.6 1535.05   699.6 1539.44
   709.6 1545.29   769.5 1566.25   779.5 1570.93   789.5 1577.61   819.4 1589.32
#Mann= 3 , 0 , 0
       0      .1       0   402.5    .045       0   417.5      .1       0
Bank Sta=402.5,417.5
XS Rating Curve= 0 ,0
Exp/Cntr=0.3,0.1

Type RM Length L Ch R = 1 ,8537.4  ,409.8,400,385
XS GIS Cut Line= 3
     1965232.485      295847.421     1965624.813       295730.71
     1966014.497      295602.732
#Sta/Elev= 30
       0 1544.21      30 1528.37    79.9 1506.12   149.8 1483.87   159.7 1478.24
   179.7 1469.76   229.6 1445.78   239.6 1437.93   249.6 1431.84   259.6 1427.05
   269.6 1423.62   279.5 1422.07   329.4 1419.26   359.4 1412.63   369.4 1411.31
   401.8    1411   416.8 1410.86   489.4 1410.55   499.4 1410.99   509.4 1413.15
   519.4 1417.37   549.4 1434.55   579.4 1449.41   619.4 1460.89   659.4 1468.11
   679.4 1475.52   739.4 1493.26   759.5 1501.62   799.5 1513.71   819.5 1520.76
#Mann= 3 , 0 , 0
       0      .1       0   401.8    .045       0   416.8      .1       0
Bank Sta=401.8,416.8
XS Rating Curve= 0 ,0
Exp/Cntr=0.3,0.1

Type RM Length L Ch R = 1 ,8137.4  ,437.8,457.7,483.4
XS GIS Cut Line= 3
     1965538.921      296326.787     1965849.562      296043.811
      1966081.55      295697.079
#Sta/Elev= 30
       0 1545.32      10 1537.83      20 1533.49      70 1516.59     100 1509.25
   120.1 1502.01   140.1 1496.84   210.1 1481.03   230.1  1474.4   260.1 1468.57
   280.1  1462.9   300.2 1450.73   320.2 1442.14   330.2  1435.5   340.2 1425.13
   350.2 1418.17   360.2 1413.32   390.2 1403.52   412.7 1401.06   427.7 1401.01
   440.1 1400.94   479.8 1403.98     599 1405.71   628.8 1412.69   678.5 1432.15
   718.2 1449.66   738.1 1459.67   767.9 1477.33   787.7 1483.58   837.4 1513.46
#Mann= 3 , 0 , 0
       0      .1       0   412.7    .045       0   427.7      .1       0
Bank Sta=412.7,427.7
XS Rating Curve= 0 ,0
Exp/Cntr=0.3,0.1

Type RM Length L Ch R = 1 ,7679.7  ,305.9,305.6,305.2
XS GIS Cut Line= 3
     1965606.546      296394.598     1965811.487      296244.457
     1966556.443      296360.643
#Sta/Elev= 30
       0 1537.19     9.8 1531.98    19.5 1523.39    29.3 1517.32   107.5 1485.28
     127  1475.2   136.8 1472.26   283.8 1441.77   303.7 1435.45   323.5 1423.78
   363.2 1410.94   472.3 1403.02     512 1391.46   531.8 1389.54   609.1 1389.88
   624.1 1389.89     641 1390.56   670.7 1394.74   680.6  1397.1   690.6 1401.47
   710.4 1414.37   720.3 1425.52   730.2 1434.62   769.9 1461.73   809.6 1479.28
   839.4 1489.53     889 1503.81   948.5 1513.63   968.3 1519.16    1008 1526.22
#Mann= 3 , 0 , 0
       0      .1       0   609.1    .045       0   624.1      .1       0
Bank Sta=609.1,624.1
XS Rating Curve= 0 ,0
Exp/Cntr=0.3,0.1

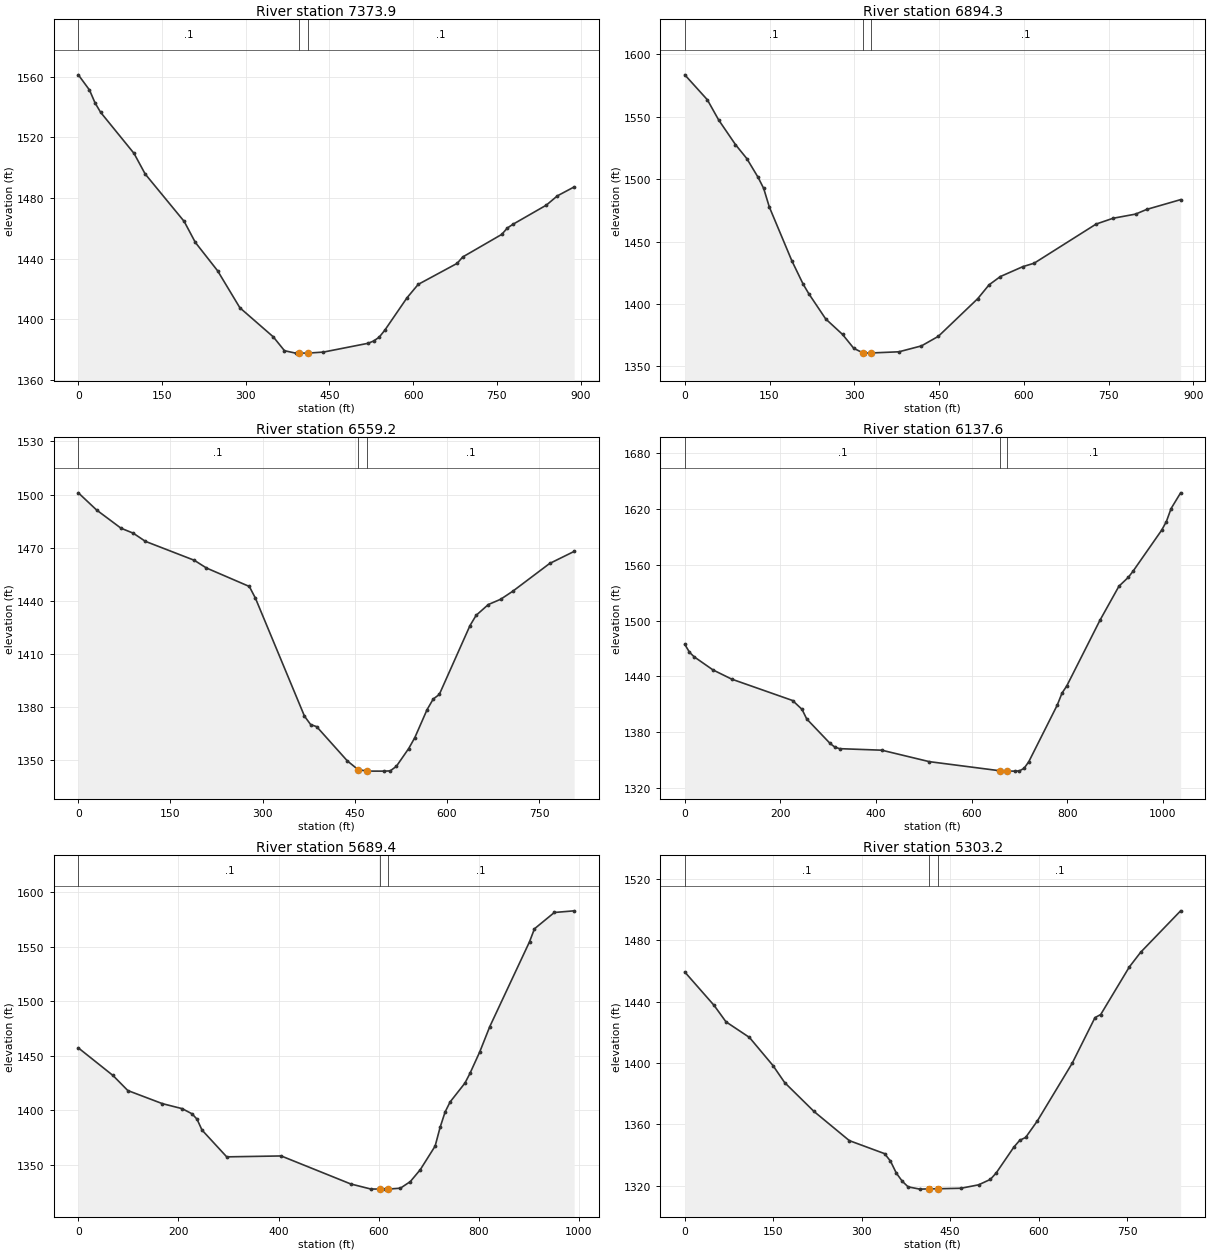
Type RM Length L Ch R = 1 ,7373.9  ,495.4,479.5,463.6
XS GIS Cut Line= 2
     1965592.552      296489.801     1966473.165      296607.684
#Sta/Elev= 30
       0 1561.26      20 1551.23      30 1542.72    39.9 1536.56    99.8 1509.45
   119.8 1495.86   189.7 1464.58   209.6  1450.8   249.6 1432.04   289.5 1407.65
   349.4 1388.46   369.4 1379.35   389.3 1377.75   396.1 1377.77   411.1 1377.76
   439.2 1378.44   519.1 1384.23   529.1 1385.73   539.1 1388.26     549 1392.77
     589 1414.26     609 1423.07   678.8 1436.94   688.8 1441.15   758.7 1456.03
   768.7 1460.22   778.7 1462.68   838.6 1475.33   858.5 1481.47   888.5 1487.34
#Mann= 3 , 0 , 0
       0      .1       0   396.1    .045       0   411.1      .1       0
Bank Sta=396.1,411.1
XS Rating Curve= 0 ,0
Exp/Cntr=0.3,0.1

Type RM Length L Ch R = 1 ,6894.3  ,348,335.1,322.1
XS GIS Cut Line= 2
     1965748.458      297185.714     1966488.068      296713.602
#Sta/Elev= 30
       0 1583.54    39.9 1563.56    59.8 1547.48    89.7 1527.64   109.7 1516.48
   129.6 1501.51   139.6 1492.54   149.6 1477.63   189.4 1434.62   209.4 1415.88
   219.4 1408.23   249.3 1388.03   279.2 1375.57   299.1 1364.43   314.7 1360.96
   319.1 1360.62   329.7 1360.75   378.9 1361.69   418.8 1366.42   448.7 1374.09
   518.5 1404.32   538.4 1415.32   558.4 1421.96   598.3 1429.91   618.2 1432.65
   727.9 1464.01   757.8 1468.64   797.7 1471.98   817.6 1475.77   877.4 1483.57
#Mann= 3 , 0 , 0
       0      .1       0   314.7    .045       0   329.7      .1       0
Bank Sta=314.7,329.7
XS Rating Curve= 0 ,0
Exp/Cntr=0.3,0.1

Type RM Length L Ch R = 1 ,6559.2  ,413.7,421.6,429.5
XS GIS Cut Line= 3
     1966031.586      297498.021     1966207.126      297367.967
     1966453.167       296833.36
#Sta/Elev= 30
       0 1500.98    29.8 1491.27    69.5 1481.01    89.4 1478.21   109.2  1473.6
   188.7 1462.93   208.5 1458.57   278.3 1448.15   288.3  1441.5   368.1 1374.96
   378.1 1370.25     388 1369.04   437.9 1349.72   455.3 1344.84   470.3 1343.98
   497.8 1343.97   507.7 1344.11   517.7 1346.72   537.7 1356.72   547.6 1362.83
   567.6 1378.65   577.6 1384.64   587.5 1387.22   637.4 1426.04   647.4 1431.85
   667.3 1437.95   687.3 1440.92   707.2 1445.49   767.1 1461.12     807 1467.93
#Mann= 3 , 0 , 0
       0      .1       0   455.3    .045       0   470.3      .1       0
Bank Sta=455.3,470.3
XS Rating Curve= 0 ,0
Exp/Cntr=0.3,0.1

Type RM Length L Ch R = 1 ,6137.6  ,417.8,448.2,478.6
XS GIS Cut Line= 3
     1966104.537      297558.287     1966492.655      297501.618
     1966948.924      297045.963
#Sta/Elev= 30
       0 1474.43     9.8 1466.02    19.6 1461.08    58.8 1447.09    98.1 1437.16
   225.5 1414.22   245.2 1404.74     255 1394.47     304 1368.15   313.8 1364.29
   323.6  1362.6   412.1 1360.95   511.3 1348.68   659.8 1338.84   674.8 1338.53
   689.8  1338.5   699.8 1338.74   709.7 1341.52   719.6  1348.7   779.1 1409.36
     789 1422.19     799 1429.93   868.4 1500.33   908.1 1536.83   927.9 1546.46
   937.9 1553.15   997.4 1596.89  1007.3 1606.15  1017.2 1620.16  1037.1 1636.97
#Mann= 3 , 0 , 0
       0      .1       0   659.8    .045       0   674.8      .1       0
Bank Sta=659.8,674.8
XS Rating Curve= 0 ,0
Exp/Cntr=0.3,0.1

Type RM Length L Ch R = 1 ,5689.4  ,385,385.9,386.8
XS GIS Cut Line= 3
      1966114.89      297650.686     1966462.279      297574.519
     1967001.773      297909.066
#Sta/Elev= 30
       0 1457.38    69.2 1432.07    98.8 1418.27   167.9 1406.24   207.5 1401.63
   227.2  1396.9   237.1    1392     247 1382.04   296.4 1357.44   405.2 1358.27
   544.1 1332.58   583.8 1327.98   603.1 1327.85   613.5 1327.84   618.1 1327.85
   643.3  1328.7   663.1 1334.74     683 1345.66   712.7 1367.33   722.6 1384.44
   732.6 1398.58   742.5 1407.72   772.2 1425.08   782.2 1433.93     802 1453.91
   821.8 1476.85   901.2 1554.68   911.1  1566.6   950.8 1581.57   990.4 1583.09
#Mann= 3 , 0 , 0
       0      .1       0   603.1    .045       0   618.1      .1       0
Bank Sta=603.1,618.1
XS Rating Curve= 0 ,0
Exp/Cntr=0.3,0.1

Type RM Length L Ch R = 1 ,5303.2  ,374.1,366,356.9
XS GIS Cut Line= 3
     1966062.422       297735.35     1966577.706      298093.938
     1966705.344      298264.547
#Sta/Elev= 30
       0 1459.39    49.8 1437.56    69.8  1426.9   109.6 1416.71   149.5 1398.38
   169.4 1387.22   219.2 1368.38     279 1349.38   338.8 1340.88   348.8    1336
   358.7 1328.18   368.7 1322.92   378.7  1319.2   398.6 1317.73   414.9  1317.9
   429.9 1317.98   468.3  1318.3   498.2 1320.53   518.2 1324.09   528.1 1328.31
     558 1345.14     568  1349.6     578 1351.45   597.9 1362.26   656.8 1399.79
   695.6 1429.64   705.3 1431.66   753.7 1462.62     773 1472.27   840.8 1499.31
#Mann= 3 , 0 , 0
       0      .1       0   414.9    .045       0   429.9      .1       0
Bank Sta=414.9,429.9
XS Rating Curve= 0 ,0
Exp/Cntr=0.3,0.1

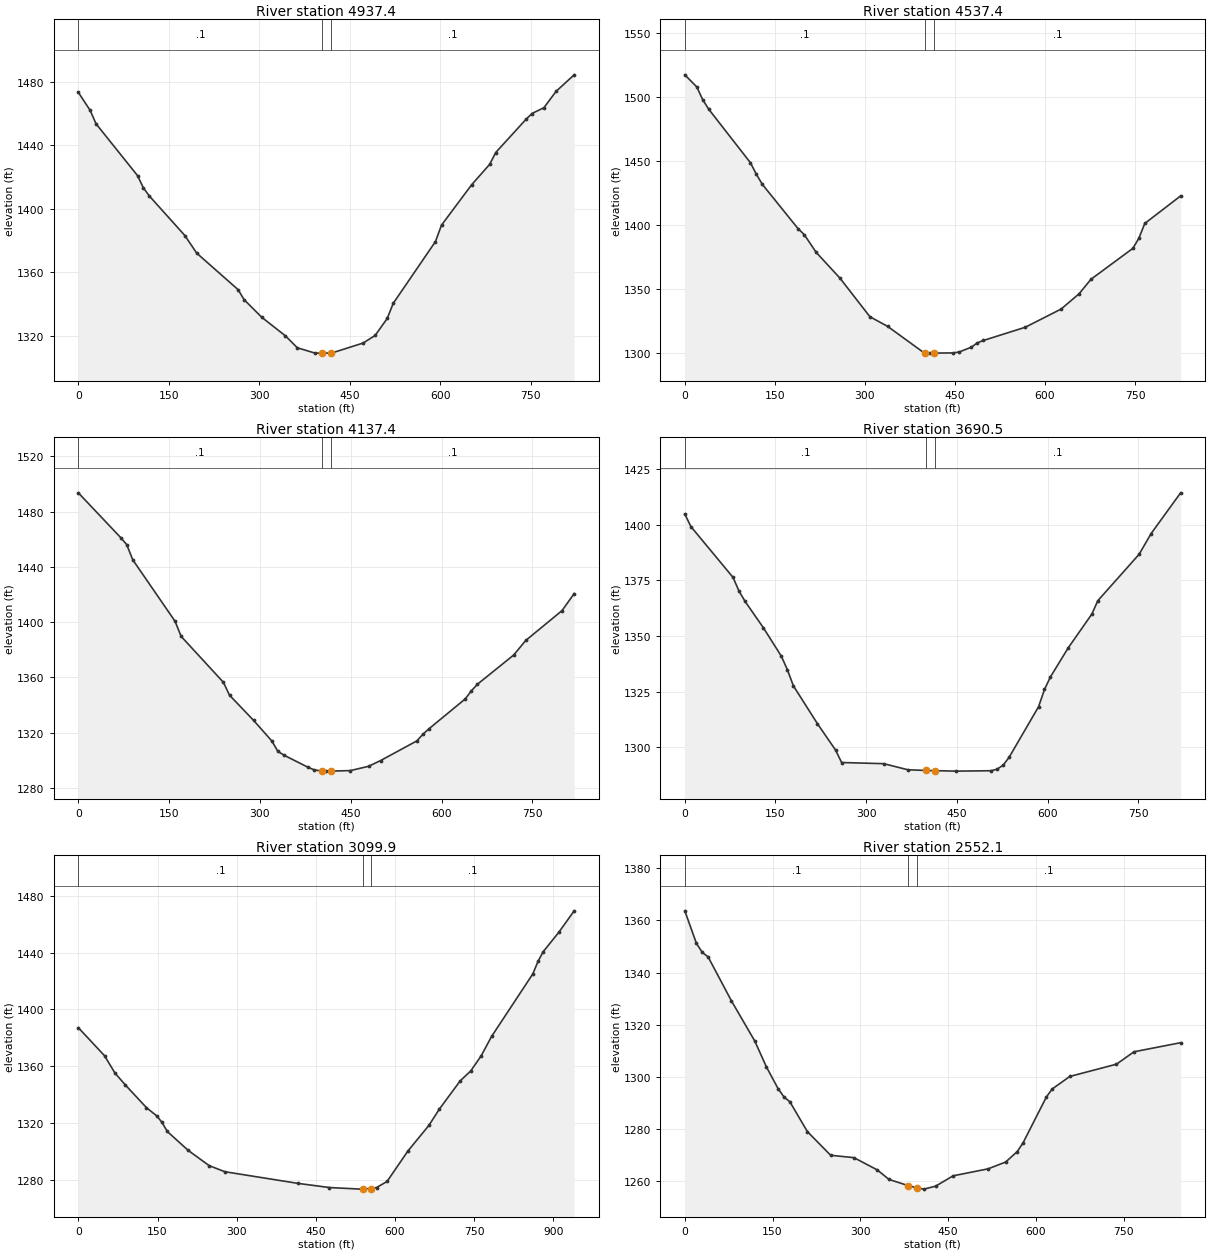
Type RM Length L Ch R = 1 ,4937.4  ,394.1,399.9,407.4
XS GIS Cut Line= 3
     1965848.786       298190.81     1966249.006      298289.045
     1966651.244      298367.188
#Sta/Elev= 30
       0 1473.17    19.6 1461.84    29.4 1453.38    98.1 1420.85   107.9 1413.09
   117.7 1408.02   176.6 1383.15   196.2  1372.1   264.9  1349.1   274.7 1342.86
   304.2 1331.71   343.4 1320.04     363 1312.58   392.5 1309.21   404.6 1309.24
   419.6 1309.24   472.1 1315.55     492 1320.32     512 1330.99     522 1340.52
     592 1379.37     602 1389.69     652 1415.09   681.9 1427.94   691.9 1435.36
   741.9 1456.15   751.9 1459.86   771.9 1463.56   791.9  1473.8   821.9  1484.2
#Mann= 3 , 0 , 0
       0      .1       0   404.6    .045       0   419.6      .1       0
Bank Sta=404.6,419.6
XS Rating Curve= 0 ,0
Exp/Cntr=0.3,0.1

Type RM Length L Ch R = 1 ,4537.4  ,408.5,400,390.8
XS GIS Cut Line= 3
     1965686.249      298426.806     1966045.865      298619.025
     1966409.234      298826.187
#Sta/Elev= 30
       0 1517.61    19.9 1508.19    29.8  1498.2    39.8 1490.76   109.4 1448.82
   119.4 1439.66   129.3 1431.88     189 1397.13   198.9 1392.71   218.8 1378.79
   258.6 1358.54   308.3 1328.45   338.2 1320.78   397.8 1300.45   400.3 1300.32
   407.8 1299.95   415.3 1299.98   447.6 1300.13   457.6 1300.93   477.5 1304.64
   487.4 1308.02   497.4 1309.84   567.1 1320.17   626.9 1334.42   656.7  1346.3
   676.6 1357.68   746.4 1381.88   756.3 1389.66   766.3 1401.37     826 1422.92
#Mann= 3 , 0 , 0
       0      .1       0   400.3    .045       0   415.3      .1       0
Bank Sta=400.3,415.3
XS Rating Curve= 0 ,0
Exp/Cntr=0.3,0.1

Type RM Length L Ch R = 1 ,4137.4  ,455.9,446.7,436.5
XS GIS Cut Line= 3
     1965546.909      298960.826     1965953.834      299006.676
     1966360.759      299052.527
#Sta/Elev= 30
       0 1493.68    69.9  1461.3    79.9 1456.21    89.9  1445.2   159.8 1400.66
   169.8 1389.77   239.7 1356.46   249.7 1347.18   289.6 1328.88   319.6 1314.05
   329.6 1306.53   339.6 1303.76   379.5 1294.95   389.5 1293.11     402 1292.24
   409.5 1292.19     417  1292.2   449.4 1292.58   479.4 1295.69   499.4 1299.87
   559.3 1314.11   569.3 1318.95   579.3 1322.89   639.2 1344.51   649.2 1350.31
   659.2 1355.09   719.1 1376.25   739.1 1386.82     799 1408.42     819 1420.74
#Mann= 3 , 0 , 0
       0      .1       0     402    .045       0     417      .1       0
Bank Sta=402,417
XS Rating Curve= 0 ,0
Exp/Cntr=0.3,0.1

Type RM Length L Ch R = 1 ,3690.5  ,568.8,590.7,613.5
XS GIS Cut Line= 3
     1965626.649      299562.579     1966017.789      299442.995
     1966404.999      299304.523
#Sta/Elev= 30
       0  1404.9      10 1399.25    79.8 1376.35    89.8 1370.12    99.8 1365.52
   129.7  1353.8   159.6 1340.94   169.6 1334.87   179.6 1327.57   219.5 1310.48
   249.4 1298.65   259.4 1293.05   329.2 1292.52   369.1 1289.78   399.2 1289.47
   414.2 1289.38   448.2 1289.17   506.9 1289.35   516.7 1290.05   526.5 1291.85
   536.3 1295.31   585.2 1318.16     595 1325.91   604.8 1331.56   634.2 1344.62
   673.4 1359.87   683.2 1365.86   751.7 1386.81   771.3 1396.05   820.2 1414.41
#Mann= 3 , 0 , 0
       0      .1       0   399.2    .045       0   414.2      .1       0
Bank Sta=399.2,414.2
XS Rating Curve= 0 ,0
Exp/Cntr=0.3,0.1

Type RM Length L Ch R = 1 ,3099.9  ,546.9,547.4,547.9
XS GIS Cut Line= 3
     1965663.407      299637.007     1966261.802      300110.863
     1966410.641      300205.027
#Sta/Elev= 30
       0 1387.09    49.6 1367.34    69.4 1355.12    89.2 1346.69   128.9 1330.82
   148.7 1324.89   158.6 1320.35   168.5 1313.98   208.2 1300.63   247.8 1289.92
   277.6 1285.61   416.3 1277.39   475.8 1274.47   535.3 1273.35   539.5  1273.4
   554.5 1273.78     565 1274.48   584.9 1278.73   624.5 1300.26   664.2 1318.24
     684 1329.74   723.6 1349.67   743.5 1356.62   763.3  1367.3   782.9 1380.89
   861.1 1424.98   870.9 1433.76   880.7 1440.59   910.1 1454.17   939.4  1469.4
#Mann= 3 , 0 , 0
       0      .1       0   539.5    .045       0   554.5      .1       0
Bank Sta=539.5,554.5
XS Rating Curve= 0 ,0
Exp/Cntr=0.3,0.1

Type RM Length L Ch R = 1 ,2552.1  ,434.8,415,398.5
XS GIS Cut Line= 2
     1965368.766      300071.375     1966018.799      300615.094
#Sta/Elev= 30
       0 1363.63    19.9 1351.15    29.9 1347.71    39.9 1345.97    79.8  1329.1
   119.6 1313.76   139.6 1303.79   159.5 1295.51   169.5 1292.33   179.5 1290.52
   209.4  1279.1   249.2 1270.01   289.1 1269.08     329 1264.39     349 1260.74
   381.8 1258.38   396.8 1257.54   408.8 1257.03   428.7 1258.17   458.6 1262.13
   518.4  1264.8   548.4 1267.42   568.3 1271.44   578.3 1274.84   618.1 1292.38
   628.1 1295.42     658 1300.19   737.8 1304.89   767.7 1309.64   847.4 1313.12
#Mann= 3 , 0 , 0
       0      .1       0   381.8    .045       0   396.8      .1       0
Bank Sta=381.8,396.8
XS Rating Curve= 0 ,0
Exp/Cntr=0.3,0.1