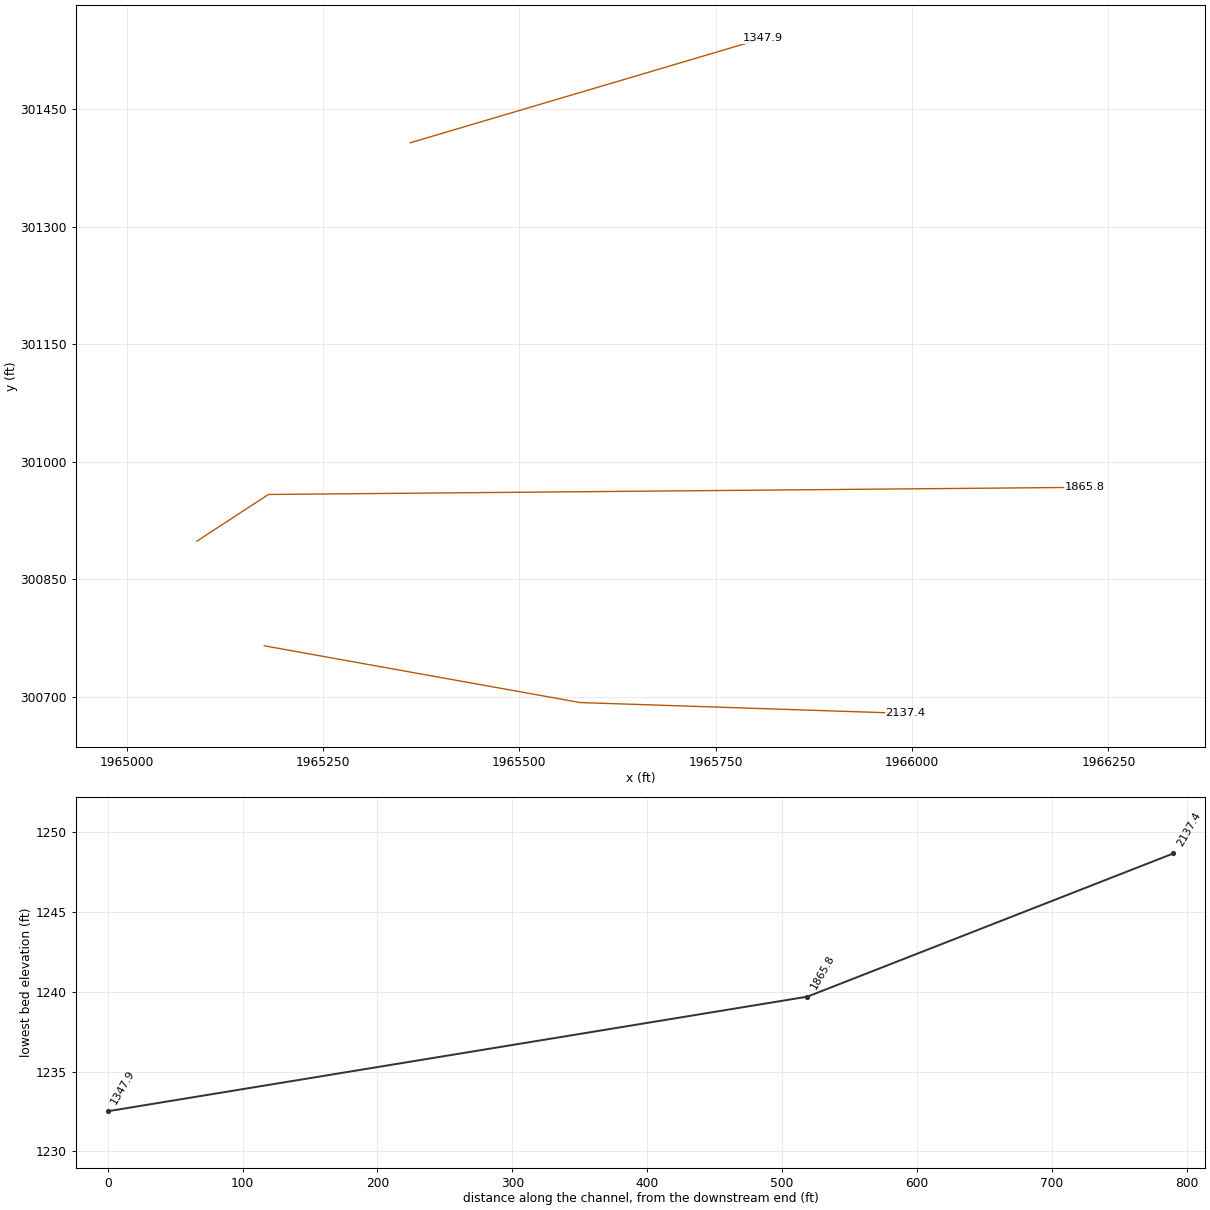
HEC-RAS study GldCrk.prj: GldCrk

--- GldCrk.g01 (geometry) --- (continued)

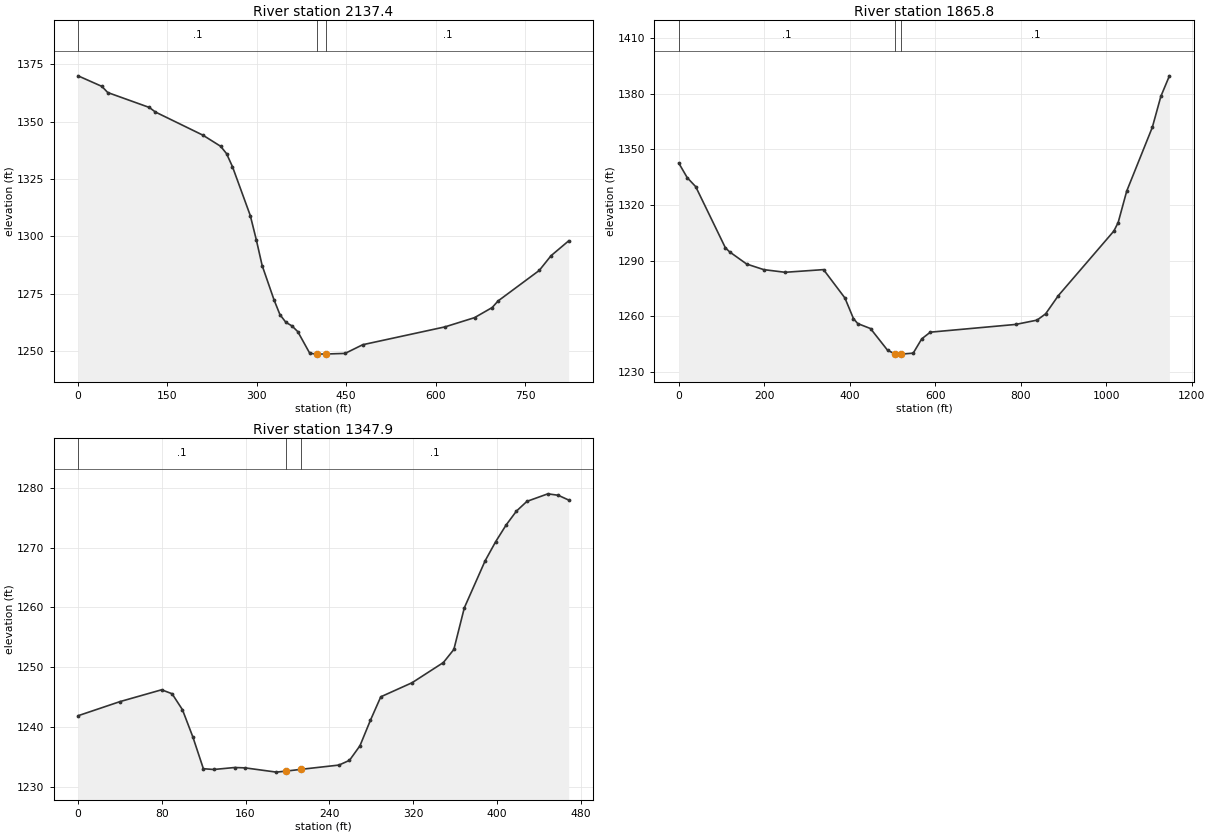
Type RM Length L Ch R = 1 ,2137.4  ,267.3,271.5,272.5
XS GIS Cut Line= 3
     1965175.162      300765.221     1965577.283      300692.839
     1965991.746      300679.027
#Sta/Elev= 30
       0  1369.9    39.9 1365.31    49.8 1362.62   119.6 1356.12   129.6 1354.16
   209.3 1344.08   239.2 1339.22   249.1 1336.03   259.1 1330.33     289 1309.04
     299 1298.59   308.9 1287.28   328.9 1272.27   338.8 1265.86   348.8 1262.51
   358.8    1261   368.7 1258.48   388.6 1249.14   398.6 1248.68   401.1  1248.7
   416.1 1248.73   448.1    1249   477.7 1252.78   615.9 1260.56   665.3 1264.57
   694.9 1268.97   704.8 1271.84   773.9 1285.13   793.7 1291.55   823.3 1298.02
#Mann= 3 , 0 , 0
       0      .1       0   401.1    .045       0   416.1      .1       0
Bank Sta=401.1,416.1
XS Rating Curve= 0 ,0
Exp/Cntr=0.3,0.1

Type RM Length L Ch R = 1 ,1865.8  ,513.5,518.8,524.1
XS GIS Cut Line= 3
     1965089.312      300898.724     1965180.438      300958.336
     1966219.276      300967.448
#Sta/Elev= 30
       0 1342.59    19.8 1334.73    39.6 1329.91   108.9 1297.02   118.9 1294.79
   158.8 1288.23   198.8 1285.22   248.7 1283.79   338.6 1285.23   388.6 1269.96
   408.6 1258.84   418.6 1256.16   448.5 1253.48   488.5 1241.77   505.2 1239.89
   518.4  1239.7   520.2 1239.71   548.4 1240.23   568.4 1247.94   588.4 1251.53
   788.2  1255.7   838.1 1258.02   858.1 1261.39     888 1271.24  1017.9 1306.03
  1027.9  1310.6  1047.9 1327.53  1107.8 1361.88  1127.8 1378.58  1147.8 1389.63
#Mann= 3 , 0 , 0
       0      .1       0   505.2    .045       0   520.2      .1       0
Bank Sta=505.2,520.2
XS Rating Curve= 0 ,0
Exp/Cntr=0.3,0.1

Type RM Length L Ch R = 1 ,1347.9  ,1363.9,1347,1330
XS GIS Cut Line= 2
     1965360.982      301407.037     1965810.348      301540.309
#Sta/Elev= 30
       0 1241.93    39.9 1244.28    79.8 1246.26    89.8  1245.6    99.7 1242.94
   109.7 1238.37   119.7 1233.09   129.6 1232.96   149.6 1233.29   159.6 1233.23
   189.5 1232.52   198.2 1232.68   213.2 1232.99   249.3  1233.7   259.3 1234.49
   269.3 1236.92   279.2 1241.14   289.2 1245.09   319.1 1247.44     349 1250.81
     359 1252.99     369 1259.94   388.9 1267.79   398.9 1270.96   408.9 1273.75
   418.8 1276.08   428.8  1277.7   448.8 1278.96   458.7 1278.72   468.7 1277.92
#Mann= 3 , 0 , 0
       0      .1       0   198.2    .045       0   213.2      .1       0
Bank Sta=198.2,213.2
XS Rating Curve= 0 ,0
Exp/Cntr=0.3,0.1

Chan Stop Cuts=-1
Use User Specified Reach Order=0
Composite Channel Slope=5